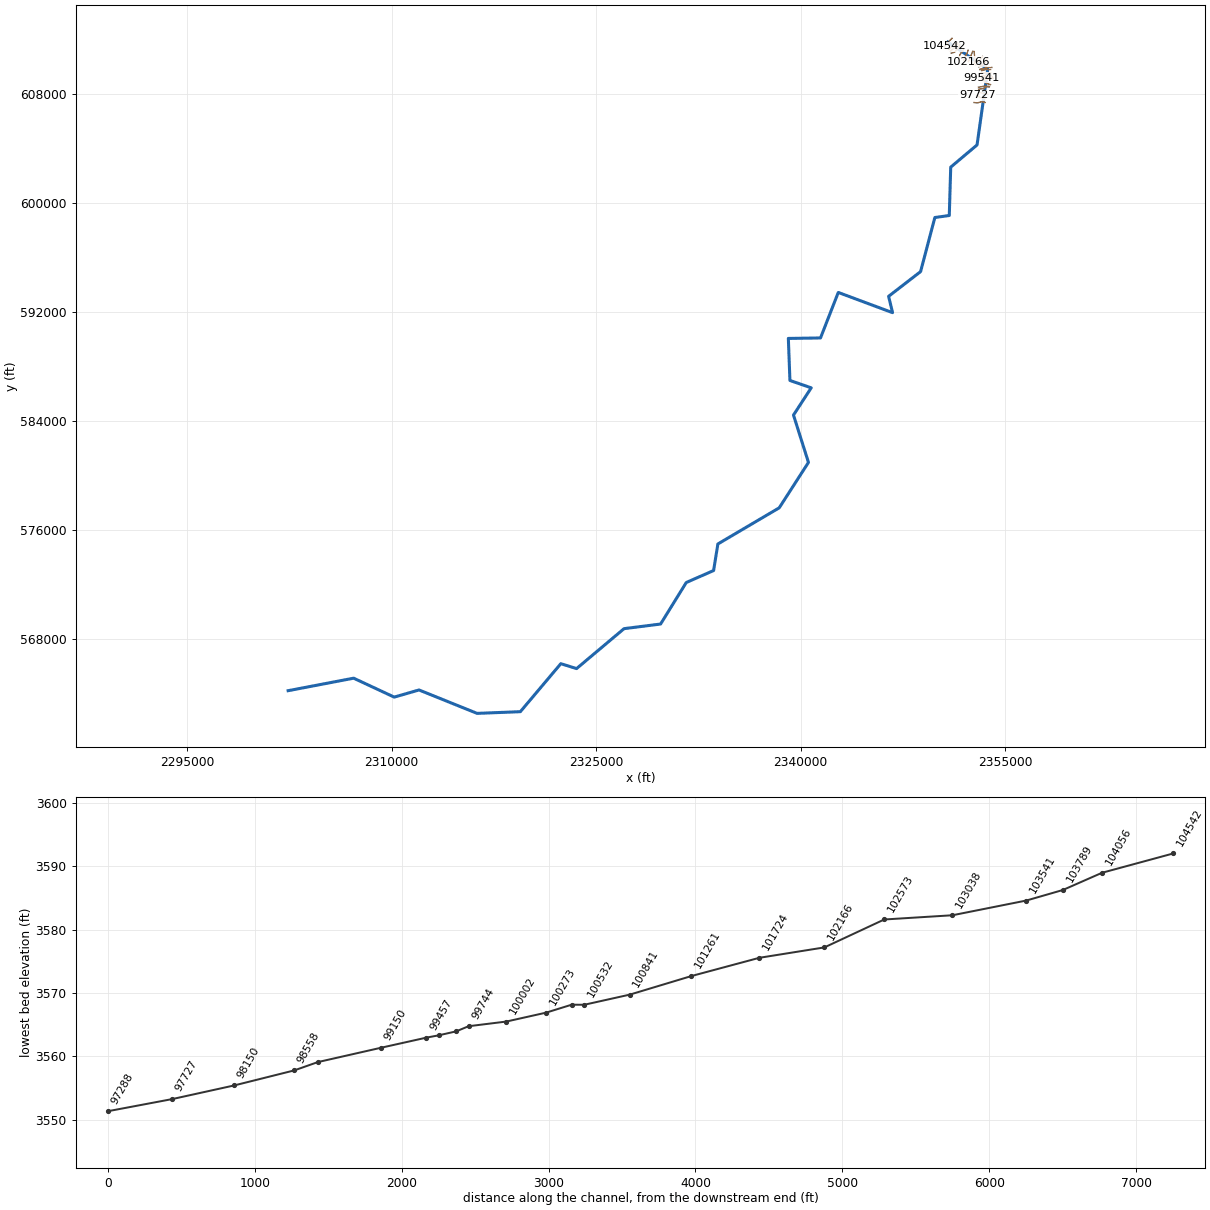
--- EFGRNBRRRV.prj (project) ---

Proj Title=EFGRNBRRRV
Current Plan=p01
Default Exp/Contr=0,0
English Units
Geom File=g01
Flow File=f01
Plan File=p01
Background Map Layer=Inundation Boundary (01pct Value_0)
Background Map Layer=Inundation Boundary (01pct Value_0)
Background Map Layer=StudyTypeAE
Background Map Layer=Inundation Boundary (01pct Value_0)
Background Map Layer=Inundation Boundary (01pct Value_0)
Y Axis Title=Elevation
X Axis Title(PF)=Main Channel Distance
X Axis Title(XS)=Station
BEGIN DESCRIPTION:
----------MODEL BY WOOD PLC 2021----------
Stream Name: East Fork Greenbrier River
Flood Zone: Alternating Approximate / Detailed
Pocahontas County, WV
HEC-RAS Version: RAS 6.0
Vertical Datum: NAVD88
Projection: NAD 1983 StatePlane West Virginia S FIPS 4702 (US Feet)
Terrain: 1-meter LIDAR (FEMA Region III 3DEP collected 2016-2018)
Land Use: 2019 NLCD
Hydrologic Method:
Gage-Weighted WV 2010 RRE
Model Notes:
Alternating A/AE Reach:
Zone AE- 0 -  42238
Zone A -  42430 - 104542
KWSEL tie in with Greenbrier River
Please note that the flows switch between regression and gage weighting and the 1% plus gets higher than 500 year. Profile crossing exists upstream of cross section 34845
END DESCRIPTION:
DSS File=dss
DSS Export Rating Curves= 0
DSS Export Rating Curve Sorted= 0
DSS Export Volume Flow Curves= 0
DXF Filename=.\Backup\FROMKEVINITRDONE\EFGRNBRRRV_KW\EFGRNBRRRV.
DXF OffsetX= 0
DXF OffsetY= 0
DXF ScaleX= 0
DXF ScaleY= 0

--- EFGRNBRRRV.p01 (plan) ---

Plan Title=Floodplain
Program Version=6.10
Short Identifier=Floodplain
Geom File=g01
Flow File=f01
Subcritical Flow
K Sum by GR= 0
Std Step Tol= 0.01
Critical Tol= 0.01
Num of Std Step Trials= 20
Max Error Tol= 0.3
Flow Tol Ratio= 0.001
Split Flow NTrial= 30
Split Flow Tol= 0.02
Split Flow Ratio= 0.02
Log Output Level= 0
Friction Slope Method= 1
Unsteady Friction Slope Method= 2
Unsteady Bridges Friction Slope Method= 1
Parabolic Critical Depth
Global Vel Dist= 0 , 0 , 0
Global Log Level= 0
CheckData=True
Encroach Param=-1 ,0,0, 2
Encroach River=EFGRNBRRRV
Encroach Reach=Main
Encroach Node=42430
       1  538.04   810.8
Encroach Node=42238
       1  528.51   898.2
Encroach Node=41802
       1   408.5   855.3
Encroach Node=41234
       1  324.53  703.29
Encroach Node=40774
       1   299.2  510.78
Encroach Node=40605
       1  350.75  581.33
Encroach Node=40185
       1   258.2     325
Encroach Node=39665
       1     346  585.99
Encroach Node=39462
       1  324.34     550
Encroach Node=39297
       1  422.36     685
Encroach Node=39246
       1  412.16     658
Encroach Node=39059
       1  544.29  784.33
Encroach Node=38609
       1  762.36  982.61
Encroach Node=38208
       1   765.5 1014.35
Encroach Node=37915
       1  876.91 1060.05
Encroach Node=37658
       1   872.2     968
Encroach Node=37236
       1  781.52  916.94
Encroach Node=36819
       1  905.68 1079.97
Encroach Node=36485
       1  924.64  1046.2
Encroach Node=36158
       1  914.59 1033.43
Encroach Node=35785
       1     796     945
Encroach Node=35378
       1   782.5   886.8
Encroach Node=35085
       1     696     812
Encroach Node=34845
       1     748     910
Encroach Node=34760
       1     793  912.57
Encroach Node=34384
       1     135     425
Encroach Node=33877
       1   210.2  520.54
Encroach Node=33451
       1   263.9  588.96
Encroach Node=32851
       1  163.02  564.15
Encroach Node=32289
       1   233.8  656.88
Encroach Node=31904
       1  318.31   728.6
Encroach Node=31315
       1  329.55  705.79
Encroach Node=31083
       1   321.3  737.35
Encroach Node=30585
       1  376.08   733.6
Encroach Node=29881
       1     183   512.2
Encroach Node=29727
       1     180  539.25
Encroach Node=29474
       1   127.2  625.49
Encroach Node=29272
       1  143.52   683.9
Encroach Node=28980
       1   302.5  922.45
Encroach Node=28680
       1  421.28 1094.35
Encroach Node=27929
       1  265.06   767.9
Encroach Node=27456
       1  284.43  909.39
Encroach Node=26717
       1  247.24   631.7
Encroach Node=26389
       1  383.98  851.37
Encroach Node=26051
       1   378.9   732.8
Encroach Node=25556
       1     366     664
Encroach Node=24985
       1     595    1018
Encroach Node=24743
       1     735    1224
Encroach Node=24658
       1     750    1316
Encroach Node=24278
       1  990.15  1582.9
Encroach Node=24054
       1 1143.25  1648.6
Encroach Node=23832
       1 1412.35 1866.84
Encroach Node=23327
       1 1515.01 1966.81
Encroach Node=22823
       1  1374.1  1783.9
Encroach Node=22322
       1    1170 1565.22
Encroach Node=21800
       1    1185    1484
Encroach Node=21205
       1     845  1198.7
Encroach Node=20671
       1     780    1275
Encroach Node=19727
       1   348.9     825
Encroach Node=19096
       1  667.88    1342
Encroach Node=18954
       1     625 1274.05
Encroach Node=18474
       1   401.7     889
Encroach Node=18033
       1     263   703.9
Encroach Node=17764
       1     327     770
Encroach Node=17448
       1     350     793
Encroach Node=17276
       1  307.24  758.83
Encroach Node=16662
       1  408.36  861.54
Encroach Node=16034
       1   328.1     756
Encroach Node=15607
       1     260  801.04
Encroach Node=15338
       1   236.9   696.6
Encroach Node=15048
       1  210.79     725
Encroach Node=14719
       1   393.3     960
Encroach Node=14362
       1  354.23     950
Encroach Node=14062
       1  396.35     871
Encroach Node=13646
       1   271.8     640
Encroach Node=13012
       1   287.7  866.95
Encroach Node=12707
       1     339 1044.53
Encroach Node=12341
       1   576.2  1155.5
Encroach Node=11871
       1   613.5  1141.9
Encroach Node=11480
       1  439.31  1008.5
Encroach Node=11045
       1  372.92 1100.23
Encroach Node=10711
       1  334.04 1321.35
Encroach Node=9993
       1  349.22    1500
Encroach Node=9733
       1     198 1406.79
Encroach Node=9483
       1  683.02    2080
Encroach Node=9170
       1  231.14    1740
Encroach Node=8923
       1   335.6 1800.77
Encroach Node=8657
       1  324.48    1739
Encroach Node=8579
       1     348    1692
Encroach Node=8559
       1     365    1700
Encroach Node=8495
       1     370    1650
Encroach Node=8206
       1  437.28 1876.13
Encroach Node=7776
       1  423.58    1439
Encroach Node=7312
       1  450.44    1232
Encroach Node=6567
       1  397.83    1310
Encroach Node=5972
       1  450.48    1203
Encroach Node=5404
       1  379.77  851.92
Encroach Node=4794
       1   267.6  691.71
Encroach Node=4189
       1     200     573
Encroach Node=3813
       1  405.14     750
Encroach Node=3698
       1     358  659.94
Encroach Node=3204
       1  430.68  738.01
Encroach Node=2743
       1  448.24  906.83
Encroach Node=2332
       1     338  759.18
Encroach Node=1943
       1  430.27  819.33
Encroach Node=1644
       1     316  726.48
Encroach Node=1302
       1   398.6  655.14
Encroach Node=1080
       1  359.85     529
Encroach Node=782
       1     367     560
Encroach Node=337
       1   370.9  597.55
Encroach Node=0
       1   454.7  742.47
Computation Interval=0.1SEC
Output Interval=1SEC
Instantaneous Interval=Max Profile
Mapping Interval=1HOUR
Computation Time Step Use Courant=        0
Computation Time Step Use Time Series=    0
Computation Time Step Count To Double=0
Computation Time Step Max Doubling=0
Computation Time Step Max Halving=0
Computation Time Step Residence Courant=0
Run HTab= 0
Run UNet= 0
Run Sediment= 0
Run PostProcess= 0
Run WQNet= 0
Run RASMapper=-1
UNET Theta= 0
UNET Theta Warmup= 0
UNET ZTol= 0
UNET ZSATol= 0
UNET MxIter= 0
UNET Max Iter WO Improvement= 0
UNET MaxInSteps= 0
UNET DtIC= 0
UNET DtMin= 0
UNET MaxCRTS= 0
UNET WFStab= 0
UNET SFStab= 0
UNET WFX= 1
UNET SFX= 1
UNET Gravity=32.174
UNET 1D Methodology=Finite Difference
UNET DSS MLevel= 1
UNET Pardiso=0
UNET DZMax Abort= 0
UNET Use Existing IB Tables= 0
UNET Froude Reduction=False
UNET Froude Limit= 0
UNET Froude Power= 0
UNET D1 Cores= 0
UNET WindReference=Eulerian
UNET WindDragFormulation=Hsu (1988)
UNET D2 Coriolis=0
UNET D2 Cores= 0
UNET D2 Theta= 1
UNET D2 Theta Warmup= 1
UNET D2 Z Tol= 0.01
UNET D2 Volume Tol= 0.01
UNET D2 Max Iterations= 20
UNET D2 Equation= 0
UNET D2 RampUpFraction=0.1
UNET D2 TimeSlices= 1
UNET D2 Turbulence Formulation=Non-Conservative (original)
UNET D2 Eddy Viscosity=0.3
UNET D2 Transverse Eddy Viscosity=0.1
UNET D2 Smagorinsky Mixing=0
UNET D2 BCVolumeCheck=0
UNET D2 Cores=0
UNET D2 SolverType=PARDISO (Direct)
UNET D2 Minimum Iterations= 2147483647
UNET D2 Maximum Iterations= 2147483647
UNET D2 Restart Number= 10
UNET D2 Relaxation Coeff=1.3
UNET D2 SOR Precondition Iterations= 10
UNET D2 ILUT Maximum Fill= 8
UNET D2 ILUT Tolerance=1E-08
UNET D1D2 MaxIter= 0
UNET D1D2 ZTol=0.01
UNET D1D2 QTol=0.1
UNET D1D2 MinQTol=1
DSS File=dss
Write IC File= 0
Write IC File at Fixed DateTime=0
Write IC File at Sim End=0
Echo Input=False
Echo Parameters=False
Echo Output=False
Write Detailed= 0
HDF Write Warmup=0
HDF Write Time Slices=0
HDF Flush=0
HDF Compression= 1
HDF Chunk Size= 1
HDF Spatial Parts= 1
HDF Use Max Rows=0
HDF Fixed Rows= 1
Calibration Method= 0
Calibration Iterations= 20
Calibration Max Change=0.05
Calibration Tolerance=0.2
Calibration Maximum=1.5
Calibration Minimum=0.5
Calibration Optimization Method= 1
WQ AD Non Conservative
WQ ULTIMATE=-1
WQ Max Comp Step=1HOUR
WQ Output Interval=15MIN
WQ Output Selected Increments= 0
WQ Output face flow=0
WQ Output face velocity=0
WQ Output face area=0
WQ Output face dispersion=0
WQ Output cell volume=0
WQ Output cell surface area=0
WQ Output cell continuity=0
WQ Output cumulative cell continuity=0
WQ Output face conc=0
WQ Output face dconc_dx=0
WQ Output face courant=0
WQ Output face peclet=0
WQ Output face adv mass=0
WQ Output face disp mass=0
WQ Output cell mass=0
WQ Output cell source sink temp=0
WQ Output nsm pathways=0
WQ Output nsm derived pathways=0
WQ Create Restart=0
WQ Fixed Restart=0
WQ System Summary=0
WQ Write To DSS=0
Sorting and Armoring Iterations= 10
XS Update Threshold= 0.02
Bed Roughness Predictor= 0
Hydraulics Update Threshold= 0.02
Energy Slope Method= 1
Volume Change Method= 1
Sediment Retention Method= 0
Sediment TS Multiplier= 1
Warm Up Method= 0
XS Weighting Method= 0
Number of US Weighted Cross Sections= 1
Number of DS Weighted Cross Sections= 1
Upstream XS Weight=0
Main XS Weight=1
Downstream XS Weight=0
Number of DS XS's Weighted with US Boundary= 1
Upstream Boundary Weight= 1
Weight of XSs Associated with US Boundary= 0
Number of US XS's Weighted with DS Boundary= 1
Downstream Boundary Weight= 0.5
Weight of XSs Associated with DS Boundary= 0.5
Percentile Method= 0
Sediment Output Level= 3
Mass or Volume Output= 0
Output Increment Type= 1
Profile and TS Output Increment= 1
Transport Output Increment 1
XS Output Flag= 0
XS Output Increment= 10
Read HDF5 Sediment Hotstart= 0
Sediment Hotstart Type= 0
Write Gradation File= 0
Read Gradation Hotstart= 0
Write HDF5 File= 1
Write Binary Output= 1
Write DSS Sediment File= 0
DSS Sediment Output Type= 1
SV Curve= 0
Specific Gage Flag= 0
Subcell Erosion Methods= 0
Subcell Deposition Methods= 0
Advection Scheme= 1
Matrix Solver= 0
Implicit Weighting Factor= 1
Maximum Outer Loop Convergence Iterations= 5
Convergence Maximum Absolute= 0.001
Convergence RMSE= 0.0001
Grain Fractions Max Abs Error= 0.001
Max Subgrid Regions= 1
Max Subgrid Length Scale= 3.402823E+38
Initial Layer Thickness= 3.402823E+38
Min Layer Thickness= 3.402823E+38
Max Layer Thickness= 3.402823E+38
Number of Layers= 5

--- EFGRNBRRRV.f01 (steady flow) ---

Flow Title=Flow
Program Version=6.10
Number of Profiles= 7
Profile Names=01pct,FW,10pct,04pct,02pct,0_2pct,01plus
River Rch & RM=EFGRNBRRRV,Main            ,104542
     679     679     361     479     576     945    1000
River Rch & RM=EFGRNBRRRV,Main            ,100532
     906     906     488     643     770    1260    1340
River Rch & RM=EFGRNBRRRV,Main            ,98150
    1020    1020     549     722     865    1400    1500
River Rch & RM=EFGRNBRRRV,Main            ,95004
    1260    1260     684     896    1070    1730    1860
River Rch & RM=EFGRNBRRRV,Main            ,93506
    1460    1460     798    1040    1240    2000    2150
River Rch & RM=EFGRNBRRRV,Main            ,87900
    1710    1710     943    1230    1460    2340    2530
River Rch & RM=EFGRNBRRRV,Main            ,80697
    2120    2120    1180    1530    1810    2880    3130
River Rch & RM=EFGRNBRRRV,Main            ,75794
    2570    2570    1440    1860    2200    3490    3800
River Rch & RM=EFGRNBRRRV,Main            ,72661
    3060    3060    1720    2220    2630    4140    4520
River Rch & RM=EFGRNBRRRV,Main            ,70843
    3420    3420    1930    2490    2940    4610    5050
River Rch & RM=EFGRNBRRRV,Main            ,60163
    3870    3870    2200    2830    3330    5220    5720
River Rch & RM=EFGRNBRRRV,Main            ,47903
    5060    5060    2910    3720    4370    6790    7490
River Rch & RM=EFGRNBRRRV,Main            ,44536
    5630    5630    3250    4140    4860    7540    8330
River Rch & RM=EFGRNBRRRV,Main            ,34384
   13300   13300    4610    7020    9710   28600   17300
River Rch & RM=EFGRNBRRRV,Main            ,24278
   14800   14800    5110    7780   10700   31500   19100
River Rch & RM=EFGRNBRRRV,Main            ,0
   23900   23900    8850   12800   17500   49800   31000
Boundary for River Rch & Prof#=EFGRNBRRRV,Main            , 1
Up Type= 0
Dn Type= 1
Dn Known WS=2714.4
Boundary for River Rch & Prof#=EFGRNBRRRV,Main            , 2
Up Type= 0
Dn Type= 1
Dn Known WS=2715.3
Boundary for River Rch & Prof#=EFGRNBRRRV,Main            , 3
Up Type= 0
Dn Type= 1
Dn Known WS=2708.5
Boundary for River Rch & Prof#=EFGRNBRRRV,Main            , 4
Up Type= 0
Dn Type= 1
Dn Known WS=2710.7
Boundary for River Rch & Prof#=EFGRNBRRRV,Main            , 5
Up Type= 0
Dn Type= 1
Dn Known WS=2712.3
Boundary for River Rch & Prof#=EFGRNBRRRV,Main            , 6
Up Type= 0
Dn Type= 1
Dn Known WS=2721.4
Boundary for River Rch & Prof#=EFGRNBRRRV,Main            , 7
Up Type= 0
Dn Type= 1
Dn Known WS=2716.6
DSS Import GetInterval= 0
DSS Import GetPeak= 0
DSS Import FillOption= 0

--- EFGRNBRRRV.g01 (geometry) ---

Geom Title=Geometry
Program Version=6.10

River Reach=EFGRNBRRRV      ,Main
Reach XY= 30
2350802.35242589611844.770913571     2353732.824609848.959000021
2352947.09923665 604287.853041532351015.97800002602658.040000007
2350910.57490124599107.6423586912349852.21147987598959.700607449
2348804.88899998       594986.752346457.70111373593170.757111013
2346749.32368125591972.4592601662342766.98499998593457.275999993
2341463.70999999590115.8939999942339103.49400002590079.709000006
2339219.21799999586994.3200000082340781.04400003586452.021000013
2339480.39399998 584451.564000012340579.21307181580976.493580431
2338433.92500003577640.357999995 2333933.6400253574986.702568948
2333619.27200001573035.0600000172331615.81700002572157.705000013
2329730.82099999569107.3920000052327051.32600003568768.172000021
2323565.89599998565835.2700000112322410.84299999566195.925000012
2319441.64552817 562671.000884982316267.24999999562546.716000021
2312007.93200001564265.7080000042310187.49800003563741.026000008
2307211.92900005565130.810000017 2302406.0692099564212.313626632

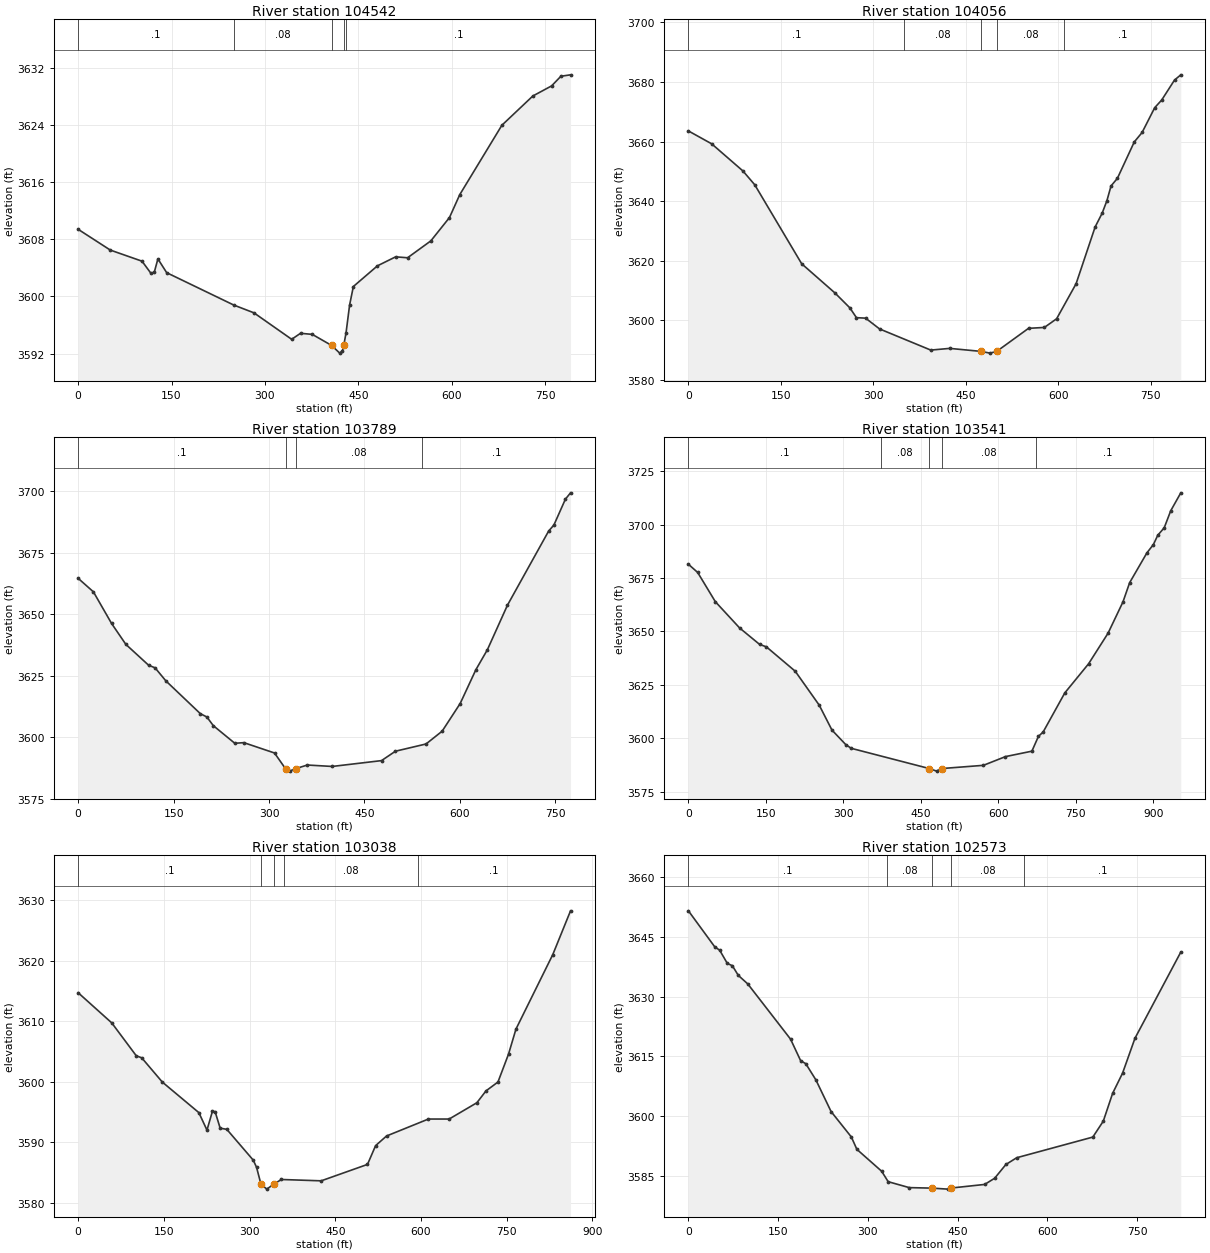
Type RM Length L Ch R = 1 ,104542  ,486.2,486.2,486.2
XS GIS Cut Line= 3
2351109.19115125  612117.15438522350672.62263982611703.509639824
2350584.92440588611535.406390643
#Sta/Elev= 30
       0 3609.42    51.6 3606.51   102.6 3604.95   117.1 3603.23   122.4 3603.44
   128.1 3605.27   142.2 3603.34     250  3598.8   282.4 3597.71     343    3594
   357.2 3594.84   376.1 3594.69   407.1 3593.14   420.2 3592.06   424.5 3592.36
  426.683593.146   430.3 3594.87   436.1 3598.82   442.1  3601.4   480.8  3604.3
     510 3605.56   529.2 3605.43   566.6  3607.8   596.5 3611.07   613.1 3614.29
   680.7 3624.01   730.4 3628.11   760.6 3629.53   775.5 3630.88     791 3631.08
#Mann= 5 ,-1,0
       0      .1       0     250     .08       0   407.1    .045       0
  426.68     .08       0   430.3      .1       0
Bank Sta=407.1,426.68
XS Rating Curve= 0 ,0
Exp/Cntr=0.3,0.1

Type RM Length L Ch R = 1 ,104056  ,258.8,266.4,270
XS GIS Cut Line= 2
2351496.78244505611812.9564004332350876.23633297 611309.65002394
#Sta/Elev= 30
       0 3663.57    37.7 3659.25    88.4 3650.15   107.6 3645.51   183.8 3618.99
   237.7 3609.21   261.9 3604.21   272.7  3600.9   287.5 3600.74   310.2 3597.12
   393.3 3590.02     424 3590.59   474.6 3589.59   489.4    3589   500.4  3589.6
   551.9 3597.32   577.6 3597.62   597.5 3600.53   629.1 3612.29     660 3631.35
   671.4 3635.97   679.1 3640.16   685.8 3645.11   696.1 3647.66   723.5 3659.88
   736.2 3663.05   756.7 3671.38     768 3673.94   788.8 3680.64     799  3682.4
#Mann= 5 ,-1,0
       0      .1       0     350     .08       0   474.6    .045       0
   500.4     .08       0     610      .1       0
Bank Sta=474.6,500.4
XS Rating Curve= 0 ,0
Exp/Cntr=0.3,0.1

Type RM Length L Ch R = 1 ,103789  ,242.6,248,250.7
XS GIS Cut Line= 3
2351534.91481981611716.140735413 2351373.7705807611511.331605708
 2350990.1433276611170.329602949
#Sta/Elev= 30
       0  3664.6      24  3659.1    52.5 3646.27      75 3637.76   110.7 3629.31
   120.9 3628.24   137.9 3622.93     192 3609.63   202.3 3608.27   212.4 3604.76
   246.2 3597.59   260.4 3597.85   308.6 3593.65  325.93 3587.25   332.3 3586.28
   342.1  3587.3   360.2 3588.76   399.3 3588.18   476.8 3590.55   498.7 3594.37
   546.8 3597.31   572.1 3602.51   600.4 3613.73   625.1 3627.47   643.2 3635.59
   674.8 3653.72   739.5 3683.81   747.8 3686.27   765.8 3696.75   773.9 3699.33
#Mann= 4 ,-1,0
       0      .1       0  325.93    .045       0   342.1     .08       0
   540.6      .1       0
Bank Sta=325.93,342.1
XS Rating Curve= 0 ,0
Exp/Cntr(USF)=0,0
Exp/Cntr=0.3,0.1

Type RM Length L Ch R = 1 ,103541  ,484.2,503.5,505.3
XS GIS Cut Line= 4
2351686.55873667611669.8556452672351592.79240508611424.956230973
2351311.81754545611106.0117957122351057.50530032611027.963051144
#Sta/Elev= 30
       0 3681.45    17.9 3677.62    52.1 3663.94    99.2 3651.61   137.8 3643.94
     151 3642.79   206.8 3631.38   253.3 3615.48   277.9 3603.84   304.6 3597.05
   315.2  3595.3   466.6 3585.81   480.5 3584.62  490.223585.826   571.1 3587.33
   613.9 3591.42     665 3593.96   677.7 3600.91   686.8 3602.93   728.8 3621.26
   774.8 3634.87   812.5 3649.19   841.3 3663.81   854.3 3672.84   887.8 3686.82
   900.3 3690.69   908.7 3695.02   921.2 3698.51   933.8 3706.48   953.3 3714.88
#Mann= 5 ,-1,0
       0      .1       0  372.24     .08       0   466.6    .045       0
  490.22     .08       0  672.24      .1       0
Bank Sta=466.6,490.22
XS Rating Curve= 0 ,0
Exp/Cntr=0.3,0.1

Type RM Length L Ch R = 1 ,103038  ,451.7,464.4,443.2
XS GIS Cut Line= 3
2351970.31232484611338.6270218352351675.32342421610881.240849171
     2351635.469      610566.437
#Sta/Elev= 30
       0 3614.71    58.8 3609.73   101.7  3604.3   111.2 3603.97   147.3 3599.96
   211.2 3594.92   225.4 3592.03     235 3595.16   239.7 3595.06   248.5 3592.35
   260.1 3592.16   306.5 3587.06   312.2 3585.88  319.84 3583.12   330.1 3582.29
  342.33 3583.11   355.6 3583.88   425.3 3583.66   506.3 3586.37   520.5 3589.47
   539.6 3591.06   612.9 3593.86   649.2 3593.86   697.7 3596.55   713.7 3598.51
   734.6 3599.97   753.1 3604.58   766.1 3608.71   830.6 3621.02   861.6 3628.23
#Mann= 5 ,-1,0
       0      .1       0  319.84    .045       0  342.33      .1       0
     360     .08       0  594.26      .1       0
Bank Sta=319.84,342.33
XS Rating Curve= 0 ,0
Exp/Cntr=0.3,0.1

Type RM Length L Ch R = 1 ,102573  ,400.9,407.4,403.2
XS GIS Cut Line= 4
2352288.74788262611246.6132793462352200.50845516610989.750153087
2352028.14162693 610687.789858962351975.80953503610491.085792543
#Sta/Elev= 30
       0 3651.56    43.8 3642.55    52.3 3641.65      65 3638.34    73.4 3637.77
    83.4 3635.33    99.2 3633.19   170.7 3619.31   187.6 3613.88   196.1 3613.15
     213 3609.08   238.4 3601.12   272.3 3594.72   281.5 3591.62   322.9 3586.12
   333.8 3583.49     369    3582   407.1 3581.87   433.5 3581.62   439.4  3581.9
   495.1  3582.8   511.8 3584.36   530.5 3587.81   548.6 3589.51   675.8  3594.7
   693.3 3598.71   708.9  3605.7   725.5 3610.77   746.2 3619.53   822.8 3641.19
#Mann= 5 ,-1,0
       0      .1       0   331.6     .08       0   407.1    .045       0
   439.4     .08       0   561.6      .1       0
Bank Sta=407.1,439.4
XS Rating Curve= 0 ,0
Exp/Cntr=0.3,0.1

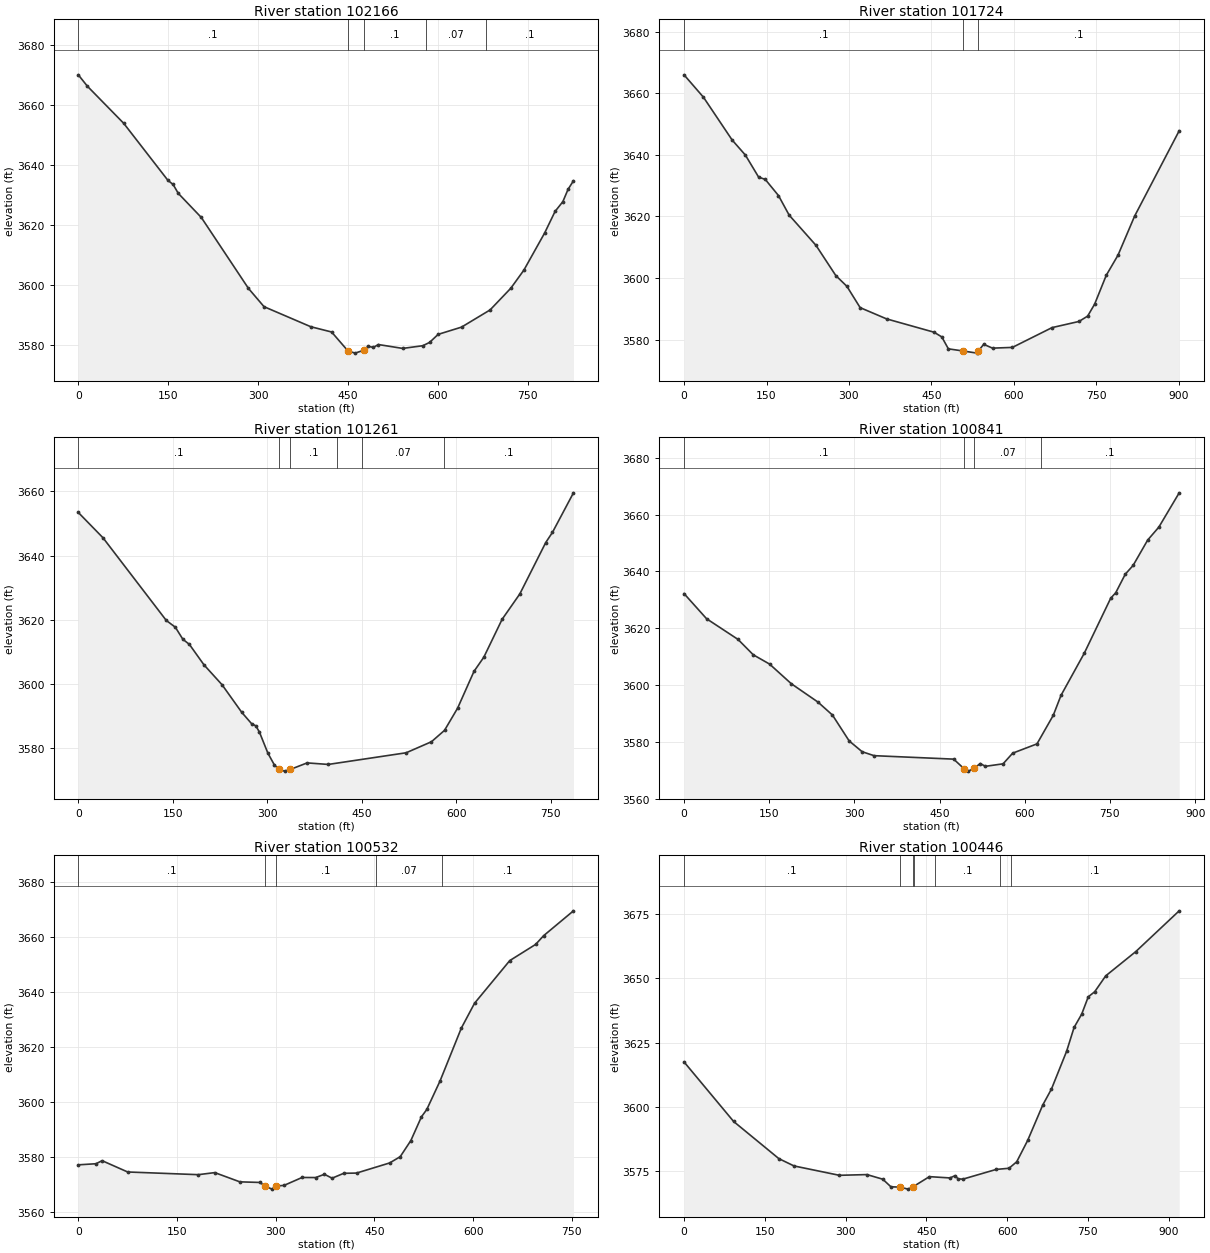
Type RM Length L Ch R = 1 ,102166  ,418.2,442.3,451
XS GIS Cut Line= 2
2352635.13507306611171.152805644 2352315.2263687610408.900834581
#Sta/Elev= 30
       0 3669.91    15.2 3666.11    75.9 3653.74   149.6 3634.77   158.3 3633.38
     167 3630.41   205.4 3622.39   284.1 3598.76   310.1 3592.68   388.2    3586
   422.9 3584.25   449.9 3578.02     462 3577.21   476.6 3578.15   483.7 3579.48
   492.7 3579.12     501 3580.07   541.6 3578.78   575.2 3579.68   586.5 3580.78
   600.8 3583.46   639.8 3585.87   687.5  3591.6   722.2 3598.85   743.9 3604.85
   778.6 3617.23     796 3624.41     809 3627.67   817.7 3631.78   826.7 3634.61
#Mann= 5 ,-1,0
       0      .1       0   449.9    .045       0   476.6      .1       0
     580     .07       0     680      .1       0
Bank Sta=449.9,476.6
XS Rating Curve= 0 ,0
Exp/Cntr=0.3,0.1

Type RM Length L Ch R = 1 ,101724  ,480.3,462.2,424.6
XS GIS Cut Line= 3
2352737.43997996611148.4153508552352796.03500408610424.441275127
2352737.43997996610260.375207606
#Sta/Elev= 30
       0 3666.04    35.4 3658.74    87.5 3644.85   111.6 3639.95   135.7 3632.78
   147.7 3632.05   171.8 3626.79   191.2 3620.43     240 3610.61   276.1 3600.77
   296.2 3597.29   320.3 3590.36   368.4  3586.7   454.7 3582.37   468.8 3580.84
   480.8 3576.96   506.7 3576.29     533 3575.57  535.433576.303     545 3578.43
   561.1 3577.19   597.2 3577.43   669.4 3583.87   718.4 3585.87   734.1 3587.61
   746.8 3591.49     768 3600.89   789.3 3607.41   819.5  3620.1   900.6 3647.86
#Mann= 3 ,-1,0
       0      .1       0   506.7    .045       0  535.43      .1       0
Bank Sta=506.7,535.43
XS Rating Curve= 0 ,0
Exp/Cntr(USF)=0,0
Exp/Cntr=0.3,0.1

Type RM Length L Ch R = 1 ,101261  ,422.2,420.3,413.3
XS GIS Cut Line= 2
2353357.24512393610789.0325362852352855.93213984610183.550620433
#Sta/Elev= 30
       0 3653.45    39.3 3645.52   139.7 3619.73   154.1 3617.61     166 3613.86
   176.4 3612.25   199.5 3605.88   228.3 3599.64   259.5 3591.04     275 3587.53
   281.9 3586.81   287.6 3584.86     301 3578.29   311.4 3574.58   318.8 3573.23
   327.4 3572.69   336.83573.238   363.3 3575.26   396.8 3574.78   520.5 3578.42
   560.7 3581.87   581.4 3585.42   602.2 3592.36   628.2 3603.84   643.8 3608.26
   672.8 3620.08   700.9    3628   742.1 3644.06   752.8 3647.25   786.1 3659.58
#Mann= 6 ,-1,0
       0      .1       0   318.8    .045       0   336.8      .1       0
     410     .08       0     450     .07       0     580      .1       0
Bank Sta=318.8,336.8
XS Rating Curve= 0 ,0
Exp/Cntr(USF)=0,0
Exp/Cntr=0.3,0.1

Type RM Length L Ch R = 1 ,100841  ,298.6,309.4,317
XS GIS Cut Line= 4
     2353659.525      610614.4432353562.97876415610352.825134542
2353280.42053676610118.4450380832353073.96616952610026.605762237
#Sta/Elev= 30
       0 3632.22    39.7 3623.37    95.1 3616.09   121.9 3610.68   150.6 3607.42
   188.9  3600.5   235.8 3594.05   261.4 3589.47   290.8 3580.37   313.7 3576.57
   334.6 3575.19   474.8 3573.97   492.7 3570.67   500.8 3569.75   510.7 3570.73
   521.6 3572.43   530.6 3571.44   561.8 3572.32   578.7 3576.07   621.5 3579.34
   650.2  3589.4   663.8 3596.41   704.7 3611.21   751.3 3630.59   760.1  3632.5
     777 3639.05   790.7 3642.11   816.4 3651.05   836.1 3655.61   871.9 3667.67
#Mann= 4 ,-1,0
       0      .1       0   492.7    .045       0   510.7     .07       0
  628.86      .1       0
Bank Sta=492.7,510.7
XS Rating Curve= 0 ,0
Exp/Cntr=0.3,0.1

Type RM Length L Ch R = 1 ,100532  ,100.2,86,71.7
XS GIS Cut Line= 5
2353715.21076811610243.7861113242353623.77917911610188.927157924
2353622.63628424610096.3526740612353514.06127231609900.917652573
2353187.19334163609857.487647798
#Sta/Elev= 30
       0 3576.99    26.9 3577.39    36.2  3578.5      75 3574.39   182.4 3573.41
   207.4 3574.16   245.5  3570.8   276.1 3570.58   283.4 3569.28   294.4 3568.15
   300.4 3569.28   312.7 3569.51   340.1 3572.39   360.8 3572.36     374 3573.55
   385.7 3572.13   403.4 3573.91   422.8 3573.99   473.1 3577.67   489.2 3579.95
   505.4 3585.83   521.5 3594.47   529.6 3597.13   549.8 3607.53   582.1 3626.74
   602.2 3635.79   655.7  3651.3     695 3657.19   707.1 3660.35   752.5 3669.41
#Mann= 5 ,-1,0
       0      .1       0   283.4    .045       0   300.4      .1       0
  452.78     .07       0  552.78      .1       0
Bank Sta=283.4,300.4
XS Rating Curve= 0 ,0
Exp/Cntr(USF)=0,0
Exp/Cntr=0.3,0.1

Type RM Length L Ch R = 1 ,100446  ,190.1,173,153
XS GIS Cut Line= 4
2354032.15095105609978.8998504892353696.07215023609998.828888353
 2353458.8098324609845.0015922152353159.95455824609816.602261878
#Sta/Elev= 30
       0  3617.5    92.1  3594.4   176.1 3579.99   204.3 3577.15   288.5 3573.52
   339.7  3573.8   369.1 3572.01   384.2 3569.06   401.4 3568.94   415.9 3568.16
   424.6 3568.99   455.7    3573   493.9  3572.5   503.4 3573.39   508.8 3572.18
   517.7 3572.02   579.7  3575.8   603.5 3576.25   617.8 3578.75   638.2 3587.05
   666.3 3600.82   682.4 3606.99   710.5 3621.62   724.4 3630.87   738.6 3636.06
   750.7 3642.74   762.7 3644.72   783.1 3650.87   839.1 3660.31   919.6  3676.1
#Mann= 7 ,-1,0
       0      .1       0   401.4    .045       0   424.6      .1       0
  426.67     .08       0  466.67      .1       0  586.67     .07       0
  606.67      .1       0
Bank Sta=401.4,424.6
XS Rating Curve= 0 ,0
Exp/Cntr=0.3,0.1

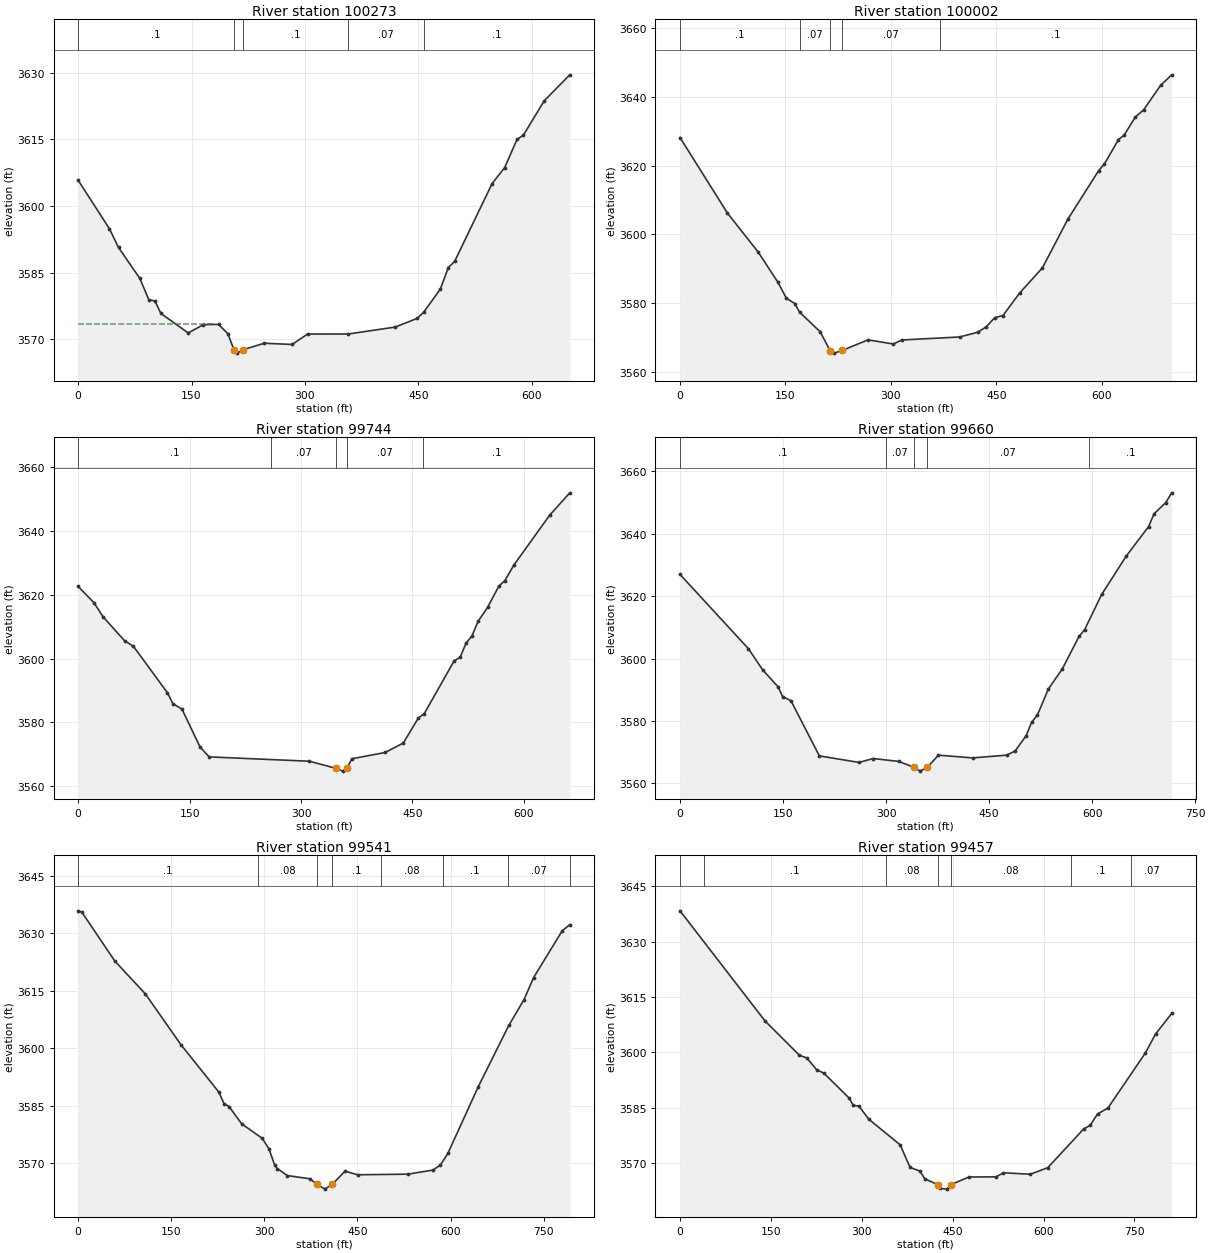
Type RM Length L Ch R = 1 ,100273  ,264.5,271.1,275.4
XS GIS Cut Line= 4
2353941.50395088609832.3439608232353766.64103692 609822.05790706
2353646.63707636609841.4871197232353304.91151247609751.198425585
#Sta/Elev= 30
       0 3605.81    41.4 3594.88    53.4 3590.68    81.5 3583.75    93.5 3578.92
   101.5 3578.65   109.5 3575.83   145.6 3571.45   165.6 3573.31   185.8 3573.37
   197.9 3571.29     206 3567.72   210.1 3566.91   218.4  3567.7   246.3 3569.13
     283 3568.86   303.4  3571.2   357.2 3571.21   419.3 3572.77   448.2 3574.71
   457.2 3576.15     479 3581.32   489.6 3586.17   497.9 3587.54   547.5 3605.06
   564.1 3608.66   580.4 3614.97   588.9 3615.95   616.4 3623.68   650.2 3629.51
#Mann= 5 ,-1,0
       0      .1       0     206    .045       0   218.4      .1       0
   357.2     .07       0   457.2      .1       0
#XS Ineff= 2 , 0
           181.7  3573.4
Permanent Ineff=
       F       F
Bank Sta=206,218.4
XS Rating Curve= 0 ,0
Exp/Cntr(USF)=0,0
Exp/Cntr=0.3,0.1

Type RM Length L Ch R = 1 ,100002  ,253.8,257.3,261.7
XS GIS Cut Line= 2
2353955.44868989609591.9052232942353256.49391729609569.864320472
#Sta/Elev= 30
       0 3628.15    67.3 3606.23   111.3 3594.84   139.3 3586.08   151.3 3581.44
   163.4 3579.89     170 3577.43   199.4 3571.68   213.4 3566.26   219.4  3565.5
   230.8 3566.29   267.4 3569.36   303.4 3568.15   315.4 3569.32   397.7 3570.19
   423.5 3571.58   435.5 3573.13   447.5 3575.79   459.3 3576.41     483 3582.96
   515.5 3590.29   551.5 3604.38   595.5 3618.56   603.6 3620.46   623.6 3627.55
   631.6 3628.84   647.6 3634.09   659.6 3636.25   683.6 3643.33   699.3 3646.37
#Mann= 5 ,-1,0
       0      .1       0     170     .07       0   213.4    .045       0
   230.8     .07       0     370      .1       0
Bank Sta=213.4,230.8
XS Rating Curve= 0 ,0
Exp/Cntr=0.3,0.1

Type RM Length L Ch R = 1 ,99744   ,83,84.3,84.6
XS GIS Cut Line= 3
 2353941.1597024609449.9193497782353515.08835594609363.179992893
2353289.18475614609384.149947305
#Sta/Elev= 30
       0 3622.59    21.4 3617.47    33.7 3613.05    62.5 3605.59    74.5 3603.83
   120.2  3589.3   127.5 3585.91   139.8 3584.17   164.1 3572.29   176.5 3569.22
   311.2 3567.86  346.44 3565.67   356.1 3564.76  361.75  3565.7   368.4 3568.63
   413.3  3570.6   437.7 3573.58   457.8 3581.38   465.9 3582.79     506 3599.27
   514.1 3600.39   522.1 3604.84   530.1 3607.13   538.2 3611.64     551 3616.01
   566.3 3622.71   574.3 3624.41   586.4 3629.28   634.6  3644.9   661.7 3651.91
#Mann= 5 ,-1,0
       0      .1       0     260     .07       0  346.44    .045       0
  361.75     .07       0  464.81      .1       0
Bank Sta=346.44,361.75
XS Rating Curve= 0 ,0
Exp/Cntr(USF)=0,0
Exp/Cntr=0.3,0.1

Type RM Length L Ch R = 1 ,99660   ,122.9,119.5,114.5
XS GIS Cut Line= 3
2353972.61463401 609394.634924512353502.69701925609273.581096771
2353274.88705995609309.801927118
#Sta/Elev= 30
       0 3626.99    99.6 3603.19   120.2 3596.45   142.8 3590.95   149.4 3587.83
   161.5 3586.52   202.9 3568.83   260.7 3566.74   281.3 3567.99   318.5 3567.06
   341.3 3565.13   349.7 3563.95   359.9 3565.13   376.3 3569.07   425.9 3568.19
   475.5 3569.07   487.8 3570.38     504 3575.31   512.1 3579.68   520.2 3581.83
   536.4  3590.3   556.7 3596.72     581 3607.14   589.1 3609.25     614  3620.6
   649.8 3632.88   682.2  3642.3   690.3 3646.44   707.3 3650.02   715.9 3653.14
#Mann= 5 ,-1,0
       0      .1       0     300     .07       0   341.3    .045       0
   359.9     .07       0  595.26      .1       0
Bank Sta=341.3,359.9
XS Rating Curve= 0 ,0
Exp/Cntr(USF)=0,0
Exp/Cntr=0.3,0.1

Type RM Length L Ch R = 1 ,99541   ,82.1,83,84.4
XS GIS Cut Line= 4
2354066.02624912609276.4406360092353755.28965193 609209.71805379
2353474.10162687609169.684504458 2353288.2315764609210.671233536
#Sta/Elev= 30
       0 3635.86       6 3635.52    59.2 3622.75   108.3 3614.22   165.5    3601
   226.9 3588.58   235.1 3585.59   243.3 3584.82   263.6 3580.33   296.5 3576.58
   307.4 3573.84   316.9 3569.49     321 3568.68   337.1 3566.85   373.5 3566.02
   384.7 3564.56   397.7 3563.32   409.5 3564.59   430.1 3568.01   450.3 3567.06
   531.1 3567.22   571.5 3568.28   583.6 3569.57   595.7 3572.62   644.8 3590.04
   693.9 3605.98   718.5 3612.74   733.9 3618.46   779.9 3630.64   792.2 3632.26
#Mann= 8 ,-1,0
       0      .1       0     290     .08       0   384.7    .045       0
   409.5      .1       0  487.82     .08       0  587.82      .1       0
  691.84     .07       0  791.84      .1       0
Bank Sta=384.7,409.5
XS Rating Curve= 0 ,0
Exp/Cntr(USF)=0,0
Exp/Cntr=0.3,0.1

Type RM Length L Ch R = 1 ,99457   ,336.2,307.2,275.9
XS GIS Cut Line= 3
2354122.26385413609191.6076386162353506.50973823609084.851507066
2353326.35876624609133.463674111
#Sta/Elev= 30
       0  3638.4   140.1 3608.59     197 3599.25   209.2 3598.53   225.3 3595.36
   237.6 3594.38   278.2 3587.79   286.3 3585.64   295.2 3585.47   311.8 3581.88
   363.4 3574.96   379.7 3568.84   395.9 3567.86     404 3565.75     426 3564.16
   429.5 3563.18   440.6 3562.96   446.8 3564.16   477.1 3566.25   521.8 3566.29
   533.9  3567.4   578.2 3566.99     607 3568.78   666.3 3579.29   677.1 3580.28
   689.1 3583.33   706.1 3584.91   768.2 3599.89   784.8 3604.99   811.5 3610.57
#Mann= 7 ,-1,0
       0     .12       0      40      .1       0     340     .08       0
     426    .045       0   446.8     .08       0  644.94      .1       0
  744.94     .07       0
Bank Sta=426,446.8
XS Rating Curve= 0 ,0
Exp/Cntr(USF)=0,0
Exp/Cntr=0.3,0.1

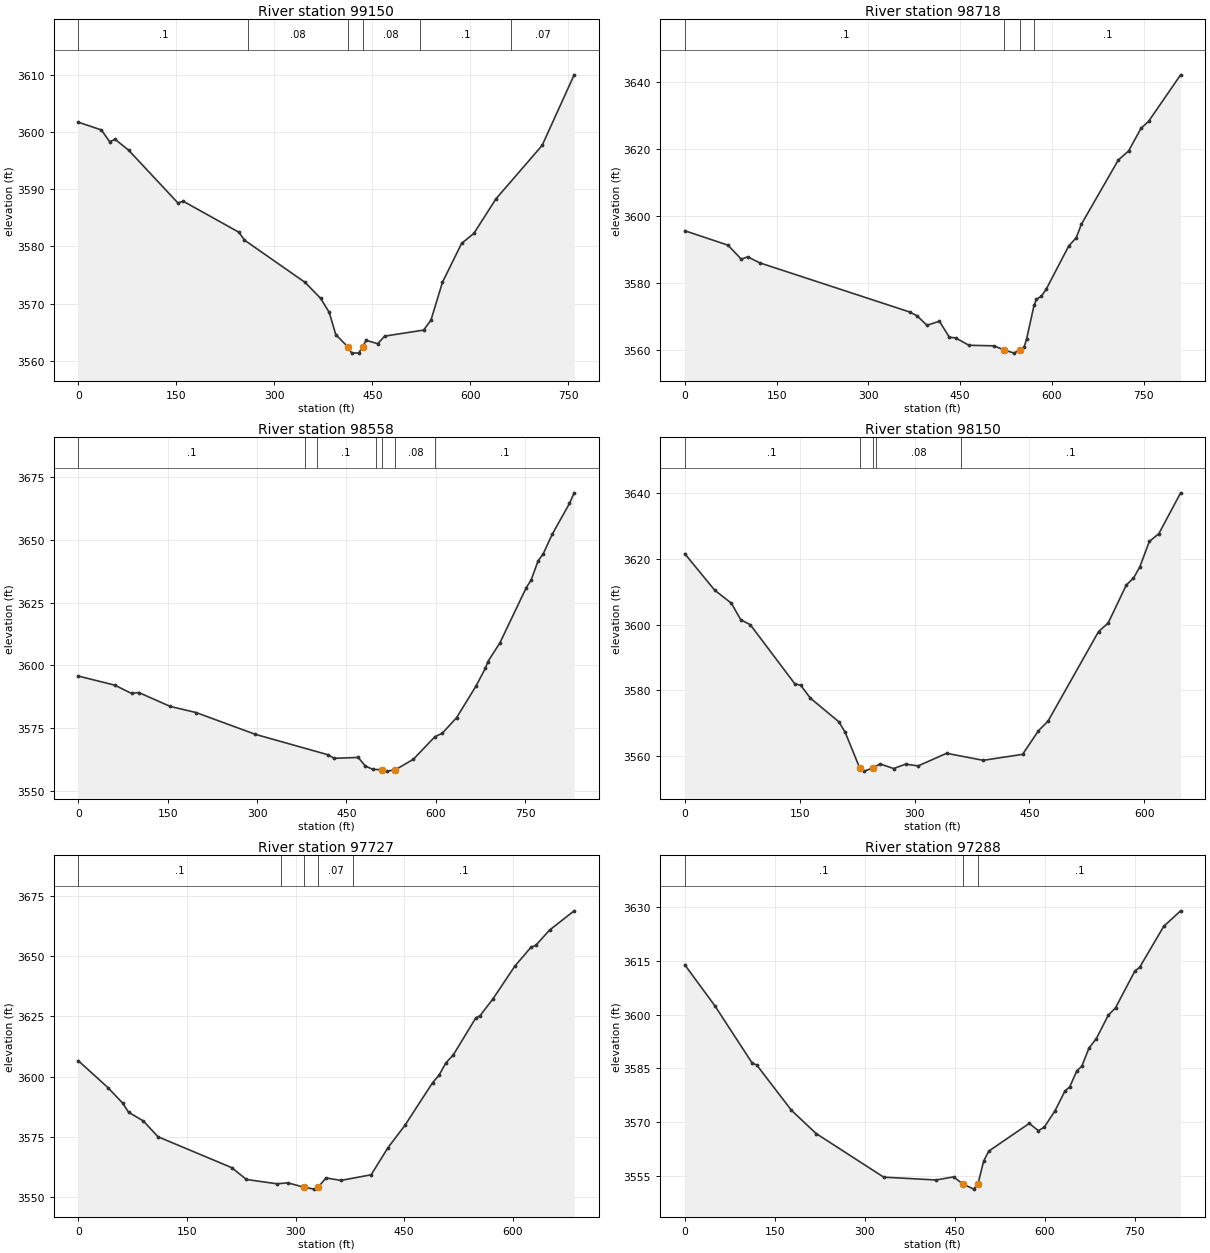
Type RM Length L Ch R = 1 ,99150   ,392,432.7,458.5
XS GIS Cut Line= 3
2353934.08058355608718.6750175662353625.48012321608811.124944503
 2353325.9944444609128.840186369
#Sta/Elev= 30
       0 3601.69    35.4 3600.33    47.9 3598.28    56.3  3598.7    77.2 3596.78
   152.3  3587.6   160.7 3587.88   245.7 3582.48   254.2 3581.11     347 3573.72
   370.7 3570.95     384 3568.47     394  3564.6   412.2  3562.5   418.4 3561.37
   429.2 3561.41   434.9 3562.46   434.9 3562.47   434.9 3562.48   440.5  3563.6
   458.2 3563.02   468.8 3564.34   528.4 3565.39   539.6 3567.12   557.3 3573.76
   586.5 3580.52   605.3 3582.27     639 3588.29   709.8 3597.64   758.8 3609.96
#Mann= 6 ,-1,0
       0      .1       0     260     .08       0   412.2    .045       0
   434.9     .08       0  522.15      .1       0  662.15     .07       0
Bank Sta=412.2,434.9
XS Rating Curve= 0 ,0
Exp/Cntr(USF)=0,0
Exp/Cntr=0.3,0.1

Type RM Length L Ch R = 1 ,98718   ,163.3,160,157.8
XS GIS Cut Line= 3
2353854.65177308608585.8596295732353493.96684686608607.995527572
2353052.55099853608525.962493811
#Sta/Elev= 30
       0 3595.68    70.6 3591.36    92.3 3587.18   102.7 3587.88   122.5 3586.08
   367.3  3571.4   379.5 3570.26   395.7 3567.42   416.1 3568.62   432.4 3563.82
   442.5 3563.66   464.3 3561.44     505 3561.27  521.513560.077   538.1 3559.09
   547.2 3560.12   554.4 3560.83   558.5 3563.23   570.7 3573.35   574.7 3575.16
   582.9 3576.16     591 3578.33   627.6 3591.18   639.8  3593.6     648 3597.59
   708.4 3616.81   725.3 3619.54   745.6 3626.32   757.8 3628.35   810.3 3642.29
#Mann= 4 ,-1,0
       0      .1       0  521.51    .045       0   547.2     .08       0
  571.36      .1       0
Bank Sta=521.51,547.2
XS Rating Curve= 0 ,0
Exp/Cntr(USF)=0,0
Exp/Cntr=0.3,0.1

Type RM Length L Ch R = 1 ,98558   ,414.6,407.8,396.9
XS GIS Cut Line= 4
2353837.50051839608550.0159250942353567.77733084608561.444873719
2353430.62994734608431.1548593932353060.33201189608385.439064893
#Sta/Elev= 30
       0 3595.69    60.8 3592.09    89.4 3588.77   101.4 3589.13   154.1  3583.6
   197.5 3581.15     297 3572.46   418.4 3564.35   429.4 3562.89   469.7 3563.24
   481.8 3559.81   493.9 3558.54   510.3 3558.28     518 3557.78   532.23558.323
   562.4 3562.54   598.6 3571.53   610.7 3572.85   634.9 3579.11   667.2 3591.61
   683.3 3598.85   687.3 3601.42   707.5  3608.9   751.8 3630.95   759.9 3633.94
   771.9 3641.76     780 3644.31   795.3 3652.21   824.3 3664.51   832.2 3668.76
#Mann= 7 ,-1,0
       0      .1       0  379.97     .08       0  399.97      .1       0
  499.13     .08       0   510.3    .045       0   532.2     .08       0
  599.13      .1       0
Bank Sta=510.3,532.2
XS Rating Curve= 0 ,0
Exp/Cntr(USF)=0,0
Exp/Cntr=0.3,0.1

Type RM Length L Ch R = 1 ,98150   ,418.3,422.7,424.3
XS GIS Cut Line= 2
2353734.85750156607992.0967185442353108.54179935608156.162786065
#Sta/Elev= 30
       0 3621.53    39.1 3610.43    60.7 3606.51    73.1 3601.46    85.5 3599.95
   143.4 3582.05   151.6 3581.46     164  3577.6   201.3 3570.39   209.5 3567.18
  228.273556.431   234.3 3555.41   245.6 3556.37     255  3557.6   272.6  3556.2
   288.4 3557.54   304.6    3557   341.8 3560.83   389.7  3558.7   441.1 3560.52
   461.8 3567.72   474.2  3570.6   540.3 3597.88   552.7 3600.42   576.5 3612.03
   585.8 3614.11   594.1 3617.51   606.5 3625.27   618.9 3627.61   647.4 3640.06
#Mann= 5 ,-1,0
       0      .1       0  228.27    .045       0   245.6      .1       0
     250     .08       0     360      .1       0
Bank Sta=228.27,245.6
XS Rating Curve= 0 ,0
Exp/Cntr(USF)=0,0
Exp/Cntr=0.3,0.1

Type RM Length L Ch R = 1 ,97727   ,419.1,438.8,453.8
XS GIS Cut Line= 3
 2353564.2808758607700.4237096182353133.28192065607782.456743379
2352952.28840172607949.127034194
#Sta/Elev= 30
       0 3606.55    40.8 3595.42    61.2 3588.97    69.3  3585.2    89.7 3581.56
     110    3575   211.8 3562.17   232.2 3557.26   274.4 3555.46   289.2 3555.86
     312 3554.03   325.7 3553.25   331.1 3554.03   342.1 3557.91   362.5 3556.86
   404.4 3559.21   427.6 3570.43   451.1 3579.74   489.2  3597.4   498.1  3600.5
   507.7 3605.69   517.9 3608.98     549 3624.35   554.7 3625.19   572.7 3632.26
   602.8 3645.78   625.1 3653.65   631.7 3654.43   650.9 3660.81   684.8 3668.78
#Mann= 5 ,-1,0
       0      .1       0     280     .07       0     312    .045       0
   331.1     .07       0     380      .1       0
Bank Sta=312,331.1
XS Rating Curve= 0 ,0
Exp/Cntr(USF)=0,0
Exp/Cntr=0.3,0.1

Type RM Length L Ch R = 1 ,97288   ,342.7,315.9,284.1
XS GIS Cut Line= 4
2353536.93653121607411.3549239862353297.34798817  607469.9499481
2352984.84119289607376.1979095172352732.23153337607402.240142457
#Sta/Elev= 30
       0  3613.9    50.2 3602.46     112 3586.59   120.2  3585.9   177.9 3573.31
     219 3566.84   331.7 3554.67   419.1 3553.88   448.3 3554.75   463.4 3552.81
   481.7 3551.33   489.1 3552.88   498.4 3559.15   506.8 3561.92   574.4 3569.66
   589.7 3567.64   599.5 3568.62   617.4 3573.18   633.9 3578.68   641.9 3579.85
     654 3584.39   662.1  3585.6   674.1  3590.7   686.2 3593.27   706.3 3599.86
   718.3  3601.9   750.5 3612.14   758.6 3613.22   798.8 3624.65   826.9 3628.96
#Mann= 3 ,-1,0
       0      .1       0   463.4    .045       0   489.1      .1       0
Bank Sta=463.4,489.1
XS Rating Curve= 0 ,0
Exp/Cntr(USF)=0,0
Exp/Cntr=0.3,0.1