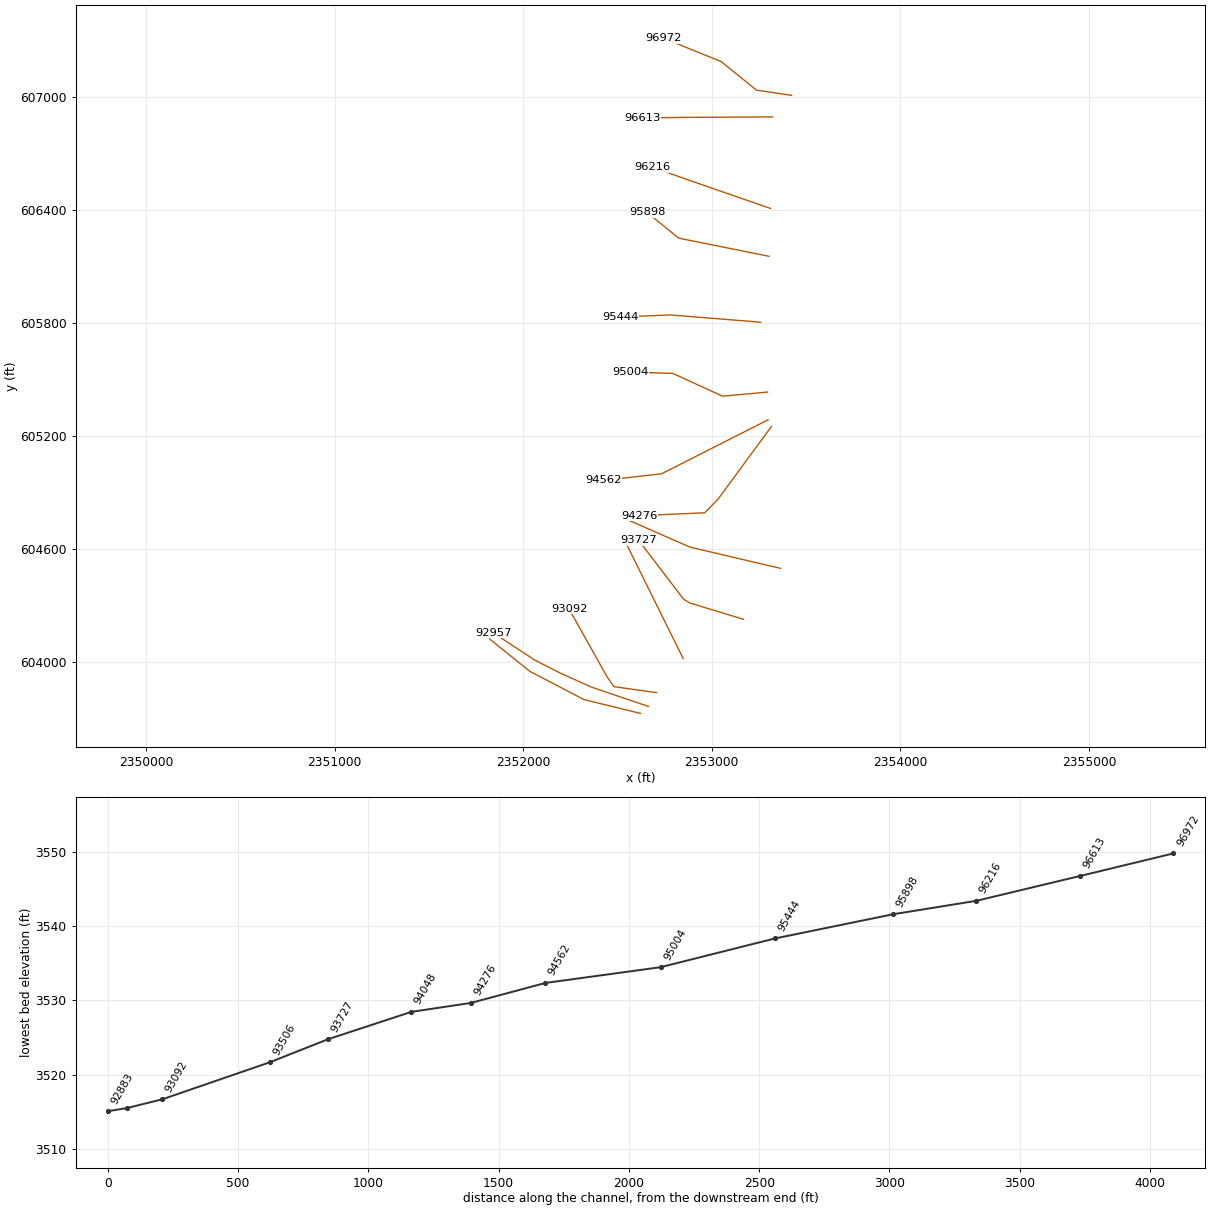
HEC-RAS study EFGRNBRRRV.prj: EFGRNBRRRV

--- EFGRNBRRRV.g01 (geometry) --- (continued)

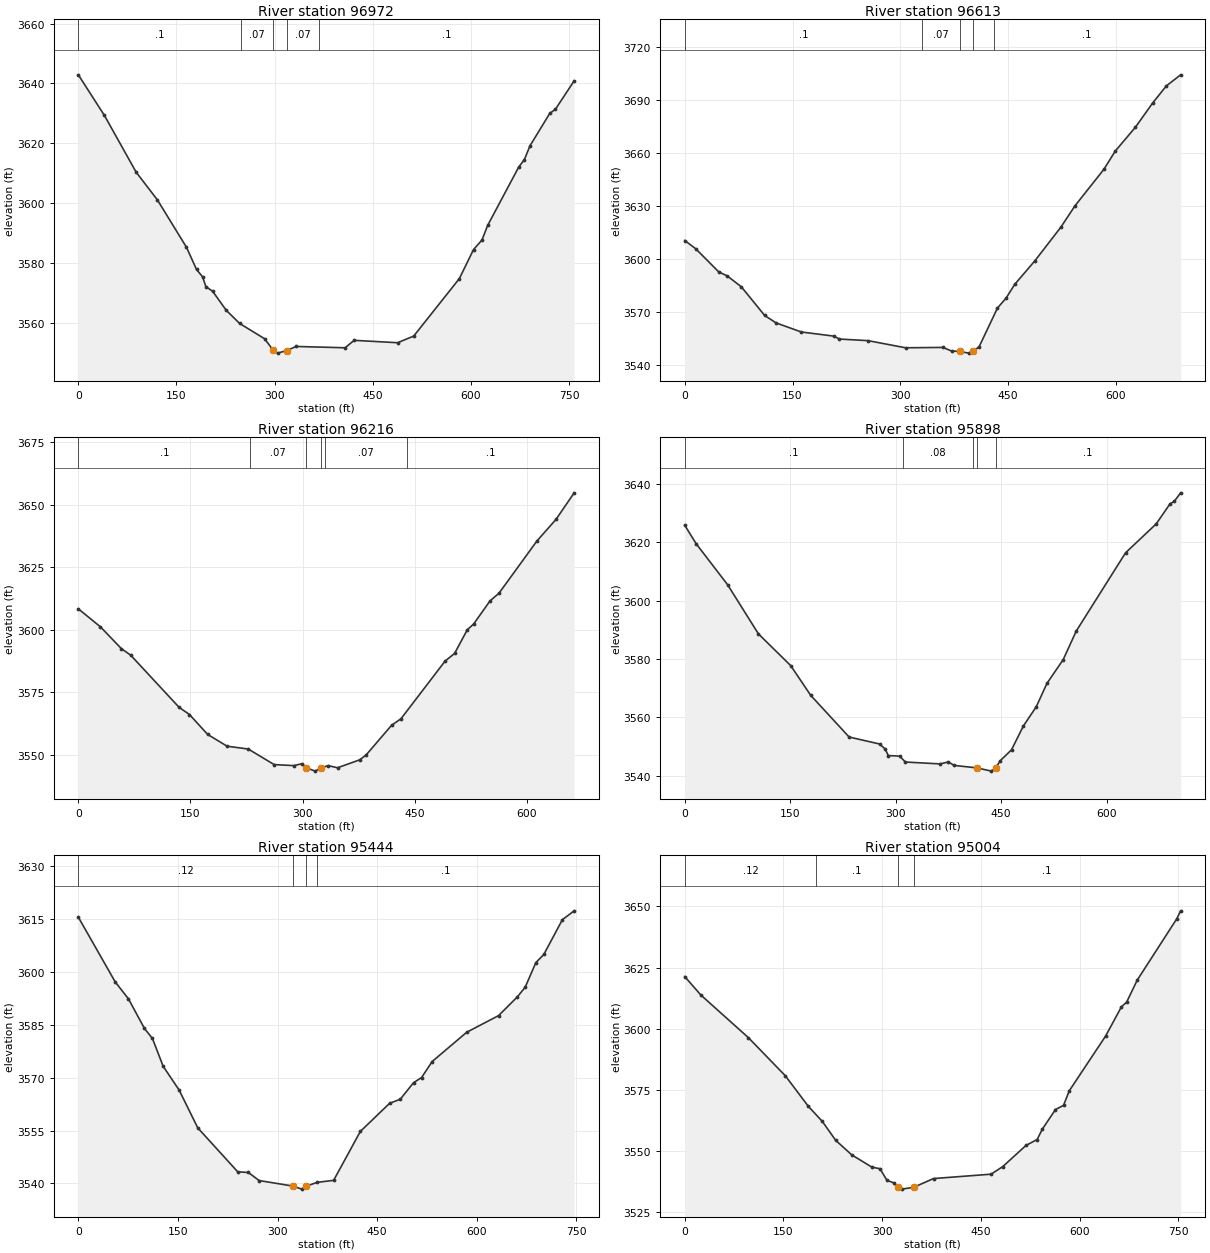
Type RM Length L Ch R = 1 ,96972   ,337.9,359.8,376.6
XS GIS Cut Line= 4
2353423.65281793607007.7003134182353237.45085241607035.044658005
2353050.43351483607186.504140585 2352745.6481647607309.964995177
#Sta/Elev= 30
       0 3642.87    39.9 3629.27    88.4  3610.3   120.8 3601.05   165.2 3585.22
   180.6 3577.78   189.8 3575.31     195 3572.02   205.3 3570.47   225.9 3564.15
   246.5 3559.71   284.5 3554.62   297.9 3550.73   304.4 3549.79   318.6 3550.65
   332.8 3552.02   407.7 3551.58   421.5 3554.07   487.9 3553.27   512.5 3555.49
   582.3 3574.73   603.9 3584.42   616.9 3587.65   625.5  3592.5     673 3612.03
   681.6  3614.5   690.2 3619.13   720.4 3629.97   729.1 3631.37   757.7 3640.86
#Mann= 5 ,-1,0
       0      .1       0   248.2     .07       0   297.9    .045       0
   318.6     .07       0   368.2      .1       0
Bank Sta=297.9,318.6
XS Rating Curve= 0 ,0
Exp/Cntr=0.3,0.1

Type RM Length L Ch R = 1 ,96613   ,406,396.9,385.3
XS GIS Cut Line= 3
2353323.39022111606893.1144884822352855.93213984606890.510265189
 2352633.2710482606887.906041894
#Sta/Elev= 30
       0 3610.54    15.2  3605.9    47.2 3592.79    59.2 3590.45    78.7 3584.33
   111.2 3568.07   127.2 3563.83   162.2 3558.72   207.2 3556.39   215.2 3554.72
   255.2 3553.81   307.2 3549.77   359.2 3549.97   371.2 3547.95   383.2 3547.67
   395.2 3546.74   400.9 3547.71   409.6 3550.33   435.2 3572.32   447.2 3577.93
   459.2 3585.72   487.2 3599.03   523.2 3618.01   543.2 3630.29   583.3 3650.92
   599.2 3661.27   627.2 3674.78   651.2 3688.49   670.2 3698.18   690.1 3704.46
#Mann= 5 ,-1,0
       0      .1       0     330     .07       0   383.2    .045       0
   400.9     .07       0     430      .1       0
Bank Sta=383.2,400.9
XS Rating Curve= 0 ,0
Exp/Cntr(USF)=0,0
Exp/Cntr=0.3,0.1

Type RM Length L Ch R = 1 ,96216   ,310.9,318.2,321.2
XS GIS Cut Line= 3
2353311.67121628606407.4268441542352891.08915431606553.263348617
2352685.35551408606626.181600849
#Sta/Elev= 30
       0 3608.36    29.3 3601.23    57.6 3592.44    70.1  3589.8   134.9 3568.92
   148.7 3566.07     173 3558.11     199 3553.39   227.3 3552.26     262 3546.03
     288 3545.62   299.6 3546.39  304.93 3544.75     317 3543.41   324.8 3544.71
   334.2 3545.62   346.8 3544.76   376.3 3547.91   384.7 3549.76   419.1 3561.75
   431.7 3564.37   490.7 3587.45   503.4  3590.5   520.4 3599.98   528.9 3602.28
   550.8 3611.53   562.8  3614.6   613.7 3635.56   639.2 3644.19   663.4 3654.79
#Mann= 6 ,-1,0
       0      .1       0     230     .07       0  304.93    .045       0
   324.8      .1       0     330     .07       0     440      .1       0
Bank Sta=304.93,324.8
XS Rating Curve= 0 ,0
Exp/Cntr(USF)=0,0
Exp/Cntr=0.3,0.1

Type RM Length L Ch R = 1 ,95898   ,445.3,453.9,456.9
XS GIS Cut Line= 3
 2353303.8585464606153.5150729912352824.68146031606249.871334868
2352656.70905785606386.593057802
#Sta/Elev= 30
       0 3625.89      16 3619.63    60.9 3605.52   104.8 3588.65   150.6 3577.81
   179.2 3567.58   233.8  3553.3   277.1 3550.91   285.3 3549.14   289.4 3546.95
   305.7 3546.75   313.8 3544.73   362.8 3544.09     375 3544.74   383.2 3543.57
   415.8 3542.72   436.2 3541.61  442.46 3542.74   448.5 3545.11   464.8 3548.92
   481.8 3557.14     500 3563.66   515.2 3571.68   538.4 3579.87   556.9 3589.63
   627.1 3616.48   670.6 3626.37   690.4 3633.28   696.2 3634.06   705.4 3637.03
#Mann= 5 ,-1,0
       0      .1       0     310     .08       0     410      .1       0
   415.8    .045       0  442.46      .1       0
Bank Sta=415.8,442.46
XS Rating Curve= 0 ,0
Exp/Cntr(USF)=0,0
Exp/Cntr=0.3,0.1

Type RM Length L Ch R = 1 ,95444   ,446.1,439.6,423.1
XS GIS Cut Line= 3
2353259.45725151605803.8576409442352781.71177596605842.310389359
2352514.49046588605831.974475526
#Sta/Elev= 30
       0  3615.6    55.5 3597.22    75.5 3592.39    99.6 3583.98   111.6 3581.14
   127.7 3573.27   151.8 3566.48   179.9 3555.74   240.1 3543.26   256.1 3543.08
   272.2 3540.79   323.7  3539.2   336.4 3538.35   342.5 3539.14     360 3540.28
   384.5 3540.85   424.7 3554.74   468.8 3562.73   484.8 3563.88   504.8 3568.58
   516.9 3570.04   532.9  3574.6   584.9 3582.91   632.9 3587.64     661 3592.93
     673 3595.72     689 3602.69     701    3605     729 3614.89   746.7  3617.4
#Mann= 4 ,-1,0
       0     .12       0   323.7    .045       0   342.5     .12       0
     360      .1       0
Bank Sta=323.7,342.5
XS Rating Curve= 0 ,0
Exp/Cntr=0.3,0.1

Type RM Length L Ch R = 1 ,95004   ,414.4,442,465.2
XS GIS Cut Line= 4
 2353296.3696313605433.2931839912353057.75944512605411.311434205
2352793.56448589605532.168820112  2352570.221694605539.763126116
#Sta/Elev= 30
       0 3621.34    24.3 3613.84    96.6 3596.41   152.8 3580.81   187.9 3568.28
   209.1 3562.13   229.2 3554.47   253.7 3548.49   284.5 3543.45   296.6 3542.83
   307.3 3538.07   317.7 3537.03   323.7 3535.27   329.7 3534.48   347.9 3535.22
     378  3538.8   465.6 3540.59   483.3  3543.7   518.5 3552.33   535.5 3554.76
   543.5 3559.04   563.4 3567.01   575.6  3568.7   584.4 3574.69   639.6 3597.05
   663.6 3608.98   671.6 3610.94   687.6 3619.89   747.7 3644.95   753.6 3648.23
#Mann= 4 ,-1,0
       0     .12       0     200      .1       0   323.7    .045       0
   347.9      .1       0
Bank Sta=323.7,347.9
XS Rating Curve= 0 ,0
Exp/Cntr=0.3,0.1

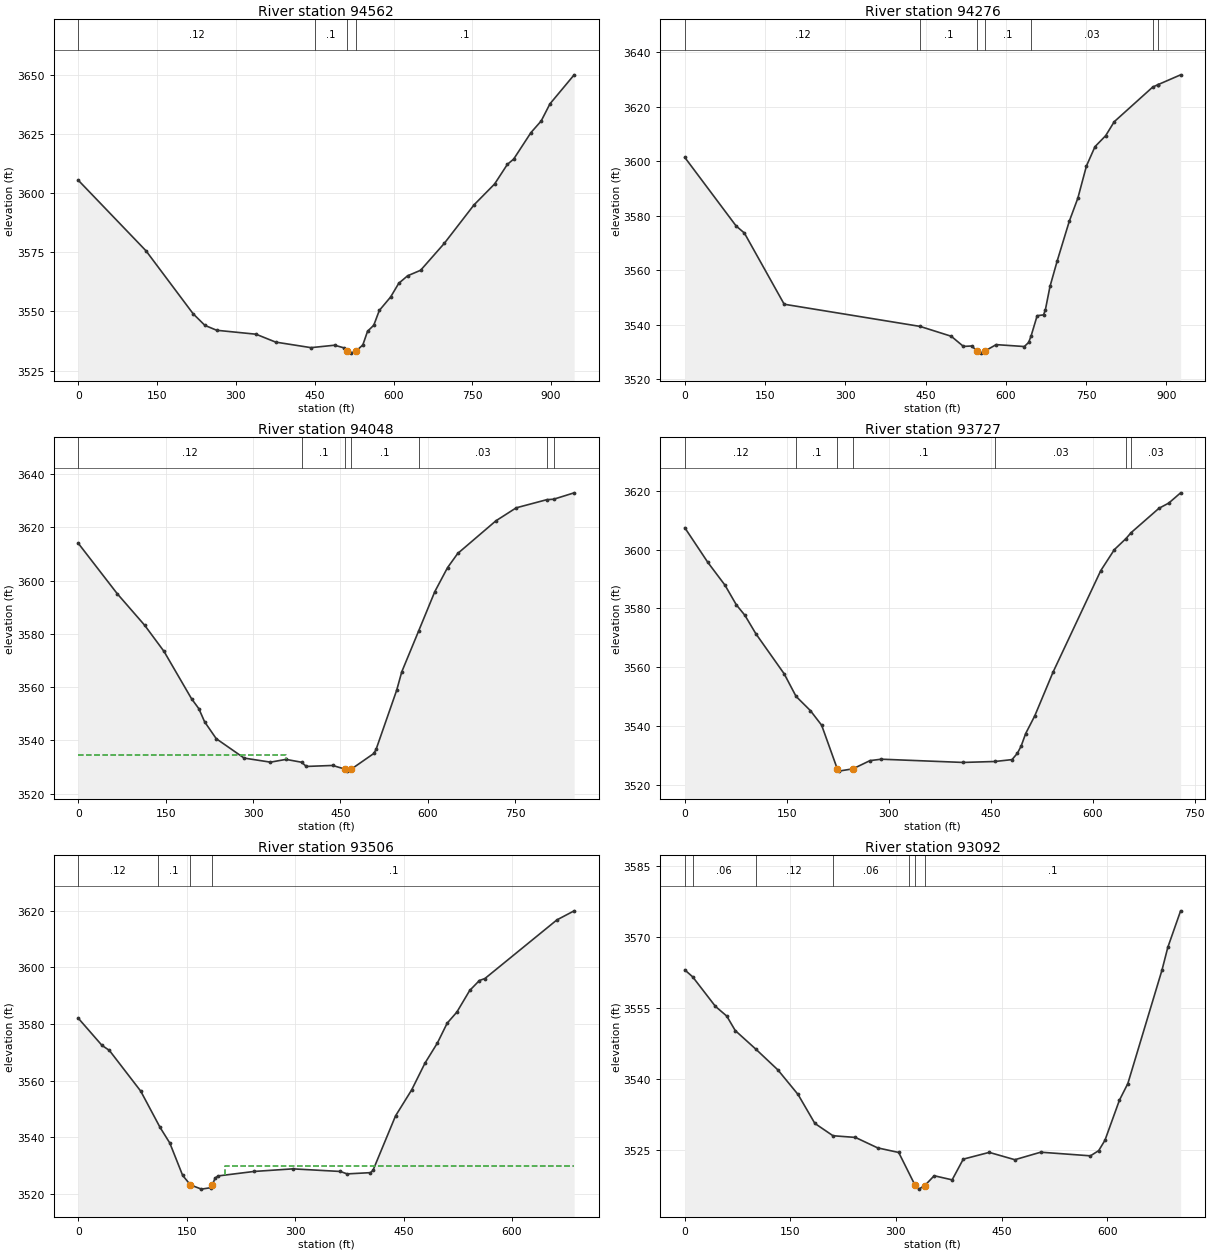
Type RM Length L Ch R = 1 ,94562   ,276.7,286,292.7
XS GIS Cut Line= 3
2353299.16242247605286.1920868132352734.83575667604999.844153755
2352425.78043694604964.519281169
#Sta/Elev= 30
       0 3605.51   128.9 3575.65   218.7 3548.98     241  3544.1   263.5 3542.03
   338.2 3540.37   375.6 3537.03   442.9 3534.68   487.8 3535.71   505.3 3534.62
   511.8 3533.06   519.2 3532.36   528.2 3533.15   541.6 3535.82   550.6 3541.62
   562.4 3544.16     573 3550.43   594.5 3556.12     610 3561.92   626.8 3565.09
   651.6 3567.43   696.5 3578.77   753.2 3595.09   792.5 3603.96   816.7 3612.24
   828.7 3614.47   861.6 3625.69   881.1 3630.61   897.8 3637.86   943.9 3650.15
#Mann= 4 ,-1,0
       0     .12       0     450      .1       0   511.8    .045       0
   528.2      .1       0
Bank Sta=511.8,528.2
XS Rating Curve= 0 ,0
Exp/Cntr=0.3,0.1

Type RM Length L Ch R = 1 ,94276   ,255.9,228.2,200.5
XS GIS Cut Line= 4
2353316.99676205605250.9581823512353033.34182901604864.622730564
2352962.74897237 604792.746367442352616.20222159604777.344289628
#Sta/Elev= 30
       0 3601.48      96 3576.31   111.4 3573.73   185.8 3547.61   439.7 3539.48
   498.1 3535.86   520.9 3532.13   536.3 3532.29   546.13530.499   553.3 3529.67
   561.7 3530.52   582.1 3532.79   634.7 3532.09   642.7 3533.57   647.3 3535.92
   658.7  3543.4   670.7 3543.71   674.1 3545.61   682.7 3554.13   696.3 3563.59
   718.7 3578.02   734.8 3586.55   750.8 3598.32   766.8 3605.42   786.8 3609.46
   802.8 3614.58   874.9 3627.32   884.9 3628.19   884.9  3628.2   926.9 3631.78
#Mann= 7 ,-1,0
       0     .12       0   439.7      .1       0   546.1    .045       0
   561.7      .1       0   647.3     .03       0   874.9      .1       0
   884.9     .03       0
Bank Sta=546.1,561.7
XS Rating Curve= 0 ,0
Exp/Cntr(USF)=0,0
Exp/Cntr=0.3,0.1

Type RM Length L Ch R = 1 ,94048   ,322.2,320.6,311.7
XS GIS Cut Line= 3
2353365.44243694604497.6862136482352884.57859607604610.512771304
2352557.01082011604754.215174345
#Sta/Elev= 30
       0 3614.03      67 3595.07   113.8  3583.3   147.1 3573.46   194.4 3555.68
     207 3551.92   216.9 3546.99   236.9 3540.65   284.8 3533.37     330 3531.84
   356.7 3532.88   383.4 3531.81   391.6 3530.23   436.8  3530.6   458.2 3529.21
   461.5 3528.47   468.7  3529.2   507.5  3535.1   511.4 3536.64   546.8 3558.87
   555.5 3565.77   584.3 3581.01   612.3 3595.91   634.1  3604.9   651.6 3610.23
   717.1 3622.48   752.1 3627.38   804.5 3630.43   816.4 3630.61   851.6 3633.01
#Mann= 7 ,-1,0
       0     .12       0   383.4      .1       0   458.2    .045       0
   468.7      .1       0   584.3     .03       0   804.5      .1       0
   816.4     .03       0
#XS Ineff= 2 , 0
           356.1 3534.46
Permanent Ineff=
       F       F
Bank Sta=458.2,468.7
XS Rating Curve= 0 ,0
Exp/Cntr=0.3,0.1

Type RM Length L Ch R = 1 ,93727   ,244.5,221.6,188.9
XS GIS Cut Line= 4
2353168.70928891604227.5017515682352885.63448155 604313.44735573
2352851.52908307604333.2284868472352612.79129374604646.316044867
#Sta/Elev= 30
       0  3607.4      34  3595.6    59.1  3587.9    75.8 3581.22    88.3  3577.7
   104.4 3571.45   146.1 3557.82   163.6 3550.15   184.6 3545.34   201.2 3540.37
  224.26 3525.51   226.3 3524.78   247.2 3525.56   272.3 3528.35     289 3528.83
     409 3527.73   455.9 3528.05   481.1 3528.69   488.9 3530.81   494.6 3533.32
   501.2 3537.55   514.6 3543.57   541.4 3558.37   611.6 3592.85   631.6 3599.98
   648.7 3603.73   656.2 3605.73   697.2 3614.01   711.5 3615.76     729 3619.25
#Mann= 7 ,-1,0
       0     .12       0   163.6      .1       0  224.26    .045       0
   247.2      .1       0   455.9     .03       0   648.7      .1       0
   656.2     .03       0
Bank Sta=224.26,247.2
XS Rating Curve= 0 ,0
Exp/Cntr(USF)=0,0
Exp/Cntr=0.3,0.1

Type RM Length L Ch R = 1 ,93506   ,410.3,413.3,415.6
XS GIS Cut Line= 2
2352848.43763612604019.8304458692352544.10661611604634.678169522
#Sta/Elev= 30
       0 3582.04    32.7 3572.47      43 3570.68    86.3 3556.32   113.1 3543.49
   126.5 3538.01   144.3 3526.57  155.053523.192   170.3  3521.7   183.3 3522.21
   185.53523.252   189.3 3525.63   193.4 3526.36     243 3527.94   296.8 3528.86
   362.4 3527.94   371.9 3527.08   404.2 3527.52   407.7 3528.35   438.9 3547.58
   461.2 3556.75   479.6  3566.2   496.8 3573.32   510.3 3580.31   523.7 3584.22
   541.5 3591.87   554.9 3595.38   562.5 3596.07   662.1 3616.78     686 3619.99
#Mann= 4 ,-1,0
       0     .12       0     110      .1       0  155.05    .045       0
   185.5      .1       0
#XS Ineff= 2 , 0
                          202.76         3529.94
Permanent Ineff=
       F       F
Bank Sta=155.05,185.5
XS Rating Curve= 0 ,0
Exp/Cntr=0.3,0.1

Type RM Length L Ch R = 1 ,93092   ,108.7,135.5,154.5
BEGIN DESCRIPTION:
strucure xs 4
END DESCRIPTION:
XS GIS Cut Line= 4
2352707.22382814603838.5881737532352481.68454892603870.197845462
 2352446.7621575603919.4478455632352243.25628899604282.606678276
#Sta/Elev= 30
       0 3563.06    11.2 3561.59    43.5 3555.35    59.6  3553.3    71.7 3550.23
   100.6 3546.35   132.3 3541.91   160.9 3536.72   184.8  3530.6   210.5    3528
   242.4 3527.64     274 3525.43   303.9 3524.46  327.25 3517.49   332.4 3516.71
     3413517.477   354.3 3519.54   379.8 3518.67   395.6 3523.05   432.5 3524.48
   468.9 3522.93   505.6 3524.52   576.3 3523.75     588 3524.85   596.9 3527.04
   617.5 3535.53   629.4 3539.03     678 3563.06   686.2 3567.83   704.4 3575.55
#Mann= 7 ,-1,0
       0     .12       0    11.2     .06       0   100.6     .12       0
   210.5     .06       0   317.9      .1       0  327.25    .045       0
     341      .1       0
Bank Sta=327.25,341
XS Rating Curve= 0 ,0
Exp/Cntr(USF)=0,0
Exp/Cntr=0.5,0.3

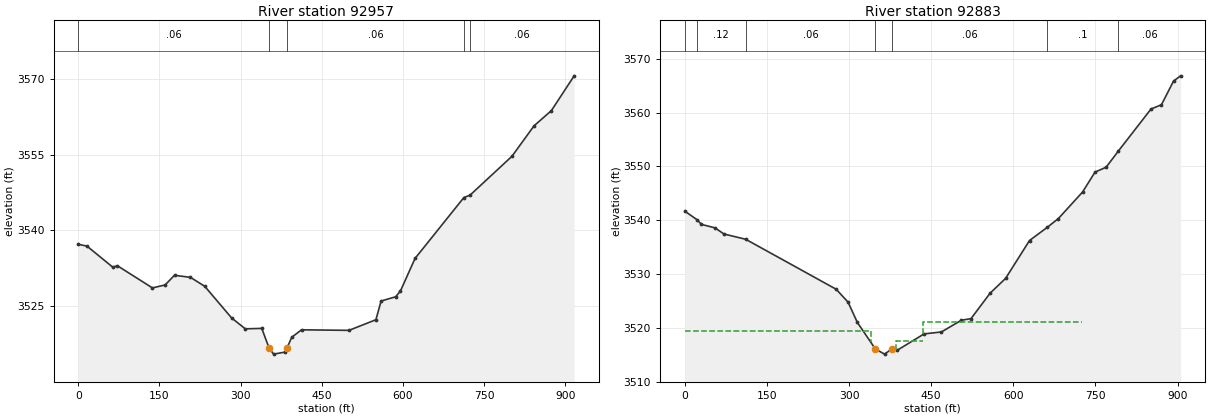
Type RM Length L Ch R = 1 ,92957   ,77.3,74.2,72.8
BEGIN DESCRIPTION:
structure xs 3
END DESCRIPTION:
XS GIS Cut Line= 5
2352664.50805556603765.1170449162352363.29598074603867.413274646
2352198.90613444603941.1060279442352061.36134673604011.159894975
2351841.00641404 604156.49900642
#Sta/Elev= 30
       0 3537.25    16.1 3536.88    63.7 3532.72    72.2 3533.01     137 3528.62
   160.4 3529.21   177.8 3531.12   207.3 3530.71   233.7 3528.94   283.4 3522.68
   308.7 3520.53   339.1 3520.62   352.6 3516.74     361 3515.53   382.3 3515.94
  386.08  3516.8   394.4 3518.85   412.6 3520.34   500.3 3520.23   550.1 3522.33
   559.7 3526.03   586.6 3526.87   595.4    3528   622.5 3534.46   712.7 3546.49
   724.2 3546.97   801.6 3554.65   842.6 3560.69   874.5 3563.68   916.6 3570.56
#Mann= 5 ,-1,0
       0     .06       0   352.6    .045       0  386.08     .06       0
   712.7      .1       0   724.2     .06       0
#XS Ineff= 2 , 0
             328  3519.9     410         3518.87
Permanent Ineff=
       F       F
Bank Sta=352.6,386.08
XS Rating Curve= 0 ,0
Exp/Cntr=0.5,0.3

Type RM Length L Ch R = 1 ,92883   ,205.5,202.7,198.3
BEGIN DESCRIPTION:
structure xs 2
END DESCRIPTION:
XS GIS Cut Line= 4
2352621.79228298603728.3814804982352321.92755947603801.852609335
2352035.73188319603951.3578133632351822.15302029604123.075219133
#Sta/Elev= 30
       0 3541.67    22.3 3540.09    30.5 3539.21    55.2 3538.57    71.5 3537.43
   111.2 3536.45   276.5 3527.16   298.2 3524.77   315.2 3520.99   348.1 3516.06
   364.9  3515.1   378.4 3516.08   387.4 3515.78   437.1 3518.86   468.7 3519.22
   505.2  3521.4   522.8  3521.7   557.8 3526.44     586 3529.18   629.7 3536.22
   661.9 3538.65   682.4  3540.3   726.5 3545.22   749.4 3548.94   769.6 3549.84
   791.9 3552.84   851.6 3560.66   870.7 3561.46   892.8 3565.86   905.7 3566.83
#Mann= 7 ,-1,0
       0     .06       0    22.3     .12       0   111.2     .06       0
   348.1    .045       0   378.4     .06       0   661.9      .1       0
   791.9     .06       0
#XS Ineff= 3 ,-1
       0     340  3519.4     386  435.49  3517.6  435.49  725.07 3521.01
Permanent Ineff=
       F       F       F
Bank Sta=348.1,378.4
XS Rating Curve= 0 ,0
Exp/Cntr(USF)=0,0
Exp/Cntr=0.5,0.3