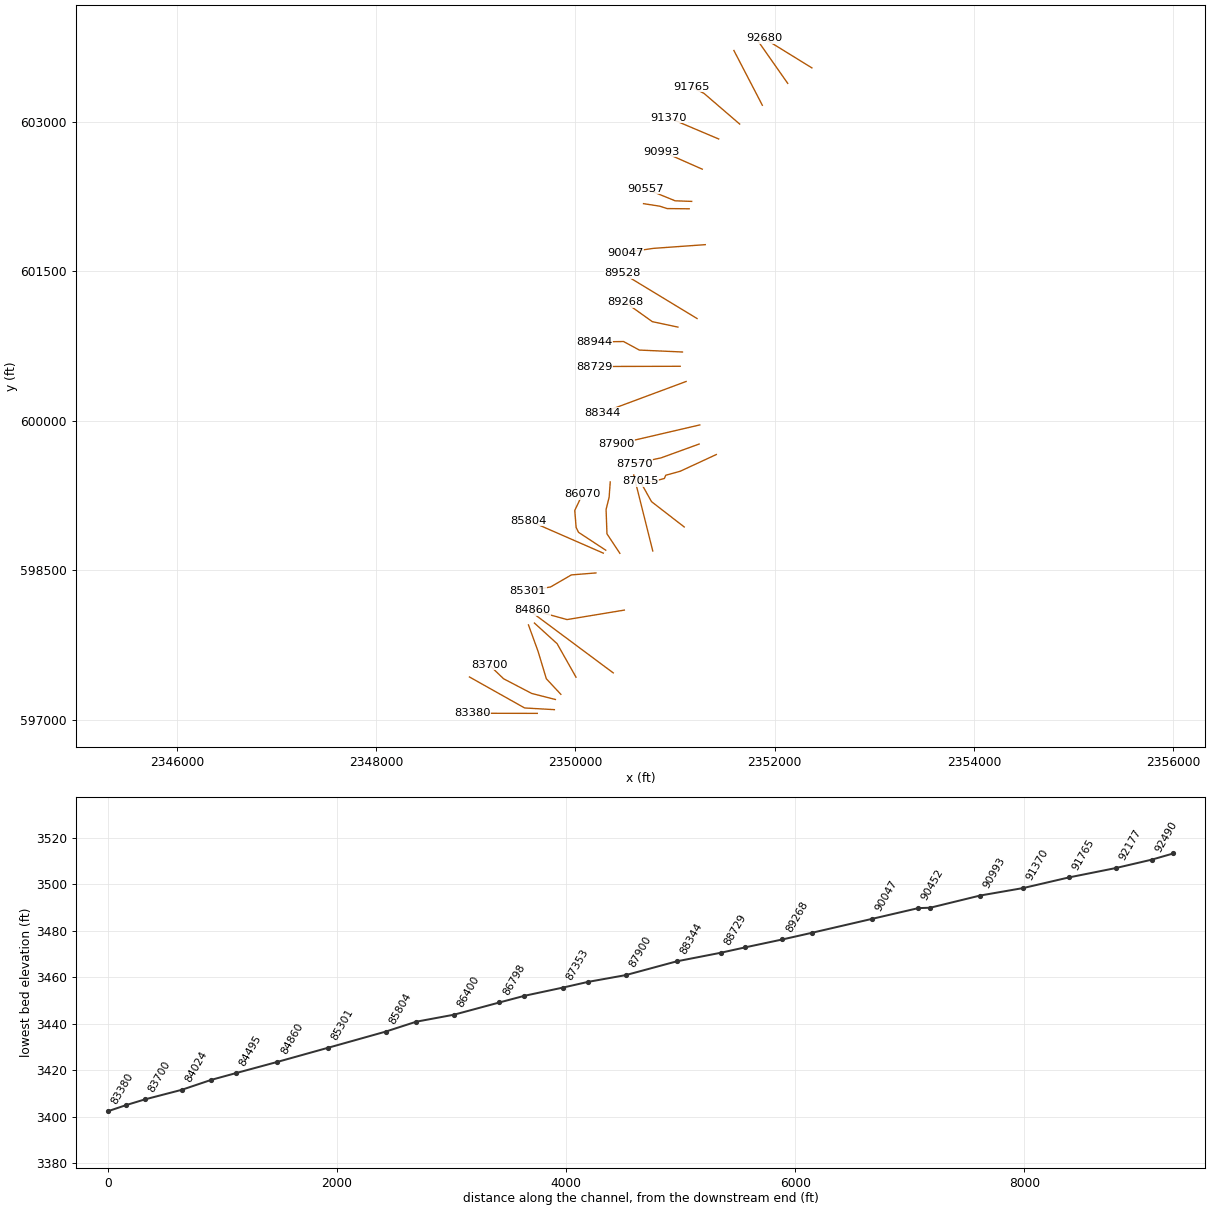
HEC-RAS study EFGRNBRRRV.prj: EFGRNBRRRV

--- EFGRNBRRRV.g01 (geometry) --- (continued)

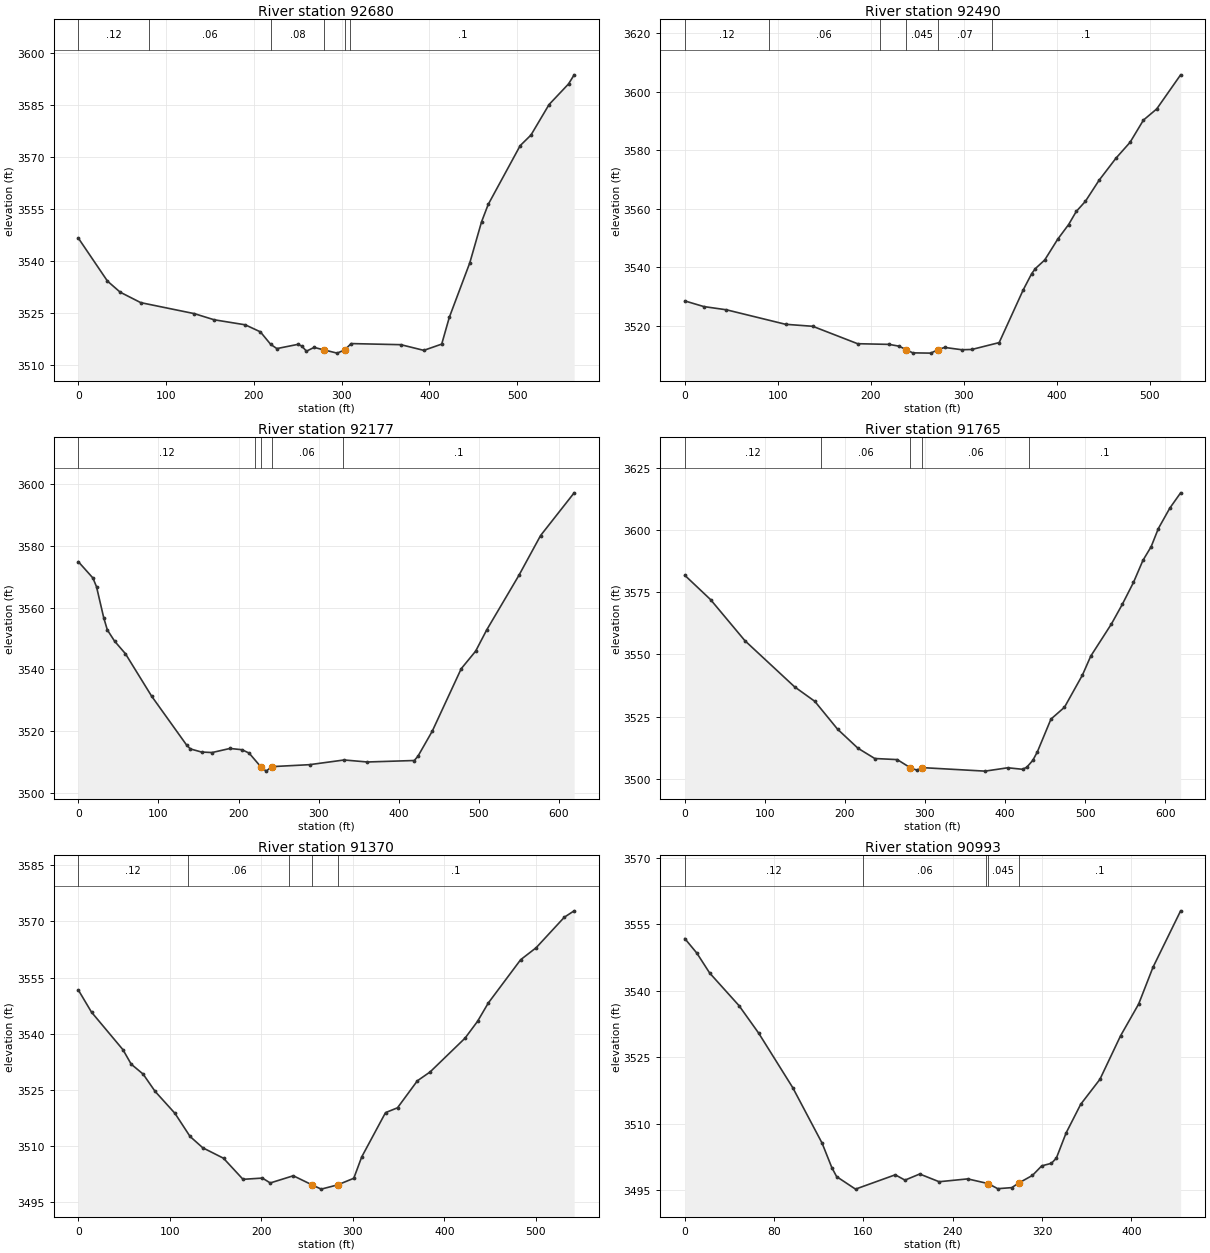
Type RM Length L Ch R = 1 ,92680   ,203,190,178.7
XS GIS Cut Line= 2
2352372.66147515 603539.977681092351891.84337334  603836.5703584
#Sta/Elev= 30
       0 3546.64    33.2 3534.21    47.7 3531.01    71.1 3527.99   132.2 3524.81
   154.7 3523.04   190.2 3521.58   207.4 3519.55   219.2 3515.92   226.2 3514.71
   249.7 3515.91   254.4 3515.49   259.9 3513.96   268.6 3515.05  280.42  3514.3
   294.8  3513.4   303.5 3514.32   310.8 3516.16   367.5 3515.84   393.6  3514.2
     414 3516.01   422.7 3523.77     446  3539.5   459.4 3551.35     467 3556.38
   503.4 3573.36   515.7 3576.42   536.3 3585.23   558.5 3591.19   564.9 3593.82
#Mann= 6 ,-1,0
       0     .12       0      80     .06       0     220     .08       0
  280.42    .045       0   303.5     .08       0     310      .1       0
Bank Sta=280.42,303.5
XS Rating Curve= 0 ,0
Exp/Cntr(USF)=0,0
Exp/Cntr=0.3,0.1

Type RM Length L Ch R = 1 ,92490   ,313.6,313.3,310.5
XS GIS Cut Line= 2
2352130.26172015603384.4897431622351824.30278934603821.069602125
#Sta/Elev= 30
       0 3528.55    20.4 3526.62    44.8 3525.51   108.3 3520.56   137.6 3519.87
   185.8 3513.92   219.7 3513.69   230.4 3513.07  238.32 3511.84   245.1 3510.79
   264.6  3510.7   271.8 3511.85   279.3 3512.65   297.8 3511.86   308.6 3511.95
     338  3514.3   363.8 3532.28     373  3537.9   376.9 3539.59     387 3542.55
   400.9 3549.62   412.7 3554.67   420.9 3559.14   430.7 3562.59   445.3 3569.74
   463.6 3577.35   478.7 3582.75   493.1 3590.36   507.4 3594.18   533.1 3605.84
#Mann= 6 ,-1,0
       0     .12       0      90     .06       0     210     .07       0
  238.32    .045       0   271.8     .07       0     330      .1       0
Bank Sta=238.32,271.8
XS Rating Curve= 0 ,0
Exp/Cntr(USF)=0,0
Exp/Cntr=0.3,0.1

Type RM Length L Ch R = 1 ,92177   ,400.3,411.7,420.5
XS GIS Cut Line= 2
2351875.44988232603165.0125897442351590.10852149603714.337425118
#Sta/Elev= 30
       0 3574.89    18.2 3569.62    22.7 3566.78    31.7 3556.75    36.2 3552.81
    45.3 3549.16    58.8  3545.1    91.5 3531.36   135.4 3515.45   139.9 3514.28
   153.8 3513.27     167 3513.11   189.3 3514.43   204.3 3514.02   213.2 3512.93
     228 3508.44   234.6 3507.09   241.4 3508.54   288.7 3509.18   331.8  3510.7
   360.8 3510.05   419.4 3510.53   423.9 3511.88   441.9 3520.05     478 3540.25
     496 3545.93   509.8  3552.8   550.1 3570.51   577.1 3583.37     619 3597.19
#Mann= 5 ,-1,0
       0     .12       0     220     .06       0     228    .045       0
   241.4     .06       0     330      .1       0
Bank Sta=228,241.4
XS Rating Curve= 0 ,0
Exp/Cntr(USF)=0,0
Exp/Cntr=0.3,0.1

Type RM Length L Ch R = 1 ,91765   ,375.3,395.2,404.2
XS GIS Cut Line= 3
 2351648.2019722602976.2088749422351290.24379798603283.762437515
2351159.53353389603352.107673643
#Sta/Elev= 30
       0 3581.85    32.2 3572.06    75.1 3555.52   137.2 3536.94   162.4 3531.12
   190.8 3519.92   216.3 3512.24   237.3  3508.1   265.4 3507.66   281.5 3504.43
     290  3503.4   296.1 3504.44   375.1 3503.02   403.5 3504.37   421.9 3503.76
   427.2 3504.59   434.7 3507.34   440.4 3510.75   457.4 3523.96   474.3 3528.73
   496.8 3541.73   507.1  3549.3   532.9 3562.23   546.5 3570.13   560.5 3578.98
   572.3 3587.84   582.6 3593.38   591.6 3600.68   605.9 3608.89   619.4 3615.04
#Mann= 5 ,-1,0
       0     .12       0     170     .06       0   281.5    .045       0
   296.1     .06       0     430      .1       0
Bank Sta=281.5,296.1
XS Rating Curve= 0 ,0
Exp/Cntr(USF)=0,0
Exp/Cntr=0.3,0.1

Type RM Length L Ch R = 1 ,91370   ,375.6,377.1,374.6
XS GIS Cut Line= 2
2351437.40312426602826.4141159982350938.29073406603037.840735906
#Sta/Elev= 30
       0 3551.68    14.4 3545.76    48.8 3535.72    57.8 3531.86    70.8 3529.22
    83.9  3524.6   105.6 3518.73   122.1 3512.56     136 3509.53   158.7 3506.73
     180  3501.1   201.2 3501.43   209.8 3500.13     235 3502.05  255.72 3499.59
   265.5 3498.48   283.5 3499.62   301.1 3501.38   309.8  3507.1   335.8 3518.92
   348.9 3520.21   370.6 3527.42   384.5 3529.78   422.7 3538.81   436.4 3543.31
   448.1 3548.19   483.5 3559.77   500.4 3562.96   531.3 3571.13     542 3572.83
#Mann= 5 ,-1,0
       0     .12       0     120     .06       0     230      .1       0
  255.72    .045       0   283.5      .1       0
Bank Sta=255.72,283.5
XS Rating Curve= 0 ,0
Exp/Cntr=0.3,0.1

Type RM Length L Ch R = 1 ,90993   ,433.5,435.6,437.2
XS GIS Cut Line= 3
2351272.60976801602523.4226996752350934.58418661602672.666289773
2350865.13698532602699.825907836
#Sta/Elev= 30
       0 3551.77    10.8 3548.49    22.3 3543.99    48.6 3536.63    66.1 3530.46
    96.7 3518.13     123  3505.6   131.7 3500.09     136 3498.06   152.9 3495.24
   188.5 3498.47   197.2 3497.27   210.4 3498.65   227.8 3496.91   253.4 3497.55
   271.7 3496.49   280.3 3495.34   292.9 3495.58   298.9 3496.59   311.4 3498.34
   319.7 3500.49   328.4 3501.07   332.8 3502.24   341.5  3507.9   354.6 3514.38
   371.8 3520.01   390.3 3529.83   406.5    3537   419.3 3545.27   444.1 3558.03
#Mann= 5 ,-1,0
       0     .12       0     160     .06       0     270      .1       0
   271.7    .045       0   298.9      .1       0
Bank Sta=271.7,298.9
XS Rating Curve= 0 ,0
Exp/Cntr=0.3,0.1

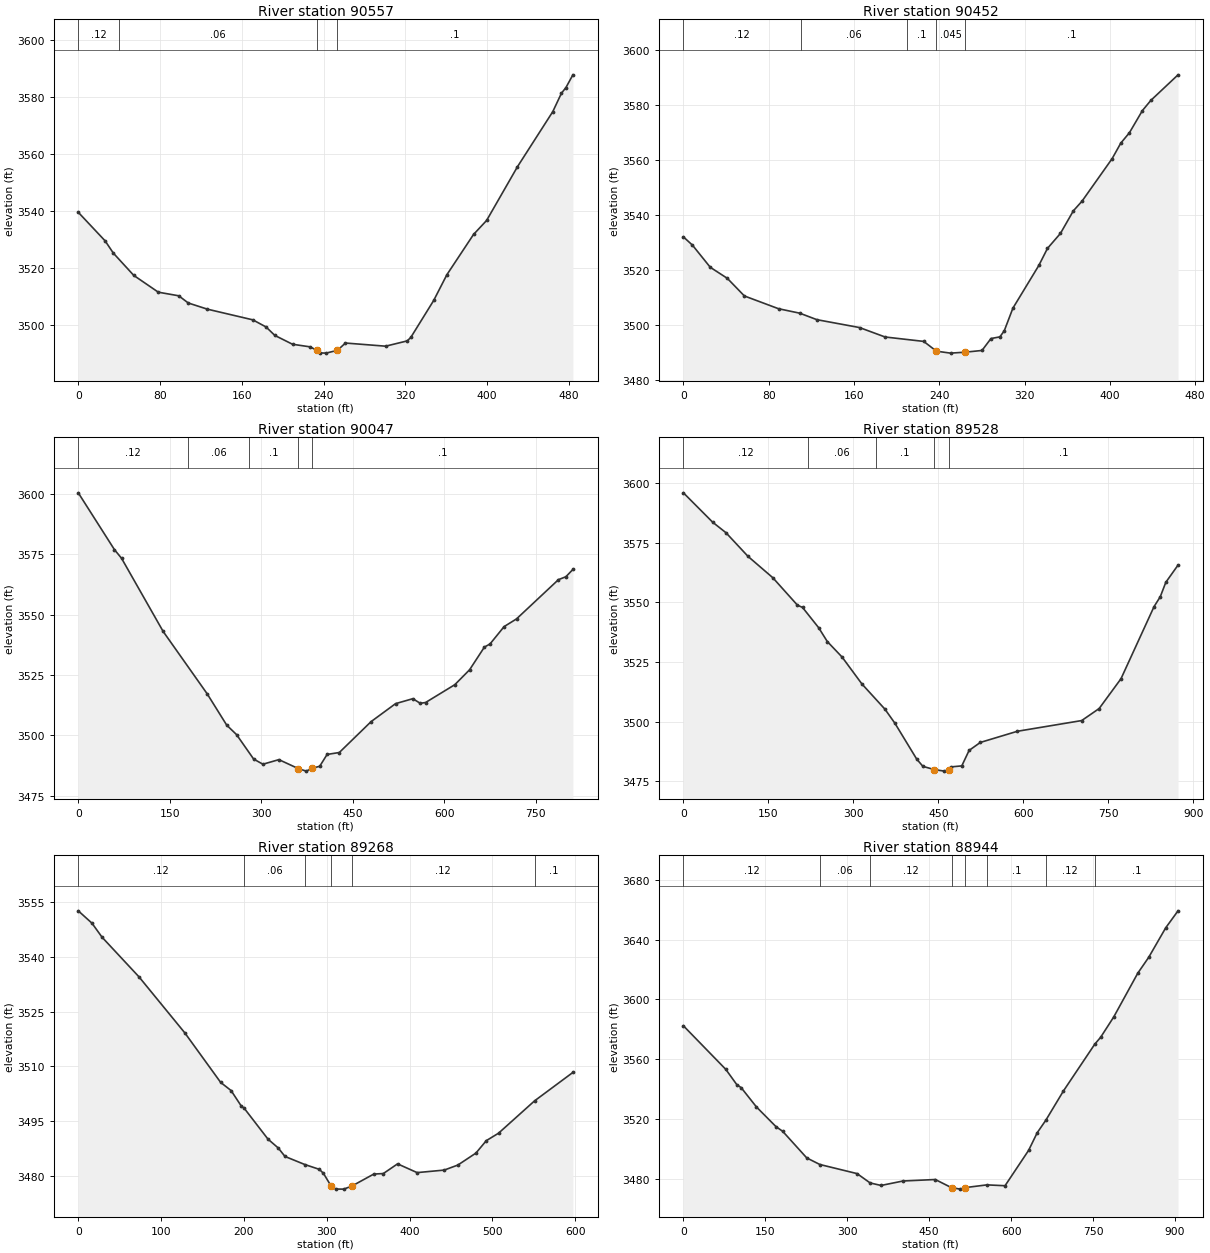
Type RM Length L Ch R = 1 ,90557   ,101.4,105.1,107.4
XS GIS Cut Line= 3
2351166.42782442602200.0521541162351001.18985642602205.911656528
2350705.87093488602325.445505722
#Sta/Elev= 30
       0 3539.51    26.3 3529.45    34.3 3525.16    54.3 3517.32    78.3 3511.42
    98.3 3510.15   107.6 3507.62   126.3 3505.45   170.8 3501.69   183.7 3499.19
   192.3 3496.22   209.6 3493.11   226.9 3492.19   233.1 3491.03   236.2 3490.08
   242.4 3489.99  253.55 3490.98   261.4 3493.54   300.7 3492.43   321.8 3494.29
   325.3  3495.5   347.7  3508.5   360.6 3517.55   386.7 3531.72   399.5 3536.65
   429.7 3555.55   464.2 3574.89   472.7 3581.38   477.1 3583.38   483.9 3587.85
#Mann= 4 ,-1,0
       0     .12       0      40     .06       0   233.1    .045       0
  253.55      .1       0
Bank Sta=233.1,253.55
XS Rating Curve= 0 ,0
Exp/Cntr(USF)=0,0
Exp/Cntr=0.3,0.1

Type RM Length L Ch R = 1 ,90452   ,392.6,405.1,417.4
XS GIS Cut Line= 4
2351141.41153775602125.8039029622350919.68993442602128.089692687
2350845.40176836602152.0904847992350683.11069788602177.234171774
#Sta/Elev= 30
       0 3532.02     8.5 3529.02    25.2 3520.98    41.2 3516.97    57.2 3510.57
    89.2 3505.94   109.2 3504.31   125.2 3501.96   165.2  3499.1   189.2 3495.67
   225.4 3494.07  237.41 3490.51   250.6 3489.81   264.3 3490.15   280.1 3490.78
   288.5  3495.1   296.9 3495.72     301 3497.93   309.1 3506.15   333.4 3521.64
   341.5 3527.84   353.7 3533.29   365.8 3541.49   373.9 3544.98   402.2 3560.46
   410.3 3566.08   418.4 3569.85   430.6 3577.91   438.5  3581.6     464 3590.88
#Mann= 5 ,-1,0
       0     .12       0     110     .06       0     210      .1       0
  237.41    .045       0   264.3      .1       0
Bank Sta=237.41,264.3
XS Rating Curve= 0 ,0
Exp/Cntr(USF)=0,0
Exp/Cntr=0.3,0.1

Type RM Length L Ch R = 1 ,90047   ,540.7,519,501.7
XS GIS Cut Line= 3
2351302.88799964601765.8891467232350779.91857695601728.438568392
2350496.77326774601686.239888281
#Sta/Elev= 30
       0 3600.38    59.3 3576.85    70.9 3573.29   139.1 3542.99   211.3 3517.15
   243.3 3504.19   259.4 3500.28   287.4 3490.16   302.6 3488.02   328.8 3489.92
   360.7  3486.2   373.6 3485.16   383.7 3486.35   395.7 3487.18   407.8 3492.07
   427.8 3492.87   479.9 3505.66     520  3513.1   548.3 3515.15   560.4 3513.24
   569.2 3513.57   617.1 3520.95   641.3 3527.12   665.6 3536.52   674.8 3537.81
   697.9    3545   718.2 3548.18   786.9 3564.43   799.1 3565.64   810.6 3568.66
#Mann= 5 ,-1,0
       0     .12       0     180     .06       0     280      .1       0
   360.7    .045       0   383.7      .1       0
Bank Sta=360.7,383.7
XS Rating Curve= 0 ,0
Exp/Cntr=0.3,0.1

Type RM Length L Ch R = 1 ,89528   ,261.1,260.2,256.1
XS GIS Cut Line= 2
     2351220.357      601024.4512350473.68687597601477.438844261
#Sta/Elev= 30
       0 3595.95    51.7 3583.62    75.1 3579.23   114.2 3569.26   157.9 3560.33
   201.4 3548.81   210.3 3547.89   238.8 3539.37     254 3533.59   280.2 3527.05
   315.2 3515.77   355.8 3505.21   373.4 3499.31   411.9 3484.27   422.9 3481.21
   443.3 3479.85   460.8 3479.22   468.1 3479.83   472.7    3481   491.5 3481.42
   504.4 3487.91   524.2 3491.25   589.7 3495.94   703.2 3500.43     734 3505.47
   772.6 3517.98     831 3548.24     842  3552.4   851.7 3558.41   873.3 3565.64
#Mann= 5 ,-1,0
       0     .12       0     220     .06       0     340      .1       0
   443.3    .045       0   468.1      .1       0
Bank Sta=443.3,468.1
XS Rating Curve= 0 ,0
Exp/Cntr=0.3,0.1

Type RM Length L Ch R = 1 ,89268   ,319.9,324,327.9
XS GIS Cut Line= 4
2351028.26494636600938.336140821 2350771.1136023600993.195094221
2350667.11016981601067.4832602832350499.10462502601187.487220846
#Sta/Elev= 30
       0 3552.63    16.5 3549.25    28.7  3545.4    73.3 3534.53   128.7 3519.15
   171.9 3505.59   184.5 3503.35   196.4 3499.24   200.5 3498.45   229.1 3490.02
   241.4 3487.61   249.6 3485.28   273.6 3483.06   291.1 3481.74     296 3480.65
   305.2 3477.19   310.8 3476.34   320.6 3476.32   330.5 3477.18   356.8 3480.45
   368.3 3480.59   385.5 3483.25   409.1 3480.85   441.8 3481.54   458.3 3482.92
   480.1  3486.2   492.7 3489.62   507.4 3491.65   550.9 3500.52   597.2 3508.32
#Mann= 6 ,-1,0
       0     .12       0   200.5     .06       0   273.6      .1       0
   305.2    .045       0   330.5     .12       0   550.9      .1       0
#XS Ineff= 2 , 0
                           385.5         3483.25
Permanent Ineff=
       F       F
Bank Sta=305.2,330.5
XS Rating Curve= 0 ,0
Exp/Cntr(USF)=0,0
Exp/Cntr=0.3,0.1

Type RM Length L Ch R = 1 ,88944   ,199.4,214.6,229.5
XS GIS Cut Line= 4
2351073.72861381600688.532291051 2350640.7421642600707.954965467
2350482.87190151600793.6481516122350190.48977519600789.611766731
#Sta/Elev= 30
       0 3582.36    77.6 3553.16    97.7 3542.95   105.8 3540.89   133.7 3527.98
   169.7 3514.71   181.7 3511.68   225.8 3493.83   249.8 3489.42   317.9 3483.32
   341.9 3477.05   361.9 3475.38     402 3478.37   461.1 3479.36   490.8  3473.9
   506.9 3472.92     516 3473.95   555.7 3475.77   588.8  3475.2     632 3498.92
   647.7 3510.71   663.5  3519.1   695.8 3538.76   753.2 3570.11   763.8 3574.65
   787.8 3588.29   831.8  3617.6   851.8 3628.23     883 3648.04   905.5 3659.39
#Mann= 8 ,-1,0
       0     .12       0   249.8     .06       0   341.9     .12       0
   490.8    .045       0     516     .12       0   555.7      .1       0
   663.5     .12       0   753.2      .1       0
#XS Ineff= 2 , 0
           461.1 3479.36
Permanent Ineff=
       F       F
Bank Sta=490.8,516
XS Rating Curve= 0 ,0
Exp/Cntr=0.3,0.1

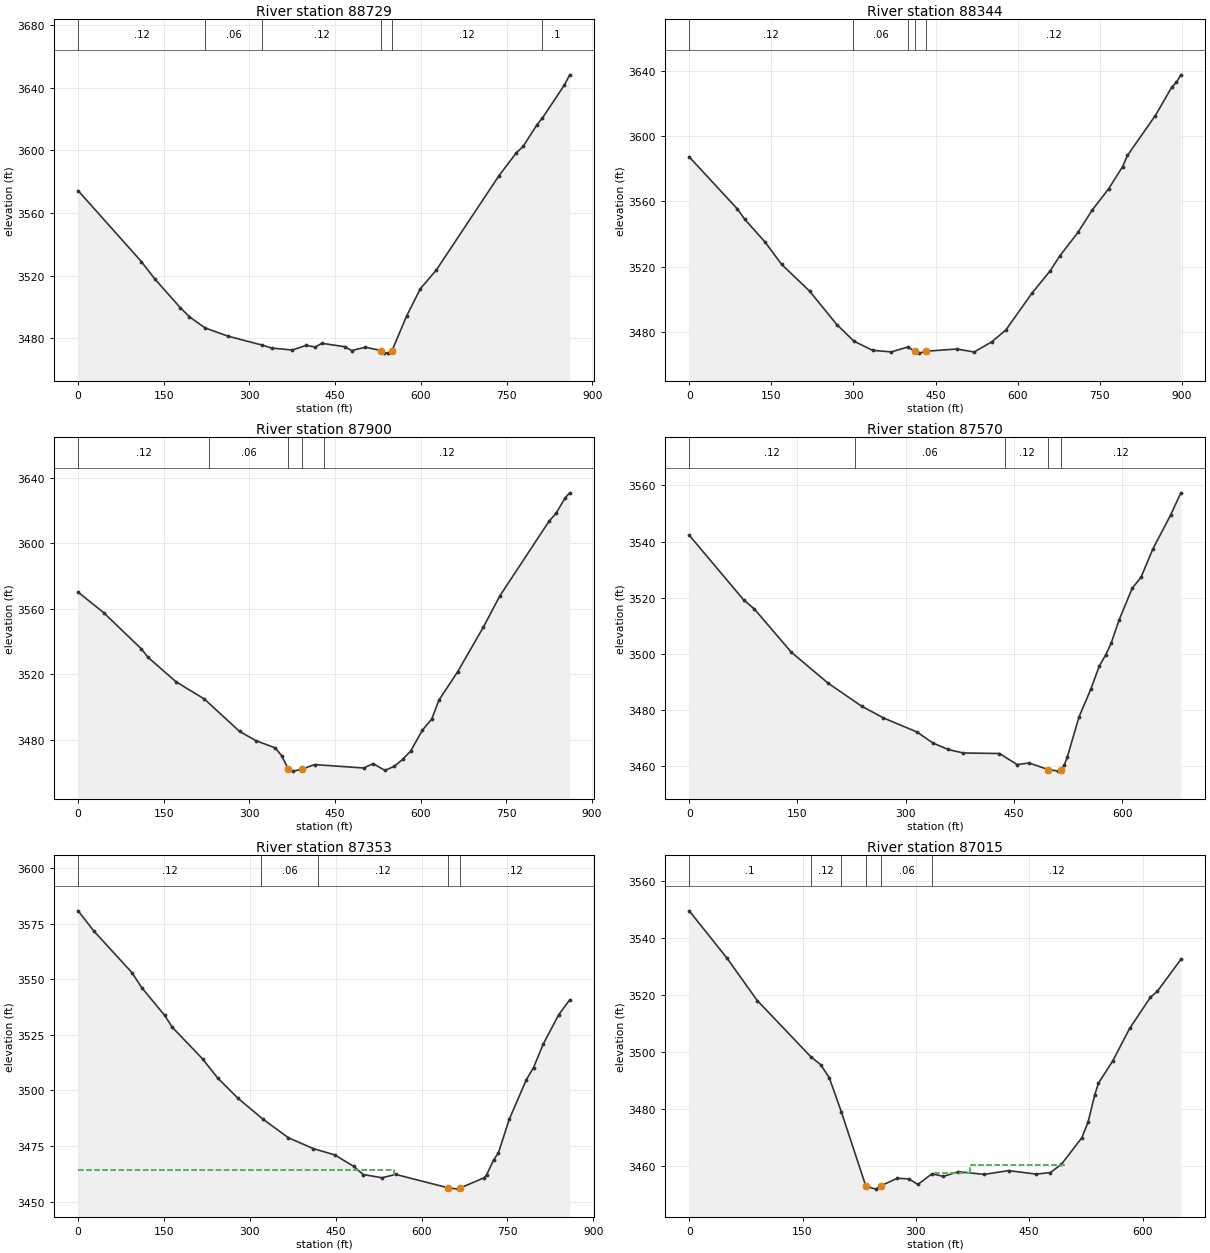
Type RM Length L Ch R = 1 ,88729   ,372.1,384.6,392.2
XS GIS Cut Line= 2
2351051.12284361600545.1803081192350190.52301214600542.894518394
#Sta/Elev= 30
       0 3574.25   110.7 3529.01   134.9  3517.6   178.9 3499.58   194.9 3493.74
   222.4 3486.62   262.9 3481.35   322.1 3475.71   338.9  3473.8   374.9 3472.57
   398.9  3475.5   414.9 3474.52   426.9 3476.83   466.9 3474.67   478.9 3472.22
   502.9 3474.33   530.9 3472.21   534.9  3470.8   542.9 3470.58   549.5 3472.18
   574.9 3494.16     599  3511.6     627 3523.59   736.9  3583.9     767 3598.35
     779 3602.46     803 3616.19   812.8  3620.6     851 3641.55   860.6 3648.16
#Mann= 6 ,-1,0
       0     .12       0   222.4     .06       0   322.1     .12       0
   530.9    .045       0   549.5     .12       0   812.8      .1       0
Bank Sta=530.9,549.5
XS Rating Curve= 0 ,0
Exp/Cntr(USF)=0,0
Exp/Cntr=0.3,0.1

Type RM Length L Ch R = 1 ,88344   ,444.9,444.3,435.6
XS GIS Cut Line= 2
2351110.33622763600392.604798443     2350268.498       600079.52
#Sta/Elev= 30
       0 3587.34    87.7 3555.48   101.6 3549.01   138.9 3534.92   168.7 3521.42
     220 3504.92   269.6 3484.43     301  3474.2   335.2 3468.57   369.3 3467.63
   399.2 3470.64   412.3 3467.99   420.5 3466.88   432.7 3468.05   488.8 3469.41
   520.7 3467.58   552.8 3473.83   578.4 3481.04   626.5 3503.81   659.5 3517.41
   676.6 3526.34   710.5 3541.13   736.3 3554.71   766.5 3567.84   791.8 3581.36
   800.7 3588.22   851.6 3612.69   881.4    3630     890 3633.06   898.2  3637.7
#Mann= 5 ,-1,0
       0     .12       0     300     .06       0     400     .12       0
   412.3    .045       0   432.7     .12       0
Bank Sta=412.3,432.7
XS Rating Curve= 0 ,0
Exp/Cntr=0.3,0.1

Type RM Length L Ch R = 1 ,87900   ,333.3,329.9,326
XS GIS Cut Line= 2
2351247.59148132599956.5629971792350408.70932558599761.350060603
#Sta/Elev= 30
       0 3570.11    44.6 3557.66   110.3 3535.68   122.6 3530.31   171.9 3515.34
   221.2 3504.93   282.8 3485.19   311.5 3479.52   345.5 3475.11   356.7 3470.29
  368.143462.243   377.2 3460.95   392.1 3462.14   414.2 3464.94   500.4 3462.86
   516.9 3465.53   537.4 3461.41   553.8 3463.84   568.7 3468.15   582.6 3473.18
   603.1 3485.93   619.5 3492.71     632  3504.2   664.7 3521.43   709.9 3548.75
   738.6 3567.69   825.2 3613.47   837.2 3618.15   853.6 3627.78   861.3 3630.69
#Mann= 5 ,-1,0
       0     .12       0     230     .06       0  368.14    .045       0
   392.1     .06       0     430     .12       0
Bank Sta=368.14,392.1
XS Rating Curve= 0 ,0
Exp/Cntr=0.3,0.1

Type RM Length L Ch R = 1 ,87570   ,216,217,217.2
XS GIS Cut Line= 3
2351241.08554454599764.7651694972350857.87414754599625.557339713
 2350590.2707466599569.312802062
#Sta/Elev= 30
       0 3542.26    75.7 3519.07    90.3 3515.91   141.4 3500.49   192.5 3489.41
   239.3 3481.15   269.1 3477.02   315.7 3471.98   337.2 3468.14   358.5 3465.76
   379.7  3464.5   429.9 3464.31   454.4 3460.36   470.8 3460.92   497.3  3458.6
   511.6 3458.02   515.7 3458.59   519.8 3460.26   523.9 3463.08   540.2 3477.44
   556.6 3487.36   568.2 3495.54     577 3499.48   584.6 3503.65   595.7 3512.03
   613.8  3523.3   626.1 3527.26   642.4 3537.33     667 3549.43   681.2 3557.38
#Mann= 5 ,-1,0
       0     .12       0     230     .06       0  437.71     .12       0
   497.3    .045       0   515.7     .12       0
Bank Sta=497.3,515.7
XS Rating Curve= 0 ,0
Exp/Cntr(USF)=0,0
Exp/Cntr=0.3,0.1

Type RM Length L Ch R = 1 ,87353   ,370.2,338.4,315.3
XS GIS Cut Line= 6
2351413.46198119599659.4356744652351050.87122078599491.536504619
2350905.98942584 599451.568567552350892.13610019599419.084907414
2350766.53937016599385.2387525482350627.32255683599420.048313886
#Sta/Elev= 30
       0 3580.72    27.9 3571.51      94 3552.95   111.6 3546.05   151.3 3533.67
   164.5 3528.37   217.4 3514.15   243.7  3505.6   279.1 3496.48   323.2 3486.99
   367.1 3478.74   410.7 3473.82     448 3471.01   481.2 3465.86     498 3462.16
     531  3460.7   554.5 3462.22645.58843456.228   663.9 3455.59   667.5 3456.11
   709.4 3460.71   713.6 3462.03   725.9 3468.71   734.2 3471.95   753.4 3487.16
   783.1 3504.84   795.6 3510.27   812.5 3520.84   839.5 3533.99   858.8 3540.75
#Mann= 5 ,-1,0
       0     .12       0     320     .06       0  419.58     .12       0
645.5884    .045       0   667.5     .12       0
#XS Ineff= 2 , 0
          552.07 3464.21
Permanent Ineff=
       F       F
Bank Sta=645.5884,667.5
XS Rating Curve= 0 ,0
Exp/Cntr(USF)=0,0
Exp/Cntr=0.3,0.1

Type RM Length L Ch R = 1 ,87015   ,240,217.4,200.4
XS GIS Cut Line= 3
2351091.44332302598932.5109099122350762.93545679599186.839580542
  2350648.487555599392.421922636
#Sta/Elev= 30
       0 3549.44    49.7 3532.98    90.1 3518.03     161 3498.35   173.9 3495.62
   185.3 3491.07   201.4 3479.05   233.8 3453.05   246.9 3452.02   253.7  3453.2
   275.5 3455.83   290.8  3455.6   302.6 3453.66   321.3 3457.38   336.4 3456.49
   356.4  3458.1   390.6 3457.19   422.7  3458.5   459.3 3457.28     478 3457.82
   492.7 3460.73   519.8 3470.06     528 3475.55   536.8 3485.09   541.7 3489.13
   560.4 3496.82   582.9 3508.26   610.4 3519.15   619.6 3521.27   650.7 3532.43
#Mann= 6 ,-1,0
       0      .1       0     161     .12       0   201.4     .06       0
   233.8    .045       0   253.7     .06       0   321.3     .12       0
#XS Ineff= 2 ,-1
     325  371.21 3457.57  371.21     500  3460.6
Permanent Ineff=
       F       F
Bank Sta=233.8,253.7
XS Rating Curve= 0 ,0
Exp/Cntr(USF)=0,0
Exp/Cntr=0.3,0.1

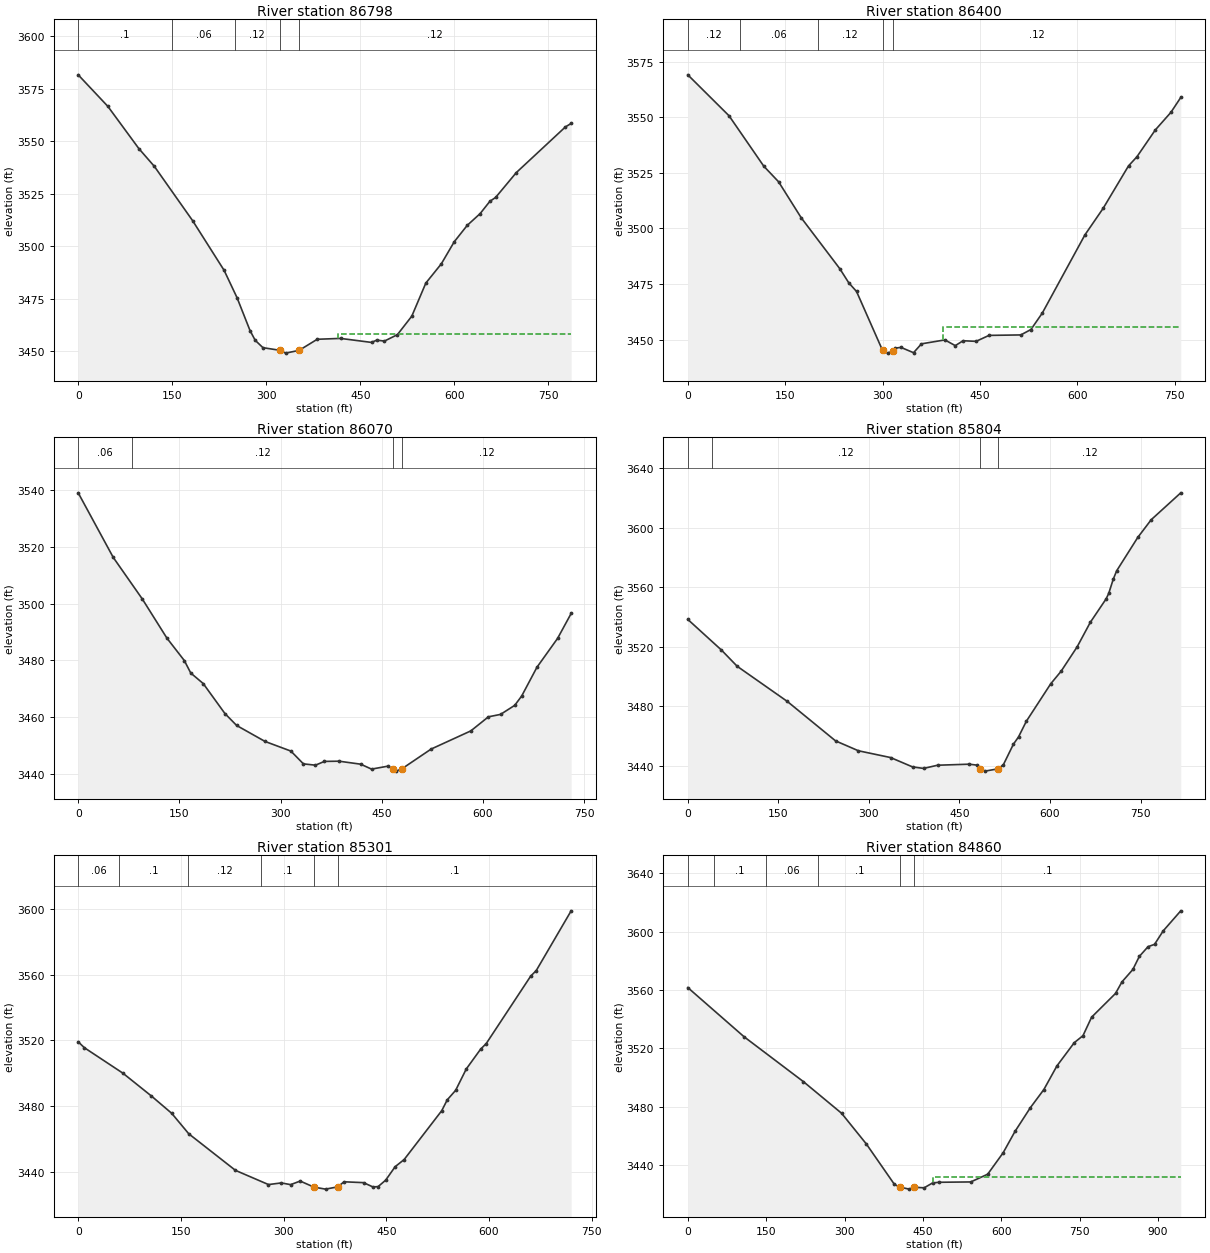
Type RM Length L Ch R = 1 ,86798   ,401.3,397,389.1
XS GIS Cut Line= 2
2350775.80236805598691.3362057812350584.68310025599454.027115611
#Sta/Elev= 30
       0 3581.72    47.4 3566.67    96.7 3546.61   121.5 3538.11   182.6 3512.22
   232.8 3488.57   253.4 3475.54   274.1  3459.9   282.3 3455.28   294.7 3451.75
   321.1 3450.54     331 3449.16   352.4 3450.48   381.3 3455.76   418.4 3456.17
   467.9 3454.26   476.1 3455.34   488.5  3454.9   509.1 3457.95   532.1 3466.76
   554.5 3482.53   579.2 3491.69   599.8  3502.2   620.5 3510.01   641.1 3515.61
   656.7 3521.49   665.8 3523.31   698.8 3535.15   777.2 3556.92   786.3 3558.57
#Mann= 5 ,-1,0
       0      .1       0     150     .06       0     250     .12       0
   321.1    .045       0   352.4     .12       0
#XS Ineff= 2 , 0
                          414.19         3458.41
Permanent Ineff=
       F       F
Bank Sta=321.1,352.4
XS Rating Curve= 0 ,0
Exp/Cntr(USF)=0,0
Exp/Cntr=0.3,0.1

Type RM Length L Ch R = 1 ,86400   ,329.8,330.5,331
XS GIS Cut Line= 5
 2350445.3625125598668.1161078242350316.13534117598863.431250261
  2350307.081531599108.0595945632350337.74874827599230.138709453
2350348.90979791599384.366821739
#Sta/Elev= 30
       0 3569.09    63.6 3550.65   117.1 3527.98   139.9 3520.96   174.8 3504.75
   234.2 3481.86     248 3475.52     260 3471.61     300 3445.14     308 3443.88
     316 3444.99     320 3446.17   328.5 3446.45   347.8 3444.07     360 3448.06
   396.1 3449.83   412.1 3447.25   424.1 3449.45   444.1 3449.18   464.1 3451.86
   513.1 3452.07   528.6  3454.5   546.1 3461.87   611.9 3497.11   639.9 3509.02
     679 3528.12     692 3532.24   720.2 3544.26   744.3  3552.2   759.5 3558.91
#Mann= 5 ,-1,0
       0     .12       0      80     .06       0     200     .12       0
     300    .045       0     316     .12       0
#XS Ineff= 2 , 0
                          392.56         3455.65
Permanent Ineff=
       F       F
Bank Sta=300,316
XS Rating Curve= 0 ,0
Exp/Cntr(USF)=0,0
Exp/Cntr=0.3,0.1

Type RM Length L Ch R = 1 ,86070   ,236.4,266.5,300.6
XS GIS Cut Line= 5
2350303.66960353598699.4051051772350030.51773139 598878.83959859
2350006.51693928598927.9840776772349992.80220093 599098.27541219
2350069.37615672599259.423587803
#Sta/Elev= 30
       0 3539.11      52 3516.29    95.1 3501.61   131.5 3487.82   157.3  3479.9
   166.9 3475.48   185.4 3471.76   217.5 3461.19   234.9 3456.97     277 3451.33
   315.3 3447.93   333.9 3443.41   351.7 3442.95     365 3444.28   386.7 3444.36
   418.8  3443.3   434.9 3441.56   458.8 3442.59   466.5 3441.68     471 3440.85
  479.83 3441.66   523.2 3448.64   582.1 3455.06   608.1 3460.02   626.1 3460.88
   647.1 3464.07   657.4 3467.35   680.1 3477.53   710.6 3487.69   730.8 3496.52
#Mann= 4 ,-1,0
       0     .06       0      80     .12       0   466.5    .045       0
  479.83     .12       0
Bank Sta=466.5,479.83
XS Rating Curve= 0 ,0
Exp/Cntr(USF)=0,0
Exp/Cntr=0.3,0.1

Type RM Length L Ch R = 1 ,85804   ,467.3,502.5,534.4
XS GIS Cut Line= 2
2350279.24950404598669.9022692052349530.84788526598996.769801989
#Sta/Elev= 30
       0 3538.43    55.7 3517.88    81.9 3506.94   164.9 3483.36   244.8 3456.89
   282.7 3450.24     336 3445.69   372.4  3439.4   390.7  3438.4   413.7 3440.54
     466 3441.24   478.8 3440.63   484.8  3438.1   492.2 3436.58     514 3438.12
   522.8 3440.88   539.5  3454.7   547.9 3459.53   560.8 3470.01   601.3 3495.23
   618.5 3503.66     645 3519.99   666.8 3536.44     693  3552.2   697.4 3555.94
   704.8 3565.36   710.5 3571.06   745.4 3593.43   767.7 3605.34   816.7 3623.41
#Mann= 4 ,-1,0
       0     .06       0      40     .12       0   484.8    .045       0
     514     .12       0
Bank Sta=484.8,514
XS Rating Curve= 0 ,0
Exp/Cntr(USF)=0,0
Exp/Cntr=0.3,0.1

Type RM Length L Ch R = 1 ,85301   ,450.3,441.5,427.1
XS GIS Cut Line= 4
2350205.16735603598471.1570945412349958.81335566598451.341139248
2349750.54573516598330.5316067512349521.91707835598291.236056362
#Sta/Elev= 30
       0  3519.2       9  3515.6    65.2 3500.14   106.8 3486.27   136.5 3475.74
   161.5 3463.25   229.7 3441.02   277.9 3432.39   296.4 3433.39   310.3 3432.36
   324.2 3434.52   344.3 3430.84   361.2 3429.62     379 3430.99   388.2 3434.08
   416.7 3433.56   430.5 3430.94     438 3431.17     449 3435.06   462.9 3443.27
     476  3447.6   530.9 3477.31     539 3483.93   551.2 3489.68   566.7 3502.65
   587.7 3514.72   595.9 3518.13   660.8 3559.11   668.9 3562.49   719.9 3598.81
#Mann= 6 ,-1,0
       0     .06       0      60      .1       0     160     .12       0
  267.15      .1       0   344.3    .045       0     379      .1       0
Bank Sta=344.3,379
XS Rating Curve= 0 ,0
Exp/Cntr(USF)=0,0
Exp/Cntr=0.3,0.1

Type RM Length L Ch R = 1 ,84860   ,394.6,364.5,337.3
XS GIS Cut Line= 3
2350490.49851586598098.1543516532349915.17228259598003.036899221
2349567.80564835598099.301711771
#Sta/Elev= 30
       0 3561.72   107.8 3527.97   221.3 3497.23   294.3 3475.57   341.7 3454.53
   395.6 3426.74   406.4 3424.84     424 3423.54   433.9 3424.82   452.4 3424.44
   468.6 3427.79   480.8 3428.24   541.6 3428.47     574 3433.76   603.6 3448.46
   626.3  3463.1   655.6 3479.32   681.6 3491.84   706.6 3508.04   739.8 3523.96
   756.4 3528.73     773 3541.45   818.7 3557.69   831.1 3565.64   851.9 3574.12
   864.3  3583.1     881 3589.76   893.4 3591.34     910 3600.59   943.6 3614.33
#Mann= 6 ,-1,0
       0     .12       0      50      .1       0     150     .06       0
     250      .1       0   406.4    .045       0   433.9      .1       0
#XS Ineff= 2 , 0
                          469.67         3432.08
Permanent Ineff=
       F       F
Bank Sta=406.4,433.9
XS Rating Curve= 0 ,0
Exp/Cntr=0.3,0.1

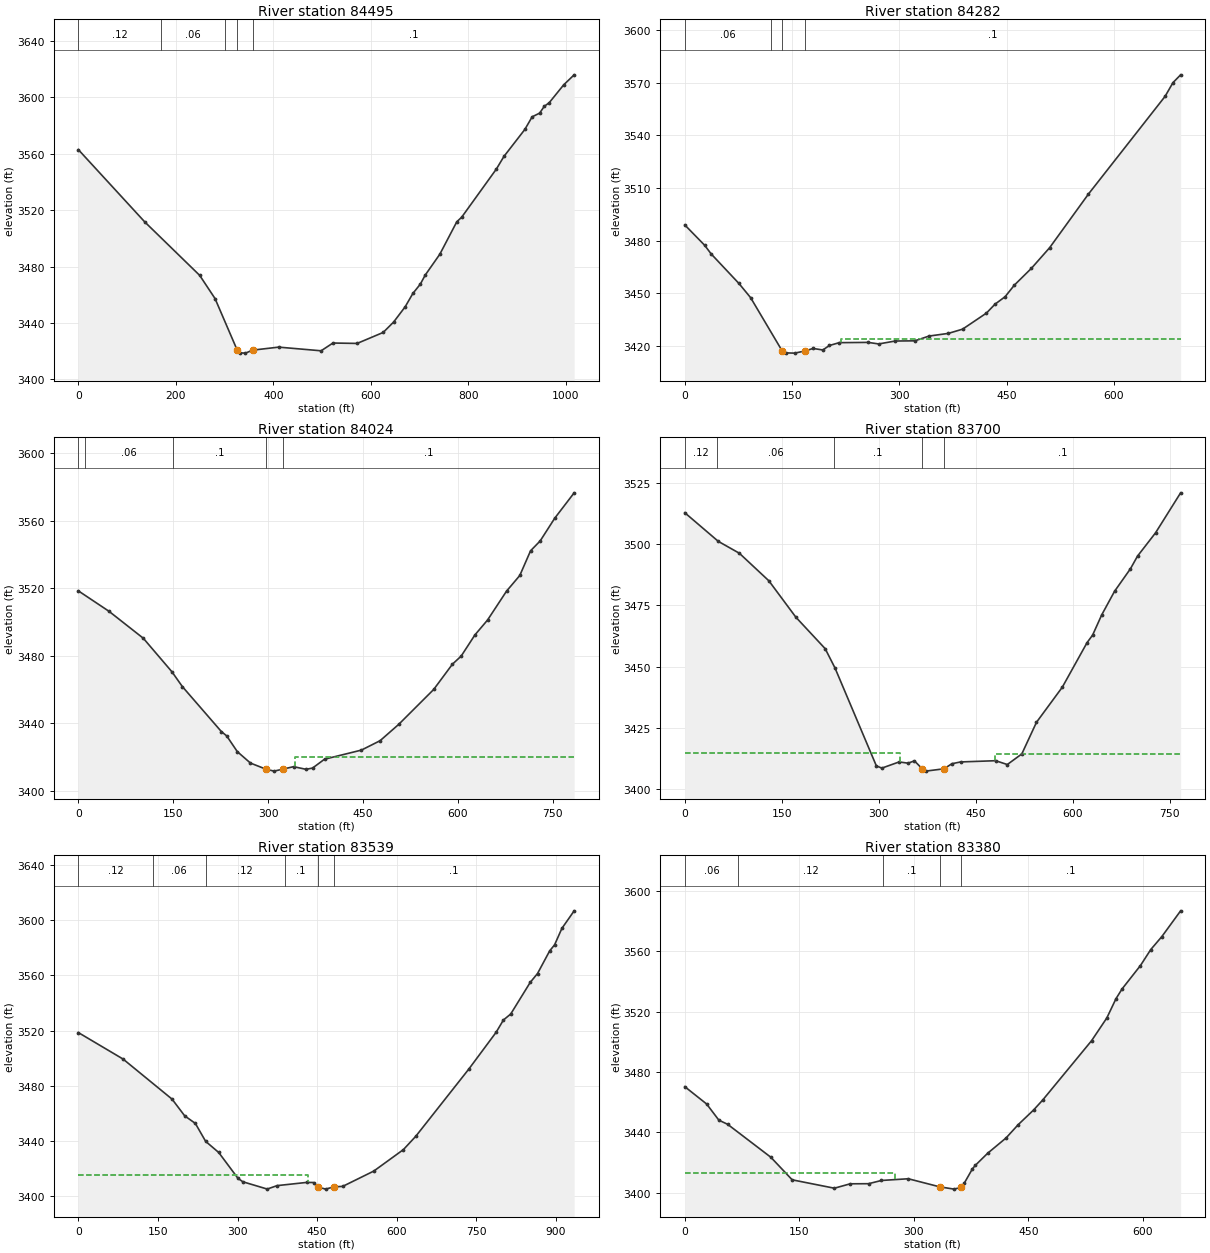
Type RM Length L Ch R = 1 ,84495   ,228,212.6,198.4
XS GIS Cut Line= 2
2350379.27454139597467.8156595672349562.99879012598075.110529221
#Sta/Elev= 30
       0 3562.75   136.3 3511.56     249 3473.72   280.5 3457.31   326.2 3420.63
   331.9 3418.86   342.9 3418.67   357.8 3420.78   411.1 3422.92   498.2 3420.32
   522.4 3425.82   572.1 3425.54   625.5 3433.31     647 3440.69   670.6 3451.45
   686.4 3460.89   701.8 3467.54   711.8 3473.93   741.7 3488.66   776.6 3511.67
   786.6  3514.9     858 3549.11   873.4 3557.97   916.2 3577.03   931.2 3585.97
   946.6 3588.59   956.1 3593.42   966.1 3595.91     996 3608.64  1017.4  3615.7
#Mann= 5 ,-1,0
       0     .12       0     170     .06       0     300      .1       0
   326.2    .045       0   357.8      .1       0
Bank Sta=326.2,357.8
XS Rating Curve= 0 ,0
Exp/Cntr(USF)=0,0
Exp/Cntr=0.3,0.1

Type RM Length L Ch R = 1 ,84282   ,265.9,258.3,249.5
XS GIS Cut Line= 3
2350005.37404442597425.0773334852349815.65349724597761.088423061
 2349588.2174196597967.952393174
#Sta/Elev= 30
       0 3488.89    27.7 3477.32    36.9 3472.34    75.7 3455.52      92 3447.44
     136 3417.17   141.9 3415.93   153.6  3415.8   168.3 3417.04   179.3 3418.47
     193  3417.6   202.2 3420.15     216 3421.77   256.4 3421.92   271.1 3421.03
   294.1  3422.7   321.7 3422.81   341.5 3425.53   368.5 3427.05   388.4 3429.46
   421.7  3438.6   433.8 3443.72   447.9 3447.97   460.9 3454.61   484.7 3464.17
   510.2 3475.93   564.4 3506.49   671.6 3562.21   682.6 3570.02   693.3 3574.47
#Mann= 4 ,-1,0
       0     .06       0     120      .1       0     136    .045       0
   168.3      .1       0
#XS Ineff= 2 , 0
                          218.74         3423.75
Permanent Ineff=
       F       F
Bank Sta=136,168.3
XS Rating Curve= 0 ,0
Exp/Cntr(USF)=0,0
Exp/Cntr=0.3,0.1

Type RM Length L Ch R = 1 ,84024   ,298.9,324.6,354.7
XS GIS Cut Line= 4
2349853.14748414597252.9765905662349707.67786201597408.872333983
2349624.66251868597683.7438499042349528.08520156597949.865746304
#Sta/Elev= 30
       0 3518.33    48.3 3506.26   102.7 3490.23   147.9 3470.37   164.4 3461.59
   226.1 3434.91   234.4  3432.4   251.2 3423.06     272 3416.27   296.5 3412.65
   309.3  3411.5  324.01 3412.75   340.1 3414.14   359.8 3412.58   370.1 3413.31
     389 3418.56   447.3 3423.96   476.8 3429.52   506.1 3439.15   561.5 3459.88
   591.2  3474.9   604.9 3479.64   626.7 3492.22   646.6 3501.02   676.7 3518.19
   697.6 3527.44   714.6 3542.06   729.8 3547.92   752.9 3561.43   783.5 3576.42
#Mann= 5 ,-1,0
       0     .12       0      10     .06       0     150      .1       0
   296.5    .045       0  324.01      .1       0
#XS Ineff= 2 , 0
                          341.91         3419.76
Permanent Ineff=
       F       F
Bank Sta=296.5,324.01
XS Rating Curve= 0 ,0
Exp/Cntr=0.3,0.1

Type RM Length L Ch R = 1 ,83700   ,160.4,160.8,157.6
XS GIS Cut Line= 4
 2349798.5100743597201.069940435 2349560.7879429597261.643368147
2349278.49291187 597409.076805412349132.20236946597549.652873498
#Sta/Elev= 30
       0 3512.76    51.9 3501.06    84.3 3496.24     130 3484.98   171.7 3470.15
   217.1 3457.28   232.3 3449.39   296.2 3409.48   304.7 3408.56   331.4 3411.08
   345.3 3410.58   355.1 3411.52     367 3408.31   372.4 3407.33  400.82 3408.28
     413 3410.35   426.5 3411.08   480.7 3411.58   498.7 3410.02   521.1 3414.34
   543.8 3427.25   583.7 3441.56   622.1 3459.79   630.6 3462.83   644.7 3471.09
   664.5 3480.69   689.1  3489.9   700.1 3495.08   727.9 3504.55   766.7 3520.88
#Mann= 5 ,-1,0
       0     .12       0      50     .06       0     230      .1       0
     367    .045       0  400.82      .1       0
#XS Ineff= 2 , 0
             332 3414.62  479.19         3414.38
Permanent Ineff=
       F       F
Bank Sta=367,400.82
XS Rating Curve= 0 ,0
Exp/Cntr(USF)=0,0
Exp/Cntr=0.3,0.1

Type RM Length L Ch R = 1 ,83539   ,139.4,159.1,174
XS GIS Cut Line= 3
2349788.29825934597098.9987174142349489.76617349597115.941867444
2348935.96790769597427.078881616
#Sta/Elev= 30
       0 3518.54    84.3 3499.31   176.6 3470.22   200.4  3458.1   220.5 3452.59
   239.9 3439.57   264.5 3431.51   300.8 3412.74     310 3410.24   355.9 3404.96
   374.5 3407.45   430.3 3409.78   443.1 3409.71   450.9 3406.52     466 3404.91
   481.2 3406.56   498.1  3406.9   556.7 3418.02   612.5  3433.6   635.8 3443.27
   735.9 3492.13   787.2 3518.75   800.9 3527.64   814.7 3532.02   851.4 3554.93
   865.2  3561.4   888.1 3577.84   897.3 3582.18   911.1 3594.16   934.2 3606.89
#Mann= 6 ,-1,0
       0     .12       0     140     .06       0     240     .12       0
  389.01      .1       0   450.9    .045       0   481.2      .1       0
#XS Ineff= 2 , 0
          432.85 3415.13
Permanent Ineff=
       F       F
Bank Sta=450.9,481.2
XS Rating Curve= 0 ,0
Exp/Cntr=0.3,0.1

Type RM Length L Ch R = 1 ,83380   ,118.9,120,121
XS GIS Cut Line= 2
2349616.78979117597061.6367672092348967.62550926597062.779662072
#Sta/Elev= 30
       0  3470.2    28.6 3458.72    44.6    3448    56.1 3445.25   112.6 3423.43
   140.6 3408.44   195.8 3402.88   216.6  3405.8   240.6 3405.87   257.5 3408.01
   292.6 3409.15   333.7 3403.79   352.6 3402.27   361.7 3403.47   365.7 3406.04
   376.6 3415.72   380.6 3418.15   396.6 3426.08   420.6 3436.18   436.6 3445.05
   456.6 3454.69   468.6 3461.34   532.6 3500.68   552.6 3515.79   564.6 3528.57
   572.6 3535.06   596.6 3550.52   610.1 3561.13   624.6 3569.72   649.2  3586.8
#Mann= 5 ,-1,0
       0     .06       0      70     .12       0     260      .1       0
   333.7    .045       0   361.7      .1       0
#XS Ineff= 2 , 0
          275.25 3412.64
Permanent Ineff=
       F       F
Bank Sta=333.7,361.7
XS Rating Curve= 0 ,0
Exp/Cntr(USF)=0,0
Exp/Cntr=0.3,0.1