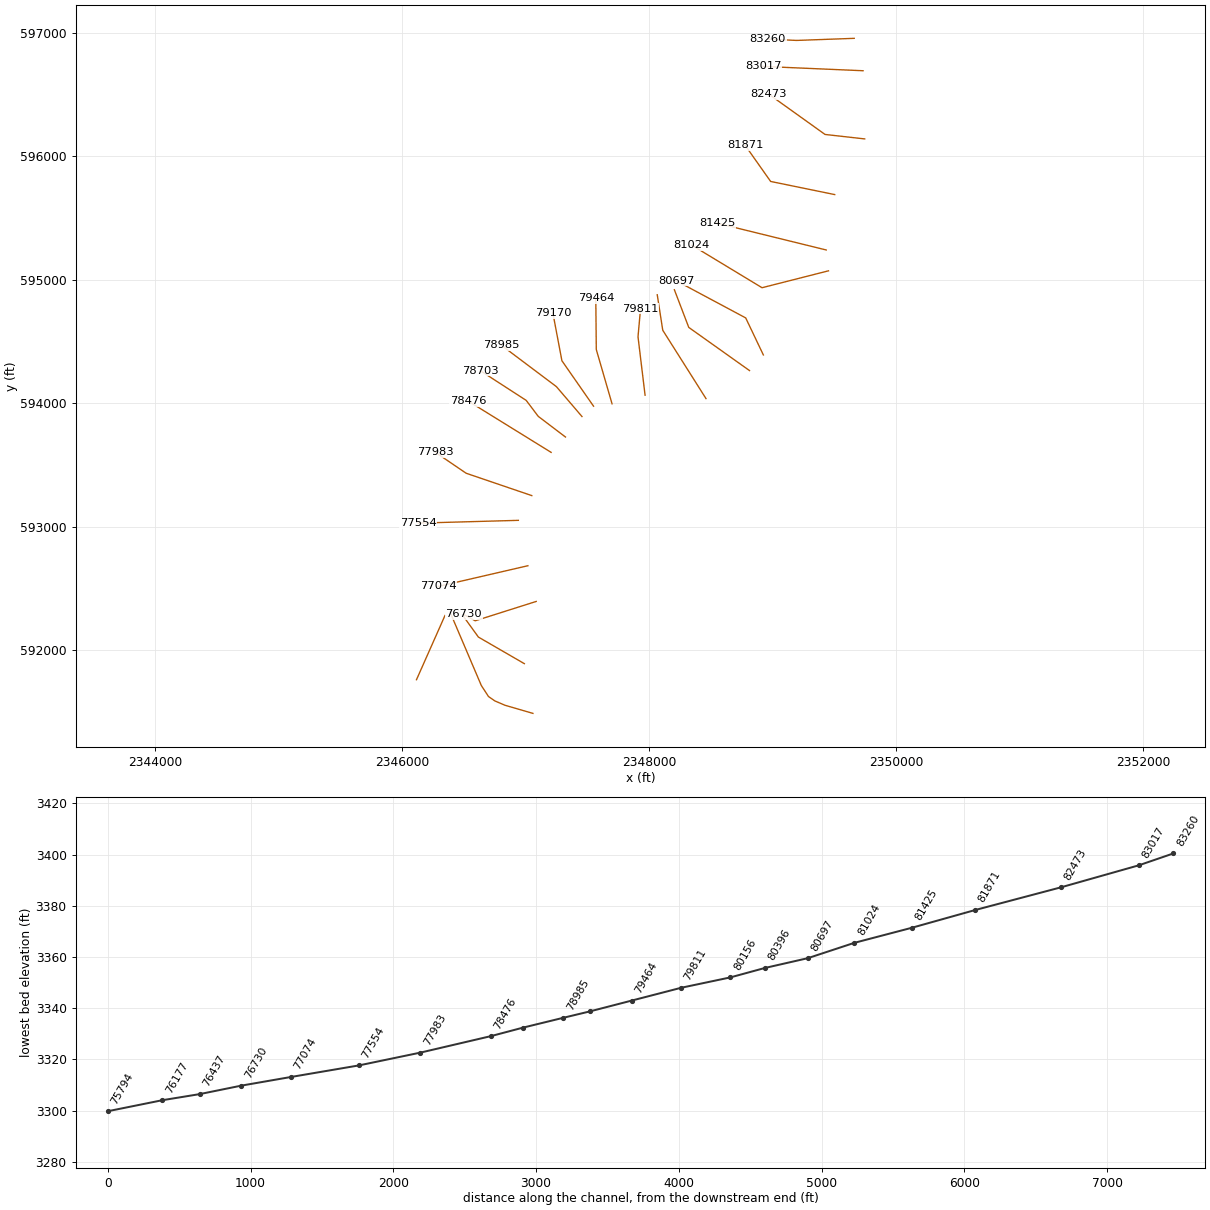
HEC-RAS study EFGRNBRRRV.prj: EFGRNBRRRV

--- EFGRNBRRRV.g01 (geometry) --- (continued)

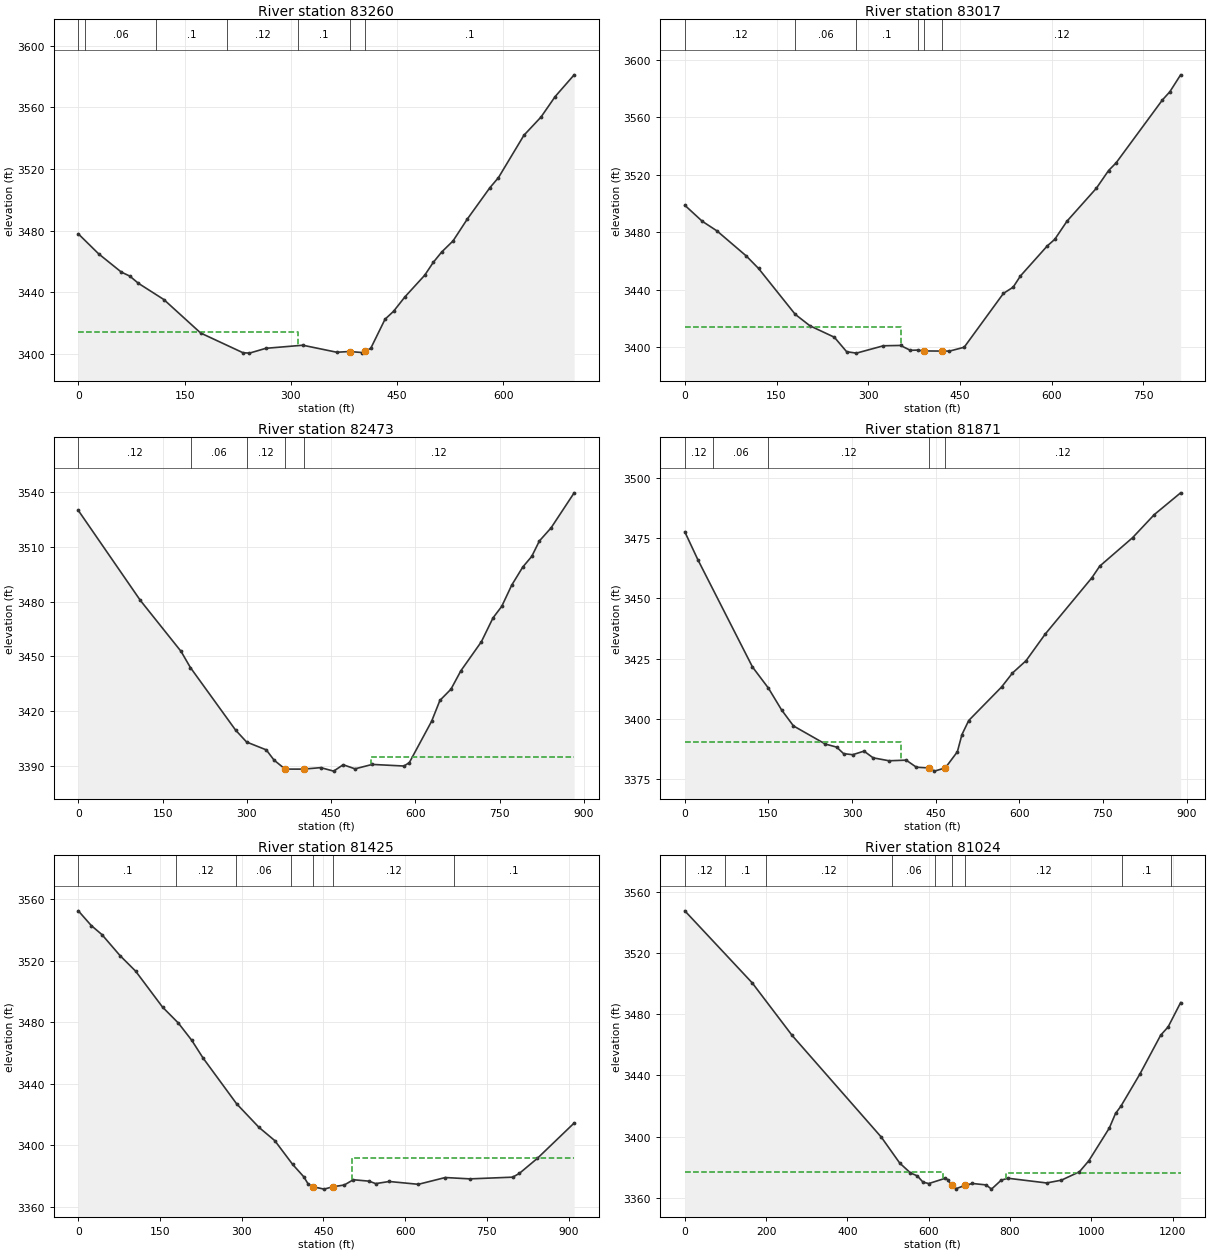
Type RM Length L Ch R = 1 ,83260   ,244.7,242.7,236.9
XS GIS Cut Line= 3
2349660.84455072596957.2249013482349194.57532123596940.269656639
2348961.44070649596950.866684582
#Sta/Elev= 30
       0 3477.89    28.7 3464.93    60.7 3453.09    72.7 3450.48    84.7 3445.84
   120.7 3435.28   172.8 3413.51   232.4 3400.76   241.6 3400.49   264.8 3403.62
   316.9 3405.62   364.9 3401.06     383 3401.54   400.9 3400.86   404.9 3401.58
   412.9 3403.66     433  3422.5     445 3427.62     461 3436.96     489 3451.05
     501 3459.34     513 3466.13     529 3473.32   549.1 3487.48   581.1 3507.91
   593.1 3514.39   629.1 3541.91   653.2 3553.73   673.2 3567.04     700 3581.13
#Mann= 7 ,-1,0
       0     .12       0      10     .06       0     110      .1       0
     210     .12       0     310      .1       0     383    .045       0
   404.9      .1       0
#XS Ineff= 2 , 0
          309.97 3414.07
Permanent Ineff=
       F       F
Bank Sta=383,404.9
XS Rating Curve= 0 ,0
Exp/Cntr(USF)=0,0
Exp/Cntr=0.3,0.1

Type RM Length L Ch R = 1 ,83017   ,567.1,544.1,524.4
XS GIS Cut Line= 2
 2349732.6518358596694.7411613812348922.52438901596729.654331227
#Sta/Elev= 30
       0  3498.7    28.5 3487.56    52.5 3480.88   100.6 3463.39   120.6 3454.74
   180.6 3422.82   204.7 3414.84   244.6  3406.9   264.7 3396.82   280.7 3395.84
   324.8 3400.95   352.8 3401.19   368.8 3397.81   380.8 3397.95   390.5 3397.36
   420.9 3397.27   432.9 3397.25   456.9 3399.93   521.1 3437.38     537 3441.71
     549 3449.55     593 3470.49     605 3474.95   625.1 3487.64   673.1 3510.52
   693.1 3522.85   705.2 3528.07   781.2 3571.97   793.2 3577.56   810.9 3589.39
#Mann= 6 ,-1,0
       0     .12       0   180.6     .06       0   280.7      .1       0
   380.8     .12       0   390.5    .045       0   420.9     .12       0
#XS Ineff= 2 , 0
           352.8 3413.76
Permanent Ineff=
       F       F
Bank Sta=390.5,420.9
XS Rating Curve= 0 ,0
Exp/Cntr=0.3,0.1

Type RM Length L Ch R = 1 ,82473   ,582.9,602,612
XS GIS Cut Line= 3
2349745.92365399596142.4323714032349425.02045808596178.401547568
2348969.85419874596504.273648347
#Sta/Elev= 30
       0 3529.82   110.4 3480.63   182.9 3452.73   199.5 3443.91   279.9 3409.72
   299.6 3403.17   334.6 3398.88   348.5 3393.26   368.2 3388.37   401.1 3388.36
   431.6 3389.17   454.5 3387.26   471.5 3390.75   492.6 3388.51   523.3 3390.93
   579.8 3390.05   589.3 3391.94     629 3414.57   643.7 3425.94   663.4 3432.08
     681 3442.13   717.5 3458.01   738.3  3471.1   753.7 3477.33   771.6 3489.01
   791.3 3498.91   807.2  3504.7   820.8 3513.14   841.6  3520.3   882.7 3539.46
#Mann= 5 ,-1,0
       0     .12       0     200     .06       0     300     .12       0
   368.2    .045       0   401.1     .12       0
#XS Ineff= 2 , 0
                          520.55         3395.21
Permanent Ineff=
       F       F
Bank Sta=368.2,401.1
XS Rating Curve= 0 ,0
Exp/Cntr=0.3,0.1

Type RM Length L Ch R = 1 ,81871   ,445.5,445.7,442.8
XS GIS Cut Line= 3
     2349503.133      595691.3692348984.28250257595797.754768019
2348776.89933123596091.775463718
#Sta/Elev= 30
       0 3477.53    23.4 3465.98   121.4 3421.53     150 3412.76   173.5 3403.78
   194.9 3397.11   252.1  3389.6   272.5 3388.32   284.8 3385.63   301.1 3385.18
   321.5 3386.66   337.8 3383.89   366.4 3382.67   397.1 3382.93   415.4    3380
   438.1 3379.71   447.9 3378.38  467.333379.728   488.9 3386.39   497.1  3393.5
   509.3 3399.35   568.1  3413.2   587.7    3419   612.2 3424.14   646.4 3435.12
   730.2 3458.48   744.3  3463.3   803.1 3475.06   842.2 3484.66   889.4 3493.67
#Mann= 5 ,-1,0
       0     .12       0      50     .06       0     150     .12       0
   438.1    .045       0  467.33     .12       0
#XS Ineff= 2 , 0
          388.17 3390.43
Permanent Ineff=
       F       F
Bank Sta=438.1,467.33
XS Rating Curve= 0 ,0
Exp/Cntr=0.3,0.1

Type RM Length L Ch R = 1 ,81425   ,411.5,400.9,388.7
XS GIS Cut Line= 2
2349434.31842072595242.529844261      2348550.47      595459.944
#Sta/Elev= 30
       0 3552.62    23.8 3543.02    43.4 3537.12    76.7 3523.41   105.2 3513.34
   154.6 3489.93   183.5 3479.59   208.2 3468.32   228.8 3456.87   290.6 3426.97
   331.7 3411.61   360.6 3403.01   393.5 3387.48   413.9 3379.44   422.4 3374.45
   430.9 3372.97   451.2 3371.42   466.8 3372.91   488.3 3374.12   504.8 3377.53
   533.6 3376.61   545.9 3375.01   570.7 3376.39   624.2 3374.56   673.6 3378.97
     719  3378.1   797.4 3379.21   809.6 3381.66   842.5 3391.41   910.2 3414.46
#Mann= 7 ,-1,0
       0      .1       0     180     .12       0     290     .06       0
     390     .12       0   430.9    .045       0   466.8     .12       0
     690      .1       0
#XS Ineff= 2 , 0
                          502.54         3391.46
Permanent Ineff=
       F       F
Bank Sta=430.9,466.8
XS Rating Curve= 0 ,0
Exp/Cntr=0.3,0.1

Type RM Length L Ch R = 1 ,81024   ,327.9,326.7,325.1
XS GIS Cut Line= 3
2349452.59863921595073.663512358 2348914.6222087594936.824982215
2348346.30057646595281.088677237
#Sta/Elev= 30
       0 3547.86     166 3500.61     264 3466.24   483.3 3399.64   528.7 3382.62
   555.1 3376.17     572 3374.21     586 3370.13   600.1 3369.21   640.7 3372.67
   646.8 3371.78   656.2 3367.96   667.8 3365.92   688.9 3367.97   707.6 3369.26
   741.1 3368.32   754.4 3365.56   778.5 3371.47   795.1 3372.68     890  3369.6
   926.4 3371.44   970.7 3376.92     994 3384.22  1044.3 3405.62  1059.5 3415.15
  1072.4 3419.75  1119.2 3440.84  1170.6 3466.42  1188.9 3471.84  1219.6 3487.76
#Mann= 9 ,-1,0
       0     .12       0     100      .1       0     200     .12       0
     510     .06       0  615.11     .12       0   656.2    .045       0
   688.9     .12       0 1075.11      .1       0 1195.11     .12       0
#XS Ineff= 2 , 0
           634.6 3377.01   790.8         3375.89
Permanent Ineff=
       F       F
Bank Sta=656.2,688.9
XS Rating Curve= 0 ,0
Exp/Cntr=0.3,0.1

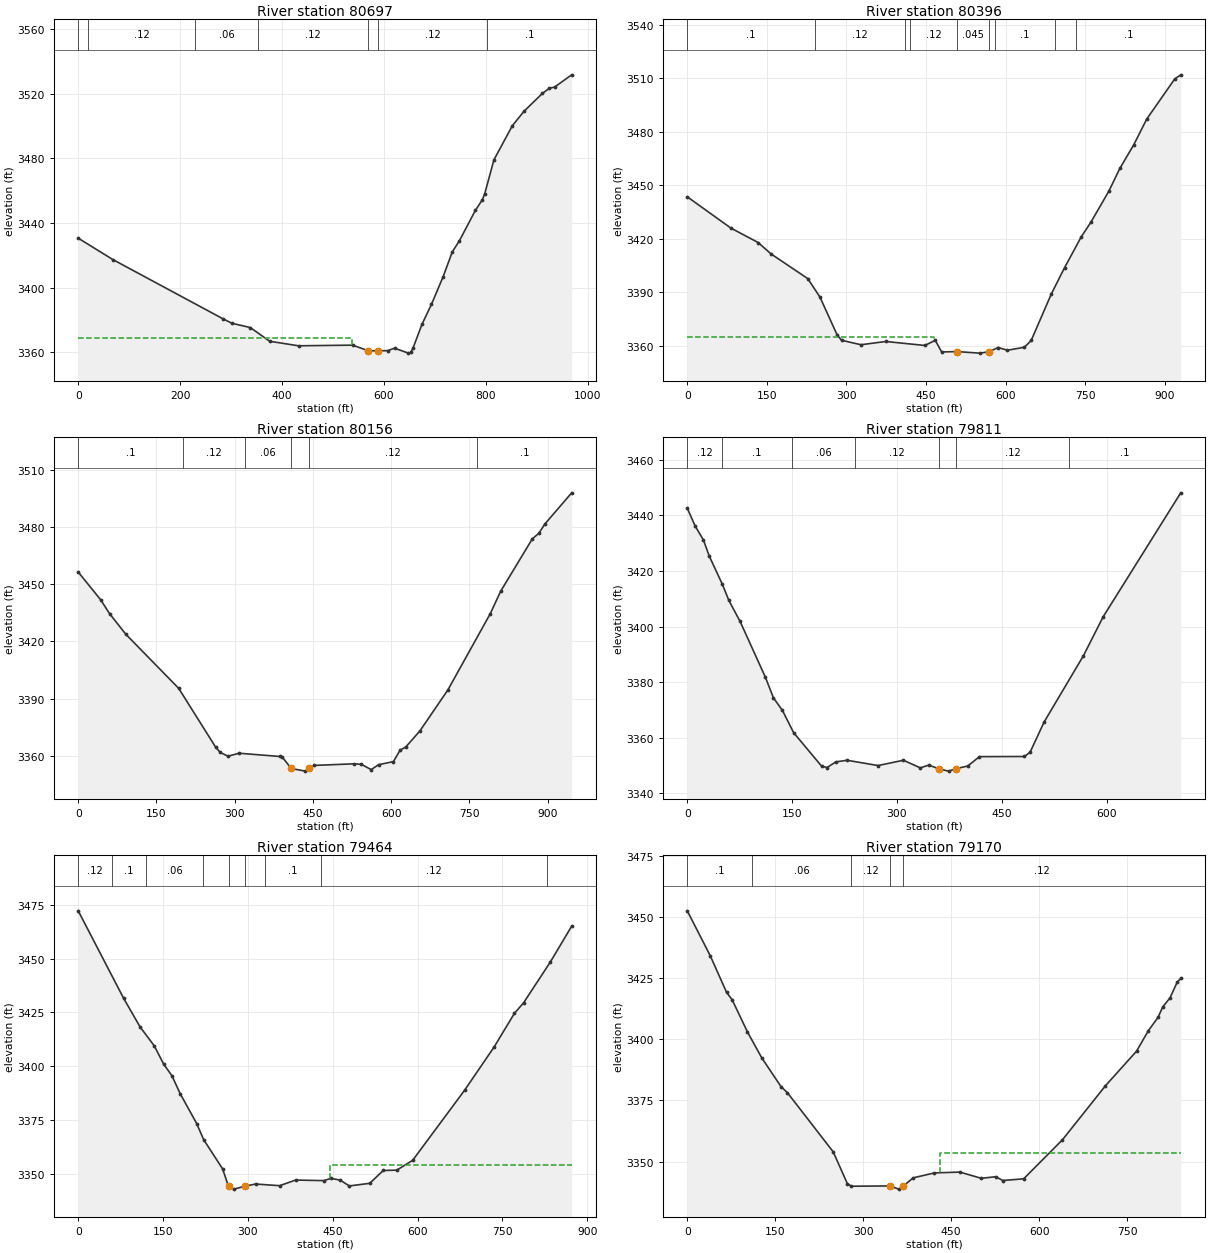
Type RM Length L Ch R = 1 ,80697   ,304.5,301,300.4
XS GIS Cut Line= 3
2348925.33917699594392.0457609082348782.44626648594692.120872973
2348221.59159274594992.195985037
#Sta/Elev= 30
       0  3430.7    67.8 3417.48   283.8 3380.85   301.8 3378.02   337.8 3375.38
   375.8  3366.9   432.3  3364.1   538.7  3364.5   569.13361.016     589 3361.03
   607.1 3361.07   620.7 3362.62     648 3359.56   652.5 3359.96     657 3362.65
   674.7 3377.45   693.3 3389.79   716.1 3406.84   734.2 3422.26   747.8 3428.94
   779.5 3447.93   793.1 3454.46   797.7  3458.1   815.8 3479.14   851.8  3500.2
   874.8 3509.19   911.1 3520.31   924.7 3523.45   934.8 3524.18   968.4 3531.76
#Mann= 7 ,-1,0
       0      .1       0      20     .12       0     230     .06       0
  352.36     .12       0   569.1    .045       0     589     .12       0
  802.36      .1       0
#XS Ineff= 2 , 0
          537.76 3368.83
Permanent Ineff=
       F       F
Bank Sta=569.1,589
XS Rating Curve= 0 ,0
Exp/Cntr(USF)=0,0
Exp/Cntr=0.3,0.1

Type RM Length L Ch R = 1 ,80396   ,253.8,240.2,222.1
XS GIS Cut Line= 3
2348813.08231529594265.5798038422348321.38021874594615.281725959
2348204.81291136594920.476130715
#Sta/Elev= 30
       0 3443.51    82.1 3425.98   133.6 3417.83   158.1  3411.4     227  3397.6
   249.9  3387.3   282.3 3366.06   290.7 3362.95   327.4 3360.44   374.2 3362.27
   447.8 3360.03   467.4 3362.95   479.4  3356.4   508.1 3356.59   551.1 3355.73
   568.3 3356.44   585.9 3358.88   603.4 3357.36   635.4 3359.02   648.2 3362.83
   686.3 3389.03   711.1 3403.69   742.4 3420.96   760.7 3429.24   794.8 3446.79
   815.2 3459.42   841.3  3472.6     866 3487.18   918.7 3509.68   930.1 3512.02
#Mann= 9 ,-1,0
       0      .1       0     240     .12       0     410     .06       0
     420     .12       0   508.1    .045       0   568.3     .12       0
     580      .1       0  693.38     .12       0  733.38      .1       0
#XS Ineff= 2 , 0
          465.77    3365
Permanent Ineff=
       F       F
Bank Sta=508.1,568.3
XS Rating Curve= 0 ,0
Exp/Cntr(USF)=0,0
Exp/Cntr=0.3,0.1

Type RM Length L Ch R = 1 ,80156   ,366.3,345.3,328.6
XS GIS Cut Line= 3
2348460.93721784594038.385807404 2348110.8495871594592.095835618
2348066.19555257594879.667818013
#Sta/Elev= 30
       0 3456.34    43.2 3441.74    60.1 3434.56    91.2 3423.77   192.6 3395.44
   263.5 3364.63   272.2 3361.89   287.3 3359.86   308.3 3361.45   386.6 3359.74
   391.4 3359.36   408.5 3353.45   435.6 3352.07   443.3 3353.47   452.9 3355.07
   528.6  3355.9   542.8 3355.64   561.7 3352.87   575.9 3355.44   604.3 3357.06
   617.2 3363.07     628 3364.72   655.1 3373.12   708.8 3394.62   789.8 3434.42
     810 3446.29   870.7 3473.74   882.9 3476.53     895 3481.58   946.1 3497.81
#Mann= 6 ,-1,0
       0      .1       0     200     .12       0     320     .06       0
   408.5    .045       0   443.3     .12       0   765.1      .1       0
Bank Sta=408.5,443.3
XS Rating Curve= 0 ,0
Exp/Cntr(USF)=0,0
Exp/Cntr=0.3,0.1

Type RM Length L Ch R = 1 ,79811   ,343.1,347,352
XS GIS Cut Line= 3
2347967.59250457594066.1093325882347910.44776145594539.267805664
2347931.01986897594767.846778165
#Sta/Elev= 30
       0 3442.55    11.2 3436.18    23.2 3431.09    31.3 3425.41      50  3415.3
    59.5  3409.4    75.6 3401.82   111.9  3381.7   123.3 3374.35   136.1 3369.86
   152.2 3361.83   192.1 3349.83     200  3349.3   212.6 3351.34   228.7 3351.91
     273 3350.02   309.3 3351.92   333.5 3349.18   345.6 3350.19  360.32 3348.81
   373.8 3348.01   384.23348.862   401.3 3349.85   418.1 3353.22   482.5 3353.27
   490.6 3354.84   510.6 3365.67   566.9 3389.53     595 3403.47   706.1 3448.08
#Mann= 7 ,-1,0
       0     .12       0      50      .1       0     150     .06       0
     240     .12       0  360.32    .045       0   384.2     .12       0
   546.6      .1       0
Bank Sta=360.32,384.2
XS Rating Curve= 0 ,0
Exp/Cntr(USF)=0,0
Exp/Cntr=0.3,0.1

Type RM Length L Ch R = 1 ,79464   ,280,294.1,299.1
XS GIS Cut Line= 3
2347700.26467037593996.1073675082347572.65772897594436.221104191
2347568.75139403594850.292607935
#Sta/Elev= 30
       0 3472.16    80.2  3431.6   109.4 3418.27   134.4 3409.52     151 3401.05
   165.7 3395.61   180.2 3387.33   209.4 3373.45   221.8 3365.94   255.2 3352.43
   265.7 3344.23   275.4    3343   294.7 3344.37   313.5 3345.37   356.1  3344.6
   384.3 3347.21   434.2 3346.95   446.7 3347.99   463.2 3347.17   479.2 3344.48
   515.3 3345.69   539.2 3351.65   563.2 3351.81   591.2 3356.38   683.2 3388.96
   735.2 3408.97   771.2 3424.63   787.2 3429.44   834.3  3448.3   872.3 3465.04
#Mann= 9 ,-1,0
       0     .12       0      60      .1       0     120     .06       0
     220     .12       0   265.7    .045       0   294.7     .12       0
     330      .1       0     430     .12       0  828.24      .1       0
#XS Ineff= 2 , 0
                          444.51         3354.42
Permanent Ineff=
       F       F
Bank Sta=265.7,294.7
XS Rating Curve= 0 ,0
Exp/Cntr(USF)=0,0
Exp/Cntr=0.3,0.1

Type RM Length L Ch R = 1 ,79170   ,171.4,184.3,198.3
XS GIS Cut Line= 3
2347550.43587976593976.9635333132347294.42743056594344.975679039
2347221.28215936594731.274142565
#Sta/Elev= 30
       0 3452.43      39 3434.17      67 3419.14    76.5 3416.11   102.6 3402.98
     127 3392.38   159.8 3380.65   170.8 3378.14   248.8 3354.01   273.1 3340.93
     280 3339.95   345.23340.062   360.8 3338.76   368.2 3339.96   385.2 3343.36
   421.3 3345.38   464.8 3345.72   501.4 3343.18   525.9 3343.83   538.1 3342.28
   573.6 3342.97   639.8 3358.92   713.1 3380.98   766.1  3395.1   786.4 3403.52
   802.7 3408.89   810.8  3413.2     823  3416.8   835.3  3423.2   841.5 3424.85
#Mann= 5 ,-1,0
       0      .1       0     110     .06       0     280     .12       0
   345.2    .045       0   368.2     .12       0
#XS Ineff= 2 , 0
                          431.55         3353.42
Permanent Ineff=
       F       F
Bank Sta=345.2,368.2
XS Rating Curve= 0 ,0
Exp/Cntr(USF)=0,0
Exp/Cntr=0.3,0.1

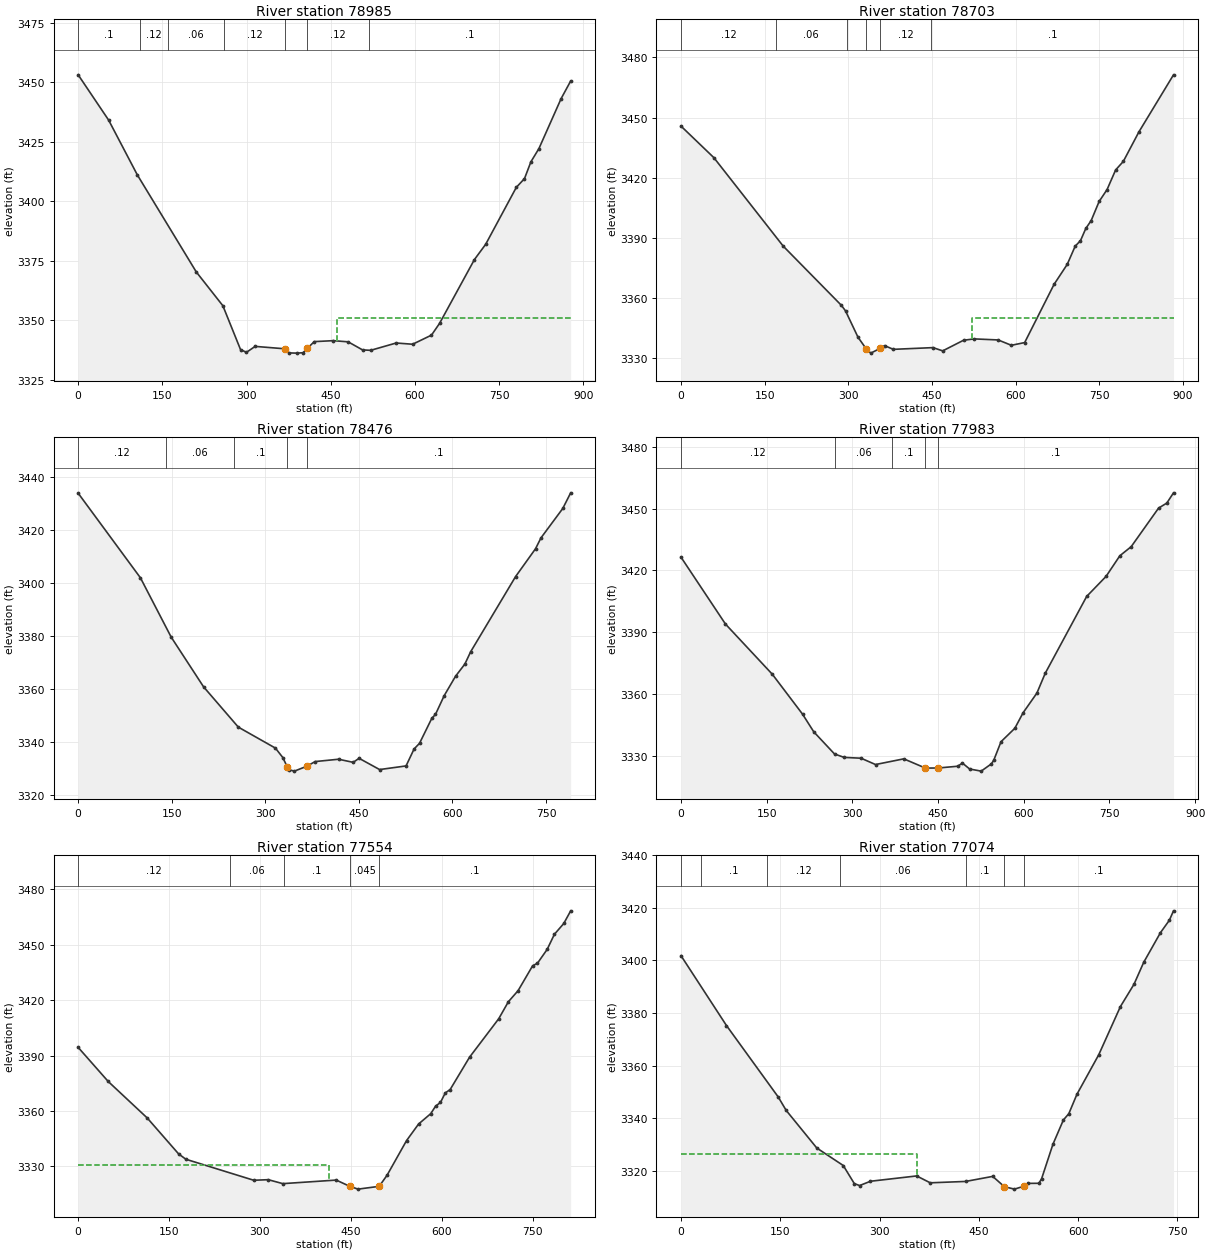
Type RM Length L Ch R = 1 ,78985   ,288.5,282,271.9
XS GIS Cut Line= 3
2347456.76979238593893.2405473952347249.73404051594135.433313736
2346803.10974559 594471.37811866
#Sta/Elev= 30
       0 3453.08    54.3 3434.07   105.4 3411.09   210.4 3370.37   257.8 3356.18
   289.3 3337.77   299.9 3336.63   315.3 3339.12   368.1 3338.11   375.6 3336.38
   389.5 3336.29   400.7 3336.46     408 3338.24   420.7 3341.12   454.6 3341.52
     481 3341.03   506.7 3337.64   521.2 3337.47   566.6 3340.54   595.9 3340.02
   629.5 3343.84   643.8 3348.74     706 3375.56     726 3381.95   780.7 3405.88
   795.2 3409.52   806.6 3416.56   820.9 3422.12   860.5 3443.12   877.5 3450.49
#Mann= 7 ,-1,0
       0      .1       0     110     .12       0     160     .06       0
     260     .12       0   368.1    .045       0     408     .12       0
  518.62      .1       0
#XS Ineff= 2 , 0
                          460.28         3350.95
Permanent Ineff=
       F       F
Bank Sta=368.1,408
XS Rating Curve= 0 ,0
Exp/Cntr(USF)=0,0
Exp/Cntr=0.3,0.1

Type RM Length L Ch R = 1 ,78703   ,214.1,227.3,239.2
XS GIS Cut Line= 4
2347323.14018651 593727.25078434 2347102.7220053593894.683825839
2347005.22934822594023.9675667432346632.21396463594265.579803842
#Sta/Elev= 30
       0 3445.76      59 3429.99   183.3 3385.85   287.7 3356.28     295 3353.55
   317.5 3340.35   331.8 3334.72   340.4 3332.45   357.5 3334.88   365.1  3336.2
   380.7 3334.34   451.9  3335.2   469.3 3333.58   506.7 3338.88   525.8 3339.55
   568.7 3339.03   592.5 3336.36   616.3 3337.72     669 3366.77   692.6 3376.74
   706.9 3385.84   716.4 3388.58   725.9 3394.66   735.5 3398.57   749.8 3408.13
   764.1 3414.11   779.4 3423.87   793.2 3428.14   821.2 3442.89   883.2 3471.35
#Mann= 6 ,-1,0
       0     .12       0     170     .06       0   296.8     .12       0
   331.8    .045       0   357.5     .12       0  448.72      .1       0
#XS Ineff= 2 , 0
                          522.25         3349.75
Permanent Ineff=
       F       F
Bank Sta=331.8,357.5
XS Rating Curve= 0 ,0
Exp/Cntr(USF)=0,0
Exp/Cntr=0.3,0.1

Type RM Length L Ch R = 1 ,78476   ,485.9,493.3,499.3
XS GIS Cut Line= 2
2347207.07758717593602.7588731652346535.76800482594018.353873884
#Sta/Elev= 30
       0 3433.79    99.8 3401.92   149.1 3379.58     201 3360.86   256.7 3345.68
   316.2 3337.77     328 3334.23   334.9 3330.83     338  3329.6   346.7  3329.1
   367.1    3331   379.8  3332.7   417.4 3333.58   440.9 3332.41   450.3 3333.93
   483.2 3329.69   525.6 3331.06   538.5 3337.46   547.2 3339.58   566.9    3349
   572.7 3350.44   586.8 3357.56   604.9 3364.83   619.9 3369.44   629.1 3374.04
   701.2 3402.39   733.2 3412.89   741.9 3416.97   776.8 3428.03   789.5 3433.93
#Mann= 5 ,-1,0
       0     .12       0     140     .06       0     250      .1       0
   334.9    .045       0   367.1      .1       0
Bank Sta=334.9,367.1
XS Rating Curve= 0 ,0
Exp/Cntr=0.3,0.1

Type RM Length L Ch R = 1 ,77983   ,415,429.3,451.1
XS GIS Cut Line= 3
2347050.51095852593252.6016170742346519.24940655593433.595136006
2346270.54608197593602.869650116
#Sta/Elev= 30
       0 3426.47    77.9    3394   159.9 3369.65   212.7 3350.34   232.4 3341.74
   268.7    3331   285.6 3329.33   315.2 3328.93   340.5 3325.87     390 3328.63
   427.8 3324.15   450.4 3324.19   484.2 3325.04   492.7 3326.56   505.3 3323.69
   525.5 3322.67   543.4 3326.21   547.6 3328.05   560.2 3336.95   584.3 3343.43
   598.8 3350.97     623 3360.54   637.5 3370.11   710.1 3407.42     744 3417.13
   768.2 3427.16     788 3431.55   835.9 3450.25   850.4 3452.72   862.1 3457.68
#Mann= 5 ,-1,0
       0     .12       0     270     .06       0     370      .1       0
   427.8    .045       0   450.4      .1       0
Bank Sta=427.8,450.4
XS Rating Curve= 0 ,0
Exp/Cntr(USF)=0,0
Exp/Cntr=0.3,0.1

Type RM Length L Ch R = 1 ,77554   ,470.6,479.2,485.2
XS GIS Cut Line= 2
2346941.76255823593052.0964024622346129.36348999593029.500844227
#Sta/Elev= 30
       0 3394.42    49.6 3375.96   113.9 3356.23   165.7 3336.77   177.7 3333.87
   289.7 3322.49   313.7  3322.8   337.7 3320.66   425.8 3322.59   448.2  3319.2
   461.8 3317.69   496.7  3319.2   509.8 3325.26   541.9 3343.98   561.8 3352.97
   581.8 3358.54   589.8 3362.63   597.8  3364.6   605.8 3369.78   613.8 3371.59
   645.8  3389.1   693.9  3409.9   709.9 3419.14   725.9 3425.12   749.9  3438.6
   757.9 3439.98   773.9 3447.48   785.9 3455.68   801.3 3461.49   812.7 3468.35
#Mann= 5 ,-1,0
       0     .12       0     250     .06       0     340      .1       0
   448.2    .045       0   496.7      .1       0
#XS Ineff= 2 , 0
          413.52 3330.75
Permanent Ineff=
       F       F
Bank Sta=448.2,496.7
XS Rating Curve= 0 ,0
Exp/Cntr=0.3,0.1

Type RM Length L Ch R = 1 ,77074   ,339.7,344.7,346.1
XS GIS Cut Line= 2
2347019.09190282592684.4945285782346294.02666916592516.731238482
#Sta/Elev= 30
       0 3401.83    68.7 3375.29   146.7 3348.22     159 3343.03   205.2 3328.76
   245.2 3322.11   261.9 3315.23   269.9  3314.5   286.3 3316.13   356.1 3318.15
   376.6 3315.54     430 3316.06     471 3317.98   488.7 3314.05   503.9 3313.14
   517.6 3314.21   524.4 3315.32   540.8 3315.36   544.9  3317.1     562 3330.17
   577.8 3339.41     586  3341.8   598.3 3349.18   631.2 3364.17     664  3382.5
   684.5 3390.96   699.2 3399.31   724.5 3410.57   737.9 3415.27   744.2 3418.86
#Mann= 7 ,-1,0
       0     .12       0      30      .1       0     130     .12       0
     240     .06       0     430      .1       0   488.7    .045       0
   517.6      .1       0
#XS Ineff= 2 , 0
          356.06 3326.38
Permanent Ineff=
       F       F
Bank Sta=488.7,517.6
XS Rating Curve= 0 ,0
Exp/Cntr=0.3,0.1

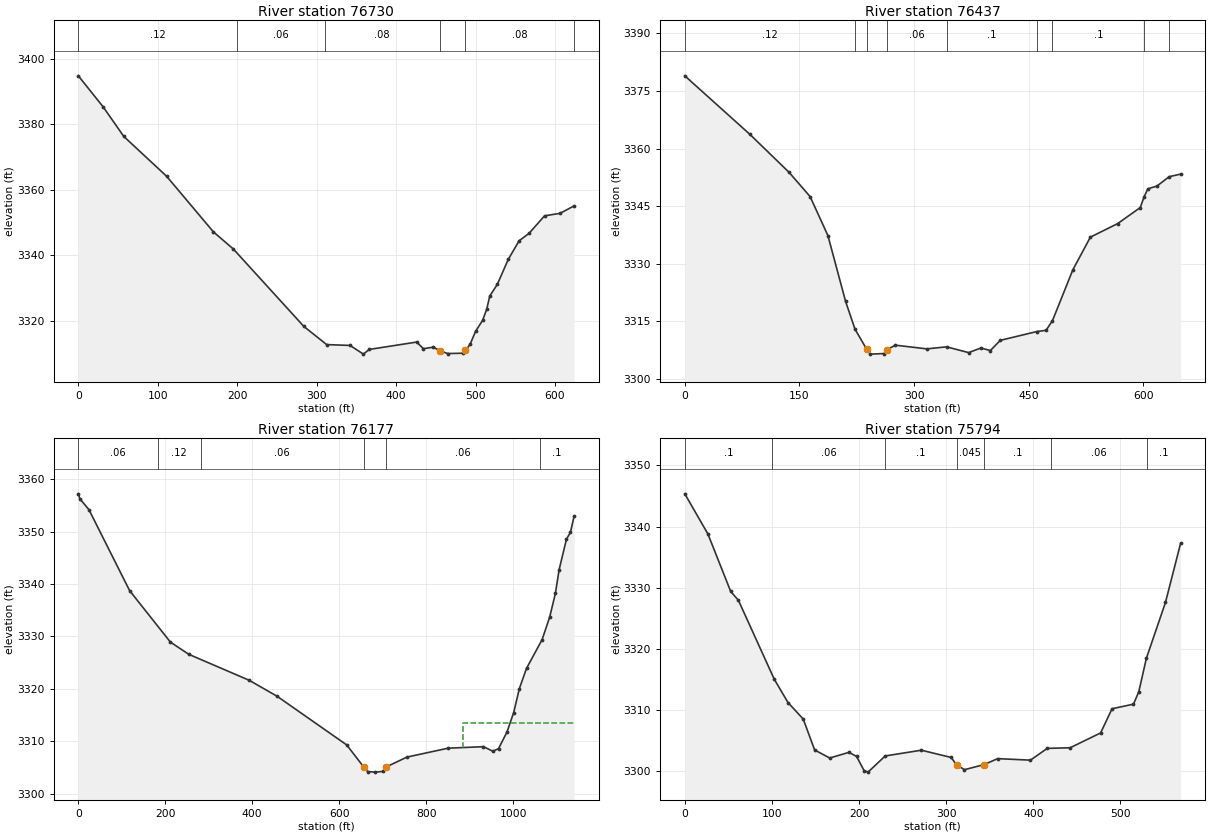
Type RM Length L Ch R = 1 ,76730   ,312.9,292.5,260
XS GIS Cut Line= 3
2347086.14832198592395.0578400762346592.54383884592238.433340617
2346499.51837855592289.692267713
#Sta/Elev= 30
       0 3394.86    31.4 3385.32    57.2 3376.34   111.2 3364.14   169.9 3347.19
   195.1 3341.92   283.9 3318.25   312.6  3312.7     342 3312.45   358.8 3309.79
   366.2 3311.22   425.9 3313.48   434.3 3311.45   446.9 3311.92     455 3310.84
     465 3309.97   484.1 3310.07   487.3  3310.9   493.1 3312.77     500 3316.75
   508.8 3320.08     514 3323.49   517.9 3327.56   527.4 3331.12   541.1 3338.73
   554.8 3344.43   567.3  3346.7   586.8 3352.06   606.4 3352.83   624.1 3355.12
#Mann= 6 ,-1,0
       0     .12       0     200     .06       0     310     .08       0
     455    .045       0   487.3     .08       0  624.07      .1       0
Bank Sta=455,487.3
XS Rating Curve= 0 ,0
Exp/Cntr(USF)=0,0
Exp/Cntr=0.3,0.1

Type RM Length L Ch R = 1 ,76437   ,278.2,260.6,233.3
XS GIS Cut Line= 3
2346990.27514352591891.0117236372346618.17330238592106.489065316
2346490.02598464592283.996831369
#Sta/Elev= 30
       0 3378.97    85.1 3363.74   136.5 3353.82     164 3347.51   187.3 3337.35
   210.4 3320.23   222.7 3312.99   238.2 3307.68   242.8 3306.47   260.7 3306.62
  264.57 3307.63   275.7  3308.8   316.7 3307.84   342.7 3308.37   371.5 3306.86
   387.5 3308.07   399.9  3307.4   412.9 3310.06   460.7 3312.35   472.8 3312.68
   481.2  3315.2   507.8 3328.41   530.8 3336.95   566.5 3340.47   596.1 3344.66
     601 3347.39     606 3349.53   617.9 3350.25   633.9 3352.69   648.9 3353.37
#Mann= 9 ,-1,0
       0     .12       0   222.7     .06       0   238.2    .045       0
  264.57     .06       0   342.7      .1       0   460.7     .06       0
   481.2      .1       0     601     .08       0   633.9      .1       0
Bank Sta=238.2,264.57
XS Rating Curve= 0 ,0
Exp/Cntr(USF)=0,0
Exp/Cntr=0.3,0.1

Type RM Length L Ch R = 1 ,76177   ,422.2,382.5,347.1
BEGIN DESCRIPTION:
low water course crossing/washed out road crossing
END DESCRIPTION:
XS GIS Cut Line= 6
2347059.62574005591488.2403353992346833.16623825591554.087793965
2346751.15613432591589.3867377762346699.74095817591624.901993807
2346641.84067137591714.1469671532346388.50567819592308.785521426
#Sta/Elev= 30
       0 3357.22     3.6 3356.26    24.4  3354.2     118 3338.74   211.9 3328.91
   254.3 3326.58   393.3 3321.62   456.9  3318.6   617.4 3309.29   656.9 3305.04
   665.5 3304.21     682  3304.1   699.9 3304.22   708.5  3305.1   755.9 3306.97
   850.6 3308.67     932 3308.96   953.5 3308.09   966.6 3308.58   986.1 3311.76
  1001.5 3315.47  1014.6 3320.06    1031  3323.9  1066.9  3329.4  1084.3 3333.69
  1097.4  3338.2  1106.1 3342.77  1122.9 3348.57    1132 3349.86  1140.6    3353
#Mann= 6 ,-1,0
       0     .06       0     183     .12       0   281.3     .06       0
   656.9    .045       0   708.5     .06       0  1061.2      .1       0
#XS Ineff= 2 , 0
                          885.63         3313.49
Permanent Ineff=
       F       F
Bank Sta=656.9,708.5
XS Rating Curve= 0 ,0
Exp/Cntr(USF)=0,0
Exp/Cntr=0.3,0.1

Type RM Length L Ch R = 1 ,75794   ,213.4,227,235.8
XS GIS Cut Line= 2
2346116.97490412591760.9659271162346347.64007605592281.149113197
#Sta/Elev= 30
       0 3345.36    26.5 3338.79    52.7 3329.37    61.5 3327.93   102.6 3315.02
   118.4 3311.19   135.9 3308.48     149 3303.42   166.3  3302.1   188.4 3303.03
   197.1 3302.36   205.7 3300.05   210.3 3299.79     230 3302.44   271.5 3303.38
   305.7 3302.19   311.8 3300.99   320.9 3300.19   343.4 3301.02     359    3302
   396.7 3301.75   415.9 3303.68   442.2 3303.78   477.2 3306.21   490.3 3310.17
   514.9 3310.92     521 3312.95   529.7 3318.43   551.6 3327.57     569 3337.27
#Mann= 7 ,-1,0
       0      .1       0     100     .06       0     230      .1       0
   311.8    .045       0   343.4      .1       0     420     .06       0
     530      .1       0
Bank Sta=311.8,343.4
XS Rating Curve= 0 ,0
Exp/Cntr(USF)=0,0
Exp/Cntr=0.3,0.1