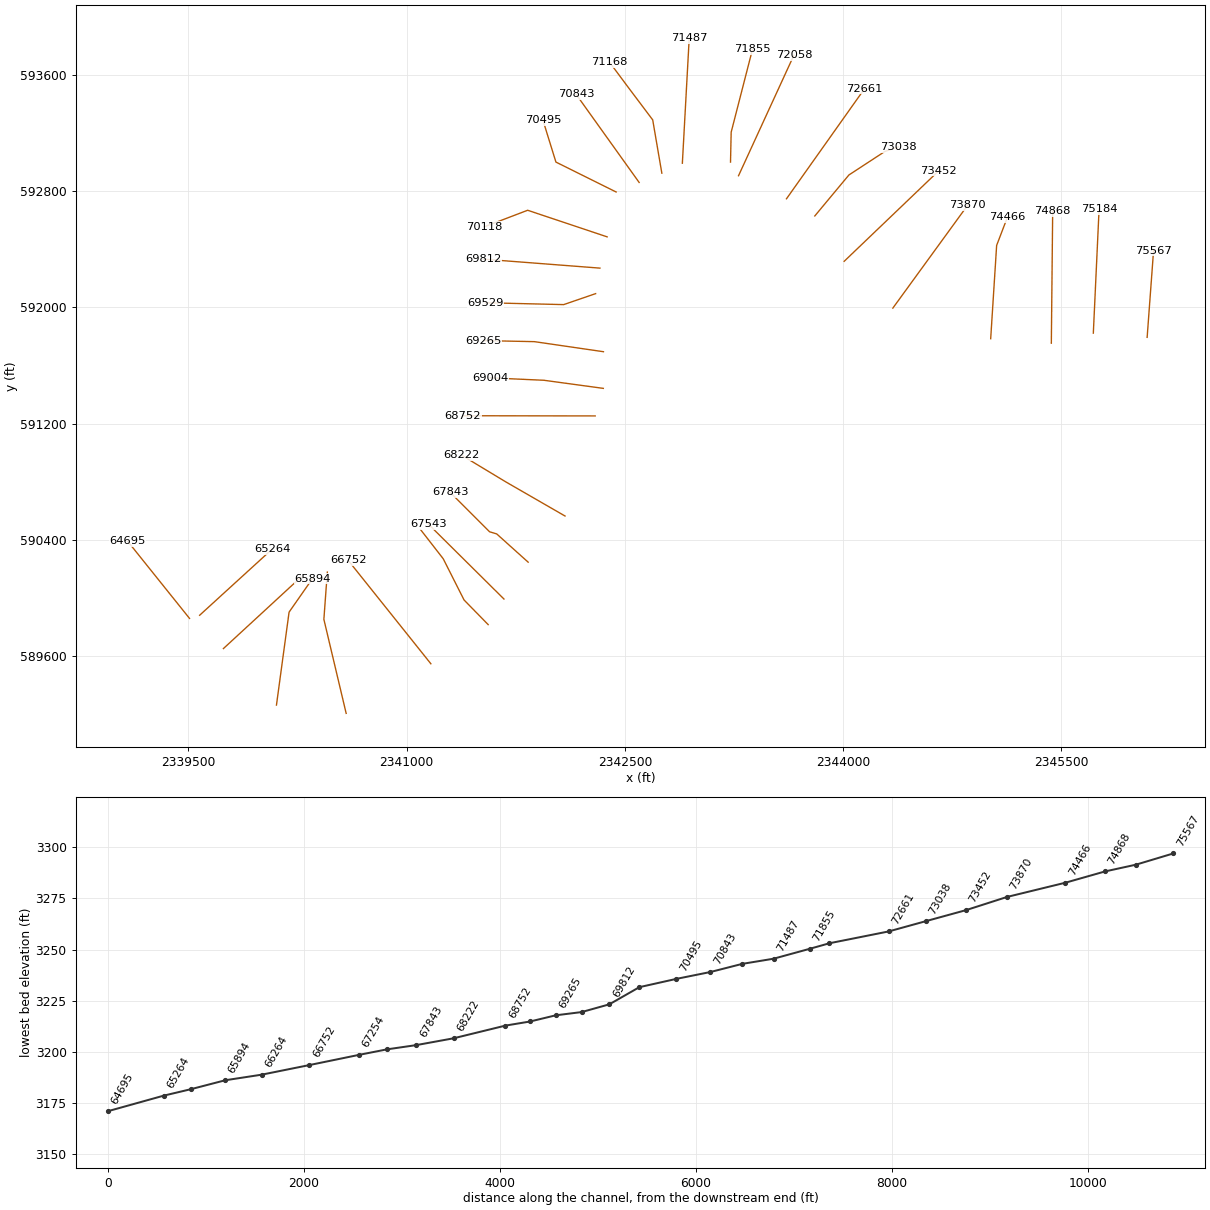
HEC-RAS study EFGRNBRRRV.prj: EFGRNBRRRV

--- EFGRNBRRRV.g01 (geometry) --- (continued)

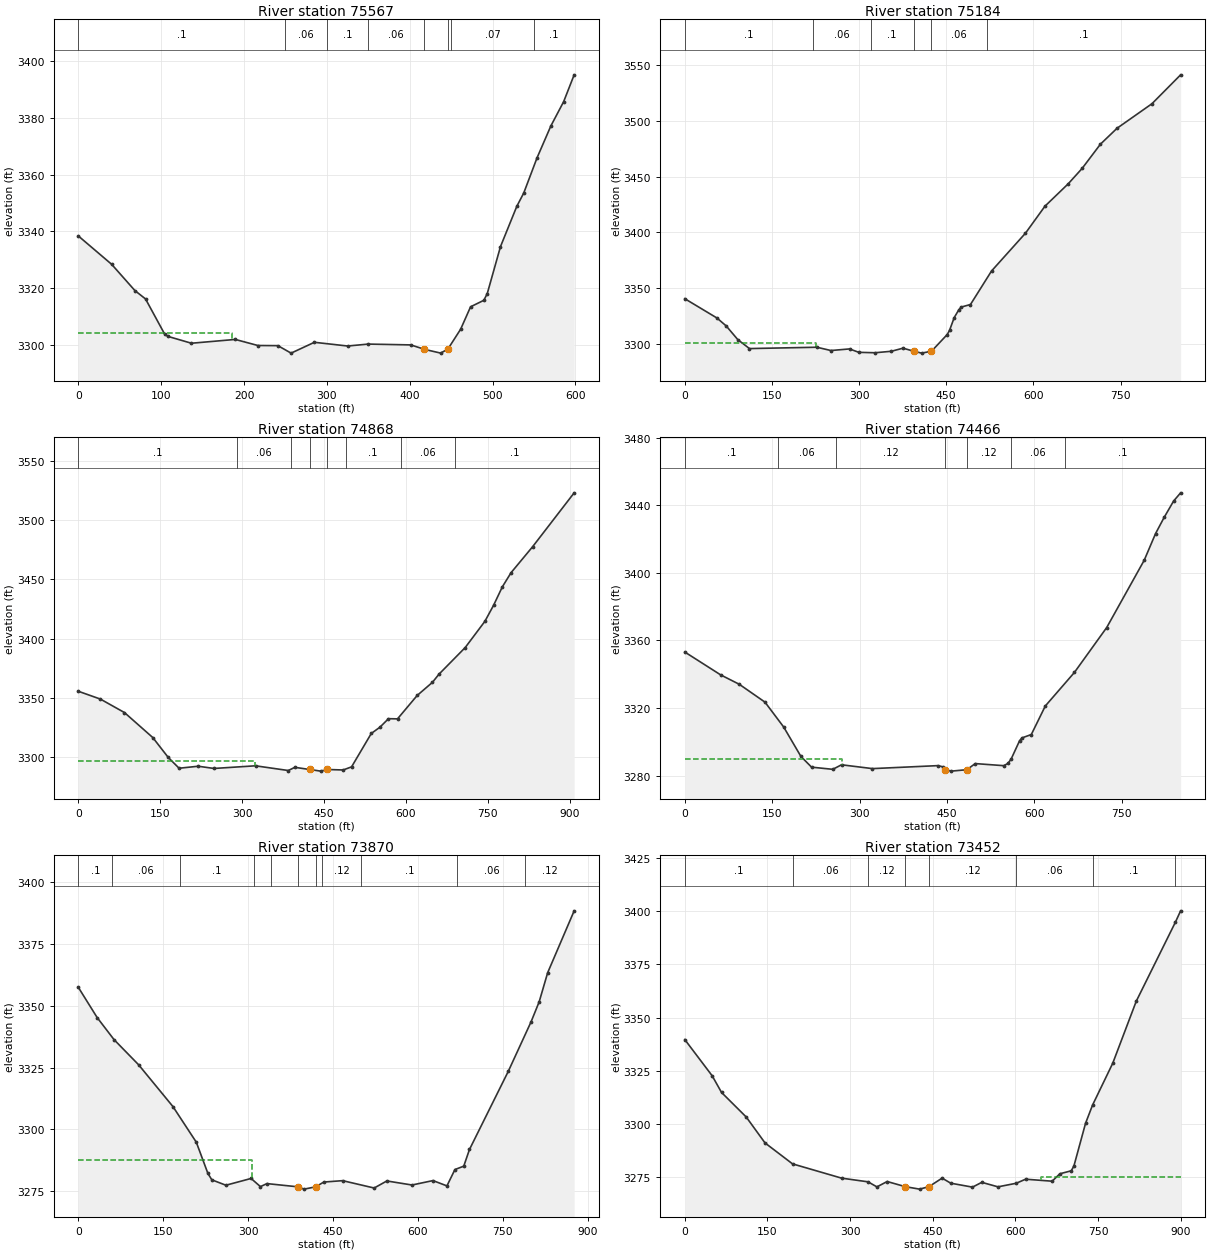
Type RM Length L Ch R = 1 ,75567   ,382.3,383.1,384.1
XS GIS Cut Line= 2
2346089.46587311591793.0645359712346133.61137304592389.789914269
#Sta/Elev= 30
       0 3338.36    40.2 3328.36    68.3 3319.08    81.1 3316.14   104.4 3303.61
   108.4  3302.9   136.5 3300.51   189.4 3301.85   216.7 3299.71   240.8 3299.66
   256.8 3297.02   284.9 3300.84     325 3299.53     350 3300.21   401.2 3299.92
   417.3 3298.41   417.3 3298.38   437.3 3297.03     4463298.448   461.4 3305.46
   473.4 3313.37   489.4 3315.66   493.5 3318.01   509.5 3334.61   529.2 3348.83
   537.6 3353.54   553.6 3365.92   570.3 3377.18   585.7 3385.73   598.4 3395.21
#Mann= 8 ,-1,0
       0      .1       0     250     .06       0     300      .1       0
     350     .06       0   417.3    .045       0     446     .06       0
     450     .07       0     550      .1       0
#XS Ineff= 2 , 0
          185.39 3304.15
Permanent Ineff=
       F       F
Bank Sta=417.3,446
XS Rating Curve= 0 ,0
Exp/Cntr(USF)=0,0
Exp/Cntr=0.3,0.1

Type RM Length L Ch R = 1 ,75184   ,312.2,315.6,314.8
XS GIS Cut Line= 2
2345719.55702891591821.9874497152345759.13575298592674.452275855
#Sta/Elev= 30
       0 3340.36    55.3 3323.05    71.3  3315.9    91.3  3303.6   111.3  3295.6
   227.4  3296.8   251.5 3293.84   283.5 3295.28   299.5 3292.23   327.5 3291.85
   355.6 3293.18   375.6 3295.96     394 3293.23   407.6 3291.51   424.6 3293.21
   451.7 3308.21   455.7 3311.98   463.7 3323.41   471.7 3330.46   475.7 3332.84
   491.7 3335.15   527.9  3365.2   586.4  3399.2   619.9  3423.4   659.9 3443.47
   683.9 3457.33   715.4 3479.07     744 3493.36   804.1 3515.39   853.4 3541.31
#Mann= 6 ,-1,0
       0      .1       0     220     .06       0     320      .1       0
     394    .045       0   424.6     .06       0     520      .1       0
#XS Ineff= 2 , 0
          226.25 3300.58
Permanent Ineff=
       F       F
Bank Sta=394,424.6
XS Rating Curve= 0 ,0
Exp/Cntr(USF)=0,0
Exp/Cntr=0.3,0.1

Type RM Length L Ch R = 1 ,74868   ,402.8,402.8,399.5
XS GIS Cut Line= 2
2345430.91070064 591752.678767062345440.15893085592660.679511374
#Sta/Elev= 30
       0 3355.63    40.5 3349.01    84.5 3337.65   136.4 3316.52   164.5 3299.85
   184.5 3290.64   219.5 3292.33   248.5 3290.46   324.5 3292.69   384.5 3288.72
   396.5 3291.41   423.6 3289.58   443.8  3288.2   455.9 3289.58   484.9 3289.17
   500.4 3291.81   536.5 3320.01   552.2 3325.25     568 3332.48   584.5 3332.32
   620.5 3352.07   648.5 3363.19   660.5 3370.07   708.5 3392.55   744.5 3414.67
   760.5 3428.27   776.5 3443.81   792.5 3455.79   831.8  3477.6     908 3523.18
#Mann= 8 ,-1,0
       0      .1       0     290     .06       0     390     .08       0
   423.6    .045       0   455.9     .08       0     490      .1       0
     590     .06       0     690      .1       0
#XS Ineff= 2 , 0
          323.63 3297.03
Permanent Ineff=
       F       F
Bank Sta=423.6,455.9
XS Rating Curve= 0 ,0
Exp/Cntr=0.3,0.1

Type RM Length L Ch R = 1 ,74466   ,608.8,595.6,566.8
XS GIS Cut Line= 3
2345014.06962693591783.8131628752345054.95363575592425.457331951
2345129.22126636592619.554509769
#Sta/Elev= 30
       0 3353.15    61.5 3339.64    93.6 3334.05   137.6 3323.51   169.7 3308.78
   199.2 3291.43   217.5 3285.06   253.9 3283.78   268.9 3286.46     322  3284.2
   434.2 3285.96   442.3 3285.31   446.3 3283.64   457.3 3282.71  483.97 3283.55
   498.4 3287.17   547.2 3285.94   554.5 3287.24     560 3289.87   574.5 3300.71
   578.5 3302.35   594.6 3304.36   618.6 3321.23   668.5 3341.06     724 3367.65
   788.3 3407.41   807.8  3423.2   822.5 3432.76   838.8 3442.46   850.8  3447.3
#Mann= 7 ,-1,0
       0      .1       0     160     .06       0     260     .12       0
   446.3    .045       0  483.97     .12       0     560     .06       0
  652.95      .1       0
#XS Ineff= 2 , 0
          269.91 3289.65
Permanent Ineff=
       F       F
Bank Sta=446.3,483.97
XS Rating Curve= 0 ,0
Exp/Cntr=0.3,0.1

Type RM Length L Ch R = 1 ,73870   ,420.7,418.3,407.8
XS GIS Cut Line= 2
2344341.57386261591994.2398826182344856.71632575592703.055069153
#Sta/Elev= 30
       0 3357.49    33.3 3345.24      63 3336.34   106.5 3326.13   167.2 3309.19
   208.5 3294.75     229 3282.09   235.9 3279.52   260.8 3277.33   305.3 3280.07
   321.8 3276.76   333.3 3277.99   387.7 3276.69   399.1 3275.75   419.5 3276.69
   433.8 3278.62   467.1 3279.18   522.8  3276.2   545.2 3279.06   589.6 3277.42
   626.7 3279.21   651.4 3277.06   665.5 3283.69   681.1 3285.05   691.2 3291.81
   759.7 3323.43   800.1 3343.55   814.4 3351.65   829.4 3363.43   876.2 3388.49
#Mann= 11 ,-1,0
       0      .1       0      60     .06       0     180      .1       0
     310     .12       0     340      .1       0   387.7    .045       0
   419.5      .1       0     430     .12       0     500      .1       0
     670     .06       0     790     .12       0
#XS Ineff= 2 , 0
          306.48 3287.61
Permanent Ineff=
       F       F
Bank Sta=387.7,419.5
XS Rating Curve= 0 ,0
Exp/Cntr=0.3,0.1

Type RM Length L Ch R = 1 ,73452   ,421.1,413.5,403.5
XS GIS Cut Line= 2
2344006.99956051592316.0596487662344656.71672157592938.416813466
#Sta/Elev= 30
       0 3339.67    49.7 3322.62    66.7 3314.78   111.5 3303.23   145.6 3291.04
   195.5 3281.19   284.5 3274.48   332.6 3272.74   348.6 3270.36   367.2 3272.89
   400.4 3270.45     426 3269.31     443 3270.47   466.9 3274.48   482.6  3272.1
     522 3270.25   538.9  3272.5   568.3 3270.39   601.4 3272.07   618.4 3273.98
   666.6 3273.04   680.6 3276.54   701.3 3277.94   706.1 3280.23   727.2  3300.3
     740 3308.91   776.5 3328.52   819.2 3357.72     890 3394.78   899.7 3400.24
#Mann= 8 ,-1,0
       0      .1       0   195.5     .06       0   332.6     .12       0
   400.4    .045       0     443     .12       0   601.4     .06       0
     740      .1       0     890     .12       0
#XS Ineff= 2 , 0
                           646.7            3275
Permanent Ineff=
       F       F
Bank Sta=400.4,443
XS Rating Curve= 0 ,0
Exp/Cntr=0.3,0.1

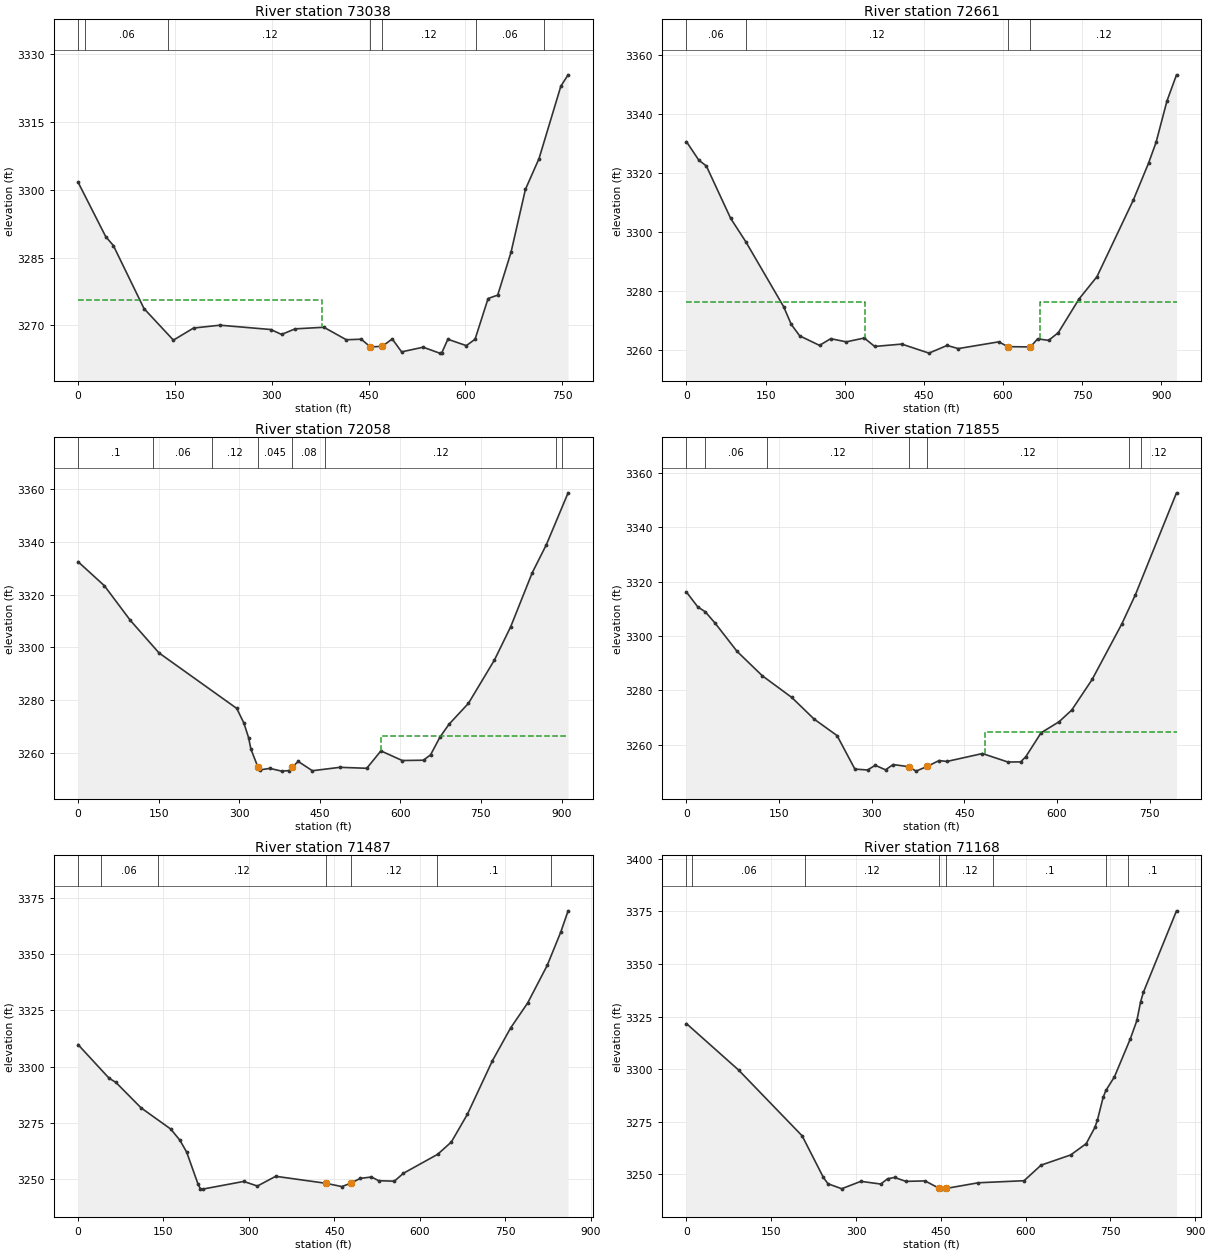
Type RM Length L Ch R = 1 ,73038   ,357.1,377,392.5
XS GIS Cut Line= 4
2343805.20252497592628.1976702942344039.50240598592909.897081827
2344286.10830211593071.2564953462344378.82569728593102.781792086
#Sta/Elev= 30
       0 3301.69    42.9 3289.63    54.7 3287.67   102.2 3273.72   147.7 3266.74
   178.9 3269.42   219.8 3270.05   298.6 3269.09   315.2    3268   336.2 3269.24
   380.8 3269.59   415.5 3266.83   438.6 3266.95   452.8 3265.25470.99263265.365
   486.7 3267.01   501.1 3264.15   534.5 3265.18     560 3263.87   563.2 3263.89
   572.8 3266.94   601.4 3265.53   614.9 3266.94   635.1 3275.95     650 3276.71
   670.6 3286.17   692.9 3300.09     714 3306.91   747.8 3322.93     759 3325.43
#Mann= 7 ,-1,0
       0      .1       0      10     .06       0     140     .12       0
   452.8    .045       0470.9926     .12       0   616.4     .06       0
  721.11      .1       0
#XS Ineff= 2 , 0
          378.14 3275.57
Permanent Ineff=
       F       F
Bank Sta=452.8,470.9926
XS Rating Curve= 0 ,0
Exp/Cntr(USF)=0,0
Exp/Cntr=0.3,0.1

Type RM Length L Ch R = 1 ,72661   ,606,603.1,612.2
XS GIS Cut Line= 2
2343610.38827752592746.0903958152344147.35894995593503.986977253
#Sta/Elev= 30
       0  3330.7    23.4 3324.41    37.7 3322.44    83.8 3304.64   112.5  3296.7
   184.3 3274.62   198.6 3268.65   214.6 3264.75   252.2 3261.51   273.4 3263.79
   302.8 3262.71   337.1 3264.01   356.7 3261.15   408.1 3261.95   459.7 3258.88
     494 3261.49   515.1 3260.42     592 3262.72   608.9 3261.08     652 3260.99
   665.6 3263.73   686.4 3263.21   704.8 3265.84     744 3277.26     778 3284.83
     847 3310.89   875.8 3323.39   890.1 3330.48   910.7 3344.51   928.8 3353.39
#Mann= 4 ,-1,0
       0     .06       0   112.5     .12       0   608.9    .045       0
     652     .12       0
#XS Ineff= 2 , 0
          338.03 3276.18   669.2         3276.18
Permanent Ineff=
       F       F
Bank Sta=608.9,652
XS Rating Curve= 0 ,0
Exp/Cntr=0.3,0.1

Type RM Length L Ch R = 1 ,72058   ,207.8,203.1,210.9
XS GIS Cut Line= 2
2343280.84957681592904.7353000312343661.35553588 593733.74638195
#Sta/Elev= 30
       0 3332.45    48.9 3323.38    97.3 3310.24   150.7  3297.9   295.4 3276.88
   308.6 3271.38   317.4 3265.85   321.8 3261.45   334.7 3254.72   339.4 3253.61
     357 3254.16     379 3253.12     392 3253.31  399.093254.711   409.8 3256.79
   436.2 3253.27   487.4 3254.56   537.4  3254.2   563.8 3260.78   603.5 3257.14
   643.1 3257.25   656.3 3259.33   673.9 3266.08   690.6 3270.89   726.7  3278.8
   775.1 3295.21   805.3 3307.79   845.5 3328.29   871.9 3338.96   912.2 3358.54
#Mann= 8 ,-1,0
       0      .1       0     140     .06       0     250     .12       0
   334.7    .045       0  399.09     .08       0     460     .12       0
     890      .1       0     900     .12       0
#XS Ineff= 2 , 0
                          563.94         3266.53
Permanent Ineff=
       F       F
Bank Sta=334.7,399.09
XS Rating Curve= 0 ,0
Exp/Cntr(USF)=0,0
Exp/Cntr=0.3,0.1

Type RM Length L Ch R = 1 ,71855   ,358.4,367.4,374.4
XS GIS Cut Line= 3
2343225.72172005592998.645531009 2343230.2932995 593204.36660626
 2343376.5838419593773.528247787
#Sta/Elev= 30
       0 3316.16    18.5 3310.66    30.5 3308.92    46.5 3304.71    81.9 3294.38
   122.8 3285.41   170.6 3277.43   206.6 3269.51   243.8 3263.44   272.7 3251.13
   293.2  3250.8   305.7 3252.53   322.3 3250.85   334.6  3252.8   359.9 3252.01
   371.8 3250.38   390.1 3252.15     409 3254.27   421.5 3253.93   479.2 3256.84
   520.5 3253.72   541.1 3253.78   549.4 3255.67   574.2 3264.48   603.1 3268.49
   623.7 3272.79   656.8 3284.05   704.6 3304.34     727 3315.26   793.4 3352.61
#Mann= 7 ,-1,0
       0      .1       0      30     .06       0     130     .12       0
   359.9    .045       0   390.1     .12       0  715.77      .1       0
  735.77     .12       0
#XS Ineff= 2 , 0
                           482.7         3264.57
Permanent Ineff=
       F       F
Bank Sta=359.9,390.1
XS Rating Curve= 0 ,0
Exp/Cntr(USF)=0,0
Exp/Cntr=0.3,0.1

Type RM Length L Ch R = 1 ,71487   ,293.2,319,342.7
XS GIS Cut Line= 2
 2342894.7676051592990.7477215662342941.83003095593849.840606008
#Sta/Elev= 30
       0 3309.78    54.5 3294.84    66.5 3292.97   110.6 3281.69   162.7 3272.26
   178.7 3267.34   190.7 3262.02   210.7 3247.77   214.8 3245.74   218.8 3245.56
   290.9 3248.98   314.9 3246.93     347 3251.26   435.1 3248.16   463.2 3246.69
   479.1 3248.22   495.2 3250.32   515.2 3250.95   527.8 3249.31   555.3 3249.08
   571.3  3252.6   631.4 3261.03   655.4 3266.49   683.5 3278.78   727.5 3302.59
   759.4 3317.13   789.4 3328.26   823.7 3344.94   847.7 3359.88   860.4 3369.21
#Mann= 7 ,-1,0
       0      .1       0      40     .06       0     140     .12       0
   435.1    .045       0   479.1     .12       0     630      .1       0
     830     .12       0
Bank Sta=435.1,479.1
XS Rating Curve= 0 ,0
Exp/Cntr=0.3,0.1

Type RM Length L Ch R = 1 ,71168   ,327.3,325.2,324.2
XS GIS Cut Line= 4
2342753.68532639592922.4054336912342690.93612049593288.917840886
2342522.65415921593512.8184164872342394.30351078593685.378732715
#Sta/Elev= 30
       0 3321.66    92.1 3299.64   204.7 3268.34   242.2 3248.62   250.4 3245.59
   274.7 3243.23   308.6 3246.74   343.7 3245.45   355.9 3247.96   368.1 3248.59
   388.3 3246.73   422.2 3246.94   447.2 3243.42   452.2 3243.04     460  3243.4
   516.3 3246.06   597.3 3247.04   627.4 3254.43   679.7 3259.27   707.2 3264.62
   722.6 3272.36   727.2 3275.94   737.1 3286.56   742.1 3289.94   757.1 3296.32
   785.5 3314.57   796.9 3323.14   803.5 3332.02   808.3 3336.45     867 3375.22
#Mann= 8 ,-1,0
       0      .1       0      10     .06       0     210     .12       0
   447.2    .045       0     460     .12       0  541.85      .1       0
  741.93     .12       0  781.93      .1       0
Bank Sta=447.2,460
XS Rating Curve= 0 ,0
Exp/Cntr(USF)=0,0
Exp/Cntr=0.3,0.1

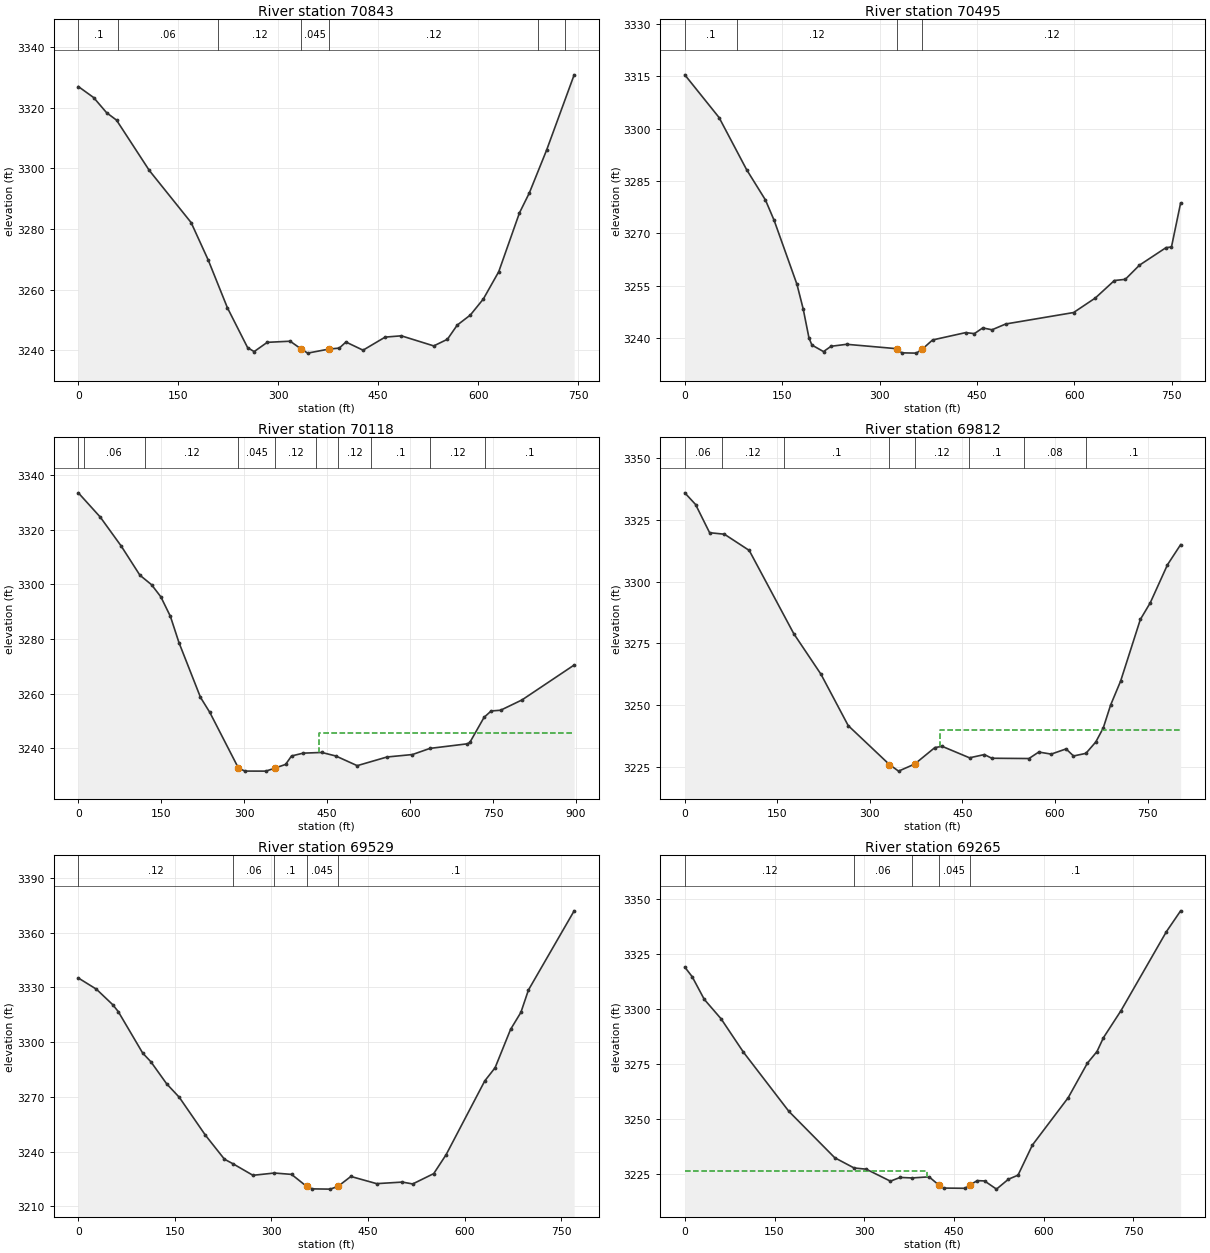
Type RM Length L Ch R = 1 ,70843   ,324.6,348.7,364
XS GIS Cut Line= 2
2342597.68862784592858.5636296672342165.06574523 593463.92765059
#Sta/Elev= 30
       0 3326.97      23 3323.33    42.5 3318.32    57.3  3315.9   106.5  3299.3
   169.3  3282.1     195 3269.73   223.7 3254.03     254 3240.89   263.8 3239.56
   283.5 3242.62   317.9 3242.99  334.343240.439   344.2 3239.06   375.7 3240.38
   391.6 3240.72   401.6 3242.72   427.3 3240.03   460.4 3244.34   484.7 3244.77
   533.4 3241.44   553.9 3243.63   568.6  3248.3   588.3 3251.62   607.8 3256.91
   630.9  3265.9     662  3285.3   676.8 3291.87   702.6 3305.92   744.1 3330.83
#Mann= 7 ,-1,0
       0      .1       0      60     .06       0     210     .12       0
  334.34    .045       0   375.7     .12       0     690      .1       0
     730     .12       0
Bank Sta=334.34,375.7
XS Rating Curve= 0 ,0
Exp/Cntr=0.3,0.1

Type RM Length L Ch R = 1 ,70495   ,372.4,376.4,377.4
XS GIS Cut Line= 3
2342439.41005464592792.9244557592342025.68211442 592998.64553101
2341936.53631514 593286.65503636
#Sta/Elev= 30
       0 3315.42    52.8 3303.18    95.1 3288.28   124.2 3279.56   137.6 3273.71
   172.7  3255.4   182.3 3248.36   191.2 3240.06   195.7 3238.01   213.6 3236.13
   225.2 3237.65   249.3 3238.22   326.5 3236.96   334.2 3235.77   356.5 3235.69
   365.5  3236.8   381.5 3239.46   432.5 3241.57   445.9 3241.28   458.8 3242.91
   473.1 3242.38   494.2 3244.04   598.7 3247.32   632.2 3251.49   661.5 3256.49
   678.3 3256.83   700.1 3260.89   741.1 3265.92   749.4 3266.09   763.5  3278.7
#Mann= 4 ,-1,0
       0      .1       0      80     .12       0   326.5    .045       0
   365.5     .12       0
Bank Sta=326.5,365.5
XS Rating Curve= 0 ,0
Exp/Cntr(USF)=0,0
Exp/Cntr=0.3,0.1

Type RM Length L Ch R = 1 ,70118   ,297.2,306.6,317
XS GIS Cut Line= 3
2342377.69373207592484.3428428832341831.38998779592667.206020884
2341531.95153382592552.916534633
#Sta/Elev= 30
       0 3333.47    39.6 3324.61    77.7 3313.95   111.3 3303.34   132.4 3299.85
   149.2 3295.42   166.5 3288.26     182 3278.66   220.9 3258.64   237.8 3253.12
   289.4  3232.8   301.1 3231.67   339.1 3231.65   355.5 3232.75   374.8 3234.11
   385.5 3237.19   406.5 3238.23   440.3 3238.48   465.6 3237.19   504.3 3233.65
   558.1 3236.82   604.2 3237.72   635.9 3239.97   703.7 3241.65     708 3242.16
   733.7 3251.33   746.5 3253.66   763.6 3253.93   802.2 3257.69   896.6 3270.47
#Mann= 10 ,-1,0
       0      .1       0      10     .06       0     120     .12       0
   289.4    .045       0   355.5     .12       0     430      .1       0
     470     .12       0     530      .1       0   636.1     .12       0
   736.1      .1       0
#XS Ineff= 2 , 0
                          436.06         3245.63
Permanent Ineff=
       F       F
Bank Sta=289.4,355.5
XS Rating Curve= 0 ,0
Exp/Cntr(USF)=0,0
Exp/Cntr=0.3,0.1

Type RM Length L Ch R = 1 ,69812   ,278.1,282.6,283.8
XS GIS Cut Line= 2
2342328.23385896592269.200210193     2341527.098      592330.992
#Sta/Elev= 30
       0 3335.89    17.5 3331.16    40.2 3319.75    64.2 3319.14   104.4 3312.58
   176.6 3278.89   220.7 3262.46   264.8 3241.69   331.5 3225.94   346.4 3223.26
   372.5 3226.11   405.3 3232.81   417.2 3233.28   461.4 3228.65   485.5 3229.96
   497.5 3228.47   557.7 3228.36   573.6 3230.98   593.8 3230.15   617.9 3232.25
   629.9 3229.39     650 3230.45     666 3235.05   678.1 3240.71   690.1 3250.04
   706.2 3259.66   738.2 3284.63   754.3 3291.39   782.2 3306.78   803.5 3314.92
#Mann= 8 ,-1,0
       0     .06       0      60     .12       0     160      .1       0
   331.5    .045       0   372.5     .12       0     460      .1       0
     550     .08       0     650      .1       0
#XS Ineff= 2 , 0
                          412.96          3239.9
Permanent Ineff=
       F       F
Bank Sta=331.5,372.5
XS Rating Curve= 0 ,0
Exp/Cntr=0.3,0.1

Type RM Length L Ch R = 1 ,69529   ,269.5,263.8,260.8
XS GIS Cut Line= 3
2342298.75358361592093.8306921352342079.13136296 592018.24642139
2341541.48475785592031.081486234
#Sta/Elev= 30
       0  3335.1    28.1 3328.96    53.5 3320.46      62  3316.7     100 3293.97
   112.7 3289.22   137.2 3277.15   156.8 3269.77   197.3 3249.05   226.9 3235.88
   240.5 3233.31   271.2 3227.05   304.5  3228.3   331.2 3227.55   354.73220.945
   363.3 3219.62   391.3 3219.48   403.43221.011   423.3 3226.42   463.3 3222.48
   503.3 3223.34   519.3 3222.31     552 3227.98   571.3 3238.39   631.3 3278.77
   647.3 3285.95   671.3 3306.92   687.4 3316.29   699.1 3328.53   770.1 3371.88
#Mann= 5 ,-1,0
       0     .12       0   240.5     .06       0   304.5      .1       0
   354.7    .045       0   403.4      .1       0
Bank Sta=354.7,403.4
XS Rating Curve= 0 ,0
Exp/Cntr(USF)=0,0
Exp/Cntr=0.3,0.1

Type RM Length L Ch R = 1 ,69265   ,255.9,261.1,262.5
XS GIS Cut Line= 3
     2342352.363      591694.2792341877.54285876591763.482356802
2341528.34415832591770.640677694
#Sta/Elev= 30
       0 3319.08    12.3 3314.72    32.5  3304.4    60.8 3295.47      98 3280.33
     174 3253.35   250.8 3232.19   283.1 3227.54   303.4 3226.99   343.8 3221.53
     360 3223.23   380.1    3223   408.5  3223.5   424.6  3219.8   432.7 3218.38
   469.1 3218.28477.09993219.877   489.2 3221.78   501.2 3221.63   521.2  3217.9
   541.2 3222.42   557.2 3224.26   581.2 3237.97   641.2 3259.61   673.2 3275.31
   689.2 3280.58   700.1 3286.94   729.3 3299.19   805.3 3335.22   829.1 3344.72
#Mann= 5 ,-1,0
       0     .12       0   283.1     .06       0   380.1      .1       0
   424.6    .045       0477.0999      .1       0
#XS Ineff= 2 , 0
           404.4    3226
Permanent Ineff=
       F       F
Bank Sta=424.6,477.0999
XS Rating Curve= 0 ,0
Exp/Cntr=0.3,0.1

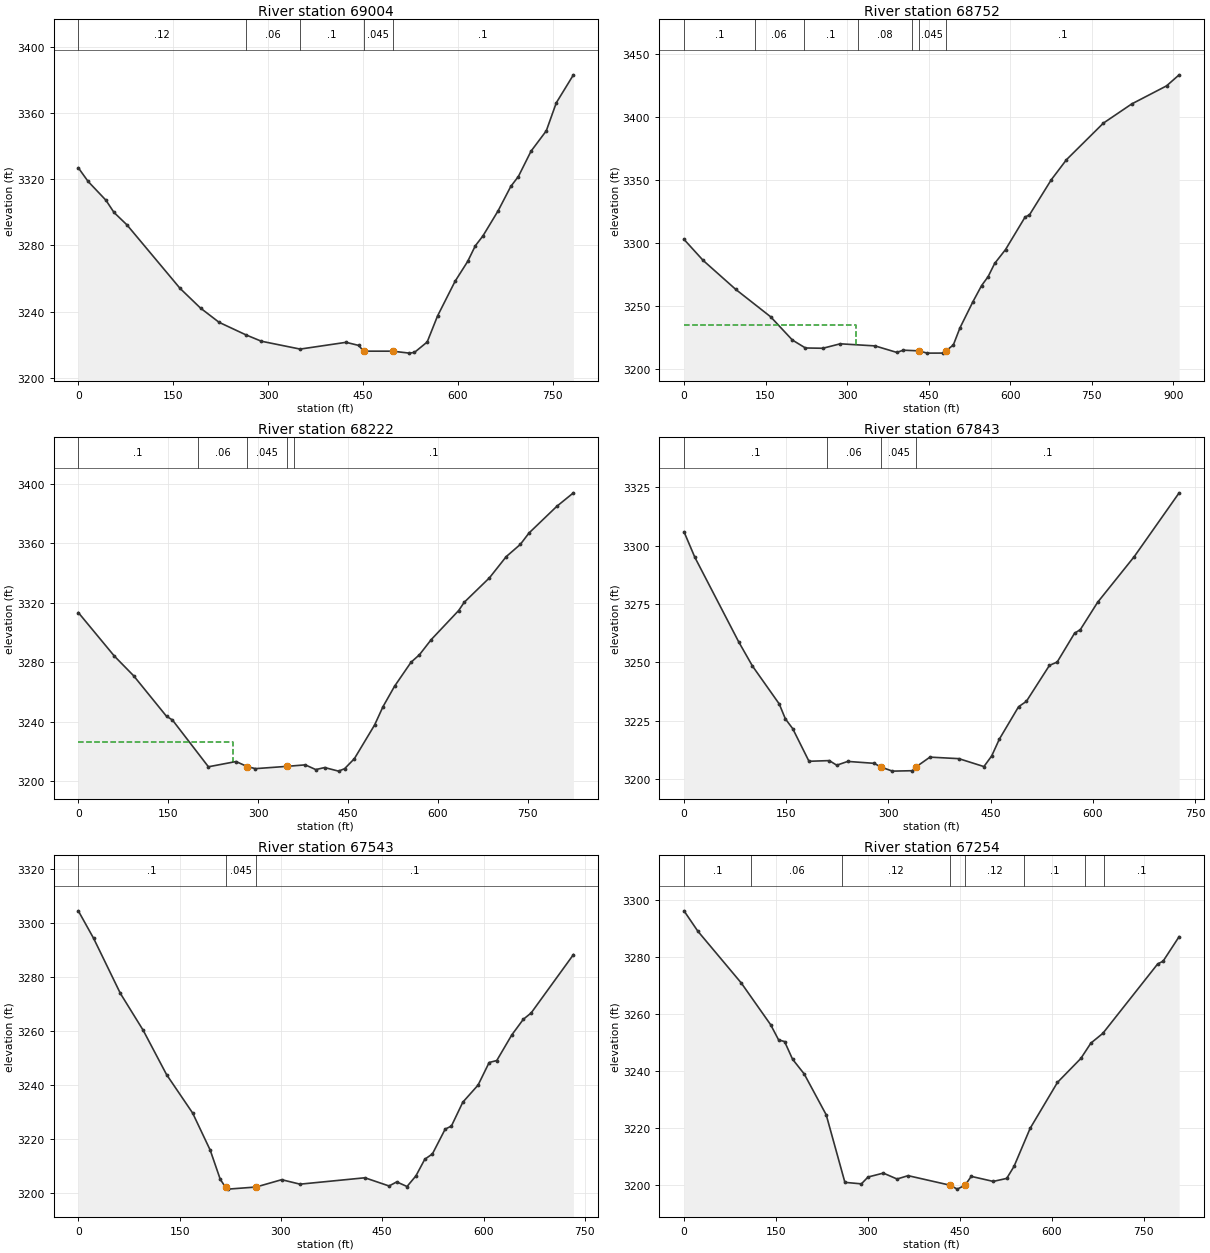
Type RM Length L Ch R = 1 ,69004   ,249.3,251.9,254.6
XS GIS Cut Line= 3
 2342351.5199613591442.0946217542341942.72450675591497.826318122
 2341573.3221689591514.528935152
#Sta/Elev= 30
       0 3326.88    15.5 3318.62    43.7 3307.25    56.4 3299.89    76.8 3292.41
   160.8    3254   193.1 3242.11   222.4 3233.51   265.1 3225.88   289.3 3222.07
   350.6 3217.32   423.1 3221.41   443.2 3219.52  450.68 3216.07  496.56 3216.06
   523.2 3214.88   531.2 3215.31   551.3  3221.6   567.6 3237.28   595.3 3258.24
   615.3  3270.3   627.3  3279.7   639.4 3285.71   663.4 3300.89   683.4 3315.61
   695.4  3321.6   715.4 3336.91   739.5  3349.2   755.3 3366.12   782.4 3383.04
#Mann= 5 ,-1,0
       0     .12       0   265.1     .06       0   350.6      .1       0
  450.68    .045       0  496.56      .1       0
Bank Sta=450.68,496.56
XS Rating Curve= 0 ,0
Exp/Cntr(USF)=0,0
Exp/Cntr=0.3,0.1

Type RM Length L Ch R = 1 ,68752   ,565.2,529.8,511
XS GIS Cut Line= 2
     2342295.516      591252.498     2341385.015       591253.83
#Sta/Elev= 30
       0  3302.9    35.3 3286.21    95.3 3263.26   159.3 3241.64   199.3 3223.23
   223.3 3216.95   255.3 3216.72   287.3 3220.25   351.3 3218.59   391.3 3213.44
   403.3 3215.19   431.3 3214.69   447.3 3212.87   475.4 3212.91  482.123214.759
   495.3 3219.37   507.4 3232.82   531.3 3253.58   547.3 3266.39   559.2 3273.39
   571.3 3283.88   591.2 3294.82   627.3 3320.63   635.3 3322.33   675.3 3350.06
   703.3 3365.98   771.3 3394.97   823.3 3410.11   887.3 3424.41   910.5 3433.16
#Mann= 7 ,-1,0
       0      .1       0     130     .06       0     220      .1       0
     320     .08       0     420      .1       0   431.3    .045       0
  482.12      .1       0
#XS Ineff= 2 , 0
          316.06 3235.49
Permanent Ineff=
       F       F
Bank Sta=431.3,482.12
XS Rating Curve= 0 ,0
Exp/Cntr=0.3,0.1

Type RM Length L Ch R = 1 ,68222   ,369.7,379.7,374.7
XS GIS Cut Line= 3
 2342088.2050351590564.1093074122341682.61704458 590797.98923294
     2341376.202      590982.994
#Sta/Elev= 30
       0 3313.44    60.1 3284.14    92.4 3270.83   147.2 3243.57     157 3241.12
   217.1 3209.58   263.2 3213.12   281.7 3209.75   295.5 3208.33  348.01 3209.87
   378.7 3210.88   396.2  3207.7     411 3209.07   434.2 3206.66   444.3 3208.29
   460.6 3215.04   494.4 3237.75   508.4 3250.08   527.6 3263.77   555.1 3279.95
   569.2 3285.02   588.8 3295.19   634.6 3314.78   643.9 3320.33     686 3336.81
     714 3351.08   737.4 3359.26     752 3366.98   798.6 3385.02   826.1 3394.02
#Mann= 5 ,-1,0
       0      .1       0     200     .06       0   281.7    .045       0
  348.01     .06       0     360      .1       0
#XS Ineff= 2 , 0
          258.59 3226.13
Permanent Ineff=
       F       F
Bank Sta=281.7,348.01
XS Rating Curve= 0 ,0
Exp/Cntr=0.3,0.1

Type RM Length L Ch R = 1 ,67843   ,312.4,299.5,290.7
XS GIS Cut Line= 4
2341834.81867238590246.5547021012341618.81154337590440.846828727
2341569.66706428590455.704461939  2341297.658087590727.713439215
#Sta/Elev= 30
       0 3305.88    15.9 3294.96    80.2 3258.75   100.4 3248.39   139.7 3232.14
   148.8  3225.7   159.5 3221.56   183.4 3207.56   213.3 3207.85   224.1 3205.87
   240.3  3207.5   279.1 3206.68   288.7 3205.13   305.8 3203.34   335.1 3203.52
     341 3205.24   360.9 3209.34   403.4 3208.68   440.1 3205.29   451.5 3209.84
   462.8 3217.07     491 3230.94   502.4 3233.22   536.3 3248.66   547.6 3250.06
   573.1  3262.4   581.6 3263.97     607 3275.68   660.8 3295.28   726.6 3322.57
#Mann= 4 ,-1,0
       0      .1       0     210     .06       0   288.7    .045       0
     341      .1       0
Bank Sta=288.7,341
XS Rating Curve= 0 ,0
Exp/Cntr(USF)=0,0
Exp/Cntr=0.3,0.1

Type RM Length L Ch R = 1 ,67543   ,305.2,289.1,250.4
XS GIS Cut Line= 2
2341668.40928797589993.1584127672341147.87610265590509.413243135
#Sta/Elev= 30
       0 3304.48    22.8 3294.22    62.3 3273.85    96.1 3260.16   130.7 3243.73
   169.3 3229.48   195.3 3215.72   210.2 3204.89     218 3201.96   221.6 3201.26
   263.2 3202.04   301.1 3204.76   328.3  3203.1   424.4 3205.47   460.1 3202.43
   471.5 3203.94   486.7 3202.23   499.9 3206.18     513 3212.34   524.3 3214.32
   543.2 3223.52   552.4 3224.64   569.3  3233.5   591.9 3239.85   608.3 3248.22
   619.6 3248.96   641.9 3258.48   658.9 3264.25   670.5  3266.6   733.1 3288.25
#Mann= 3 ,-1,0
       0      .1       0     218    .045       0   263.2      .1       0
Bank Sta=218,263.2
XS Rating Curve= 0 ,0
Exp/Cntr(USF)=0,0
Exp/Cntr=0.3,0.1

Type RM Length L Ch R = 1 ,67254   ,495.2,502.6,509.1
XS GIS Cut Line= 4
2341560.02051502589816.9985141092341394.23447939589986.558420047
2341251.00219822590270.1294009472341095.83337216590469.868231116
#Sta/Elev= 30
       0 3296.29    22.6 3289.13    93.4 3270.95   141.4 3256.27   154.3 3250.96
   164.1 3250.36   177.1 3244.17   196.1 3238.99     232 3224.64   262.5 3200.91
   289.4 3200.38   300.2 3202.78   325.2 3204.16   347.6 3202.08   365.6 3203.26
   434.2  3199.9   445.8 3198.53  458.673199.938   468.6 3203.01   504.5 3201.24
   526.5  3202.3   538.4 3206.51   564.7 3219.88   609.3 3236.03   647.4 3244.43
   663.8 3249.82   683.3 3253.25   772.8 3277.64   781.6  3278.6   807.8 3287.23
#Mann= 8 ,-1,0
       0      .1       0     110     .06       0  257.14     .12       0
   434.2    .045       0  458.67     .12       0  554.83      .1       0
  654.83     .12       0  684.83      .1       0
Bank Sta=434.2,458.67
XS Rating Curve= 0 ,0
Exp/Cntr=0.3,0.1

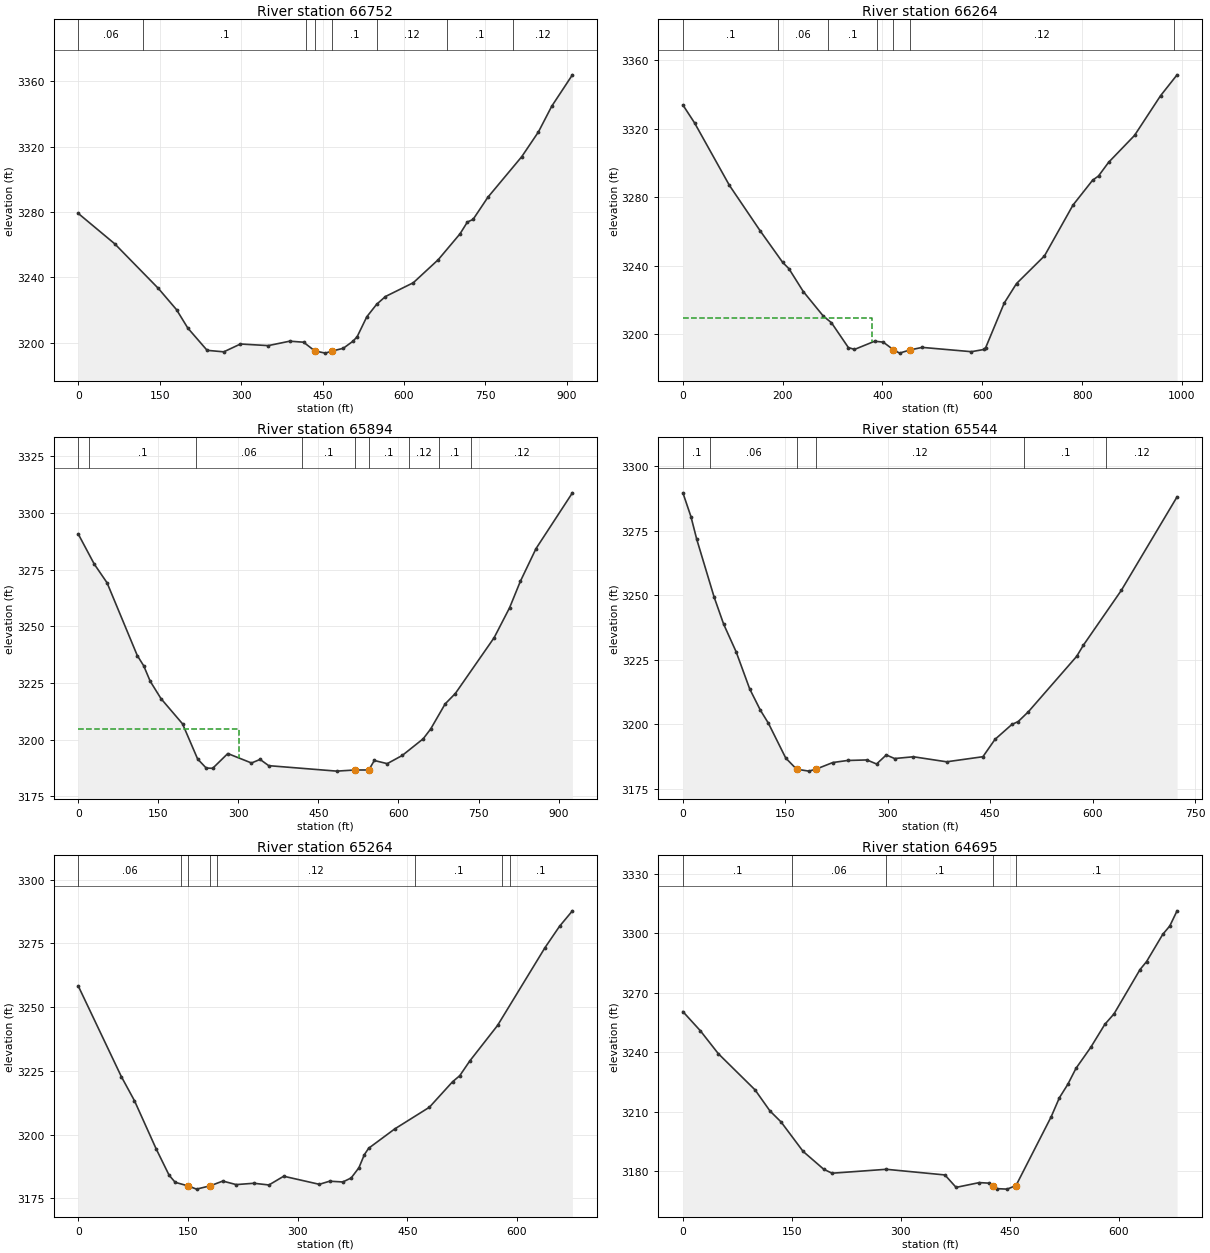
Type RM Length L Ch R = 1 ,66752   ,503.2,487.1,471.1
XS GIS Cut Line= 2
     2341166.122      589547.724     2340597.933      590258.926
#Sta/Elev= 30
       0 3279.15    67.2 3260.53   147.6  3233.2   181.1 3220.17   201.8 3208.93
   237.4 3195.29   268.1 3194.37   298.8 3199.17     350 3198.18   389.5  3200.9
   415.1 3200.27  435.663194.961   454.9 3193.58   467.8 3194.86   488.2 3196.54
   506.2 3200.92   513.8 3203.65   531.5 3215.81   549.7  3223.5   565.9 3228.25
   617.2 3236.69   663.2 3250.83   703.3 3266.67   716.8 3273.87   727.3 3275.47
   754.5 3289.01     817 3313.92   847.7 3329.07   872.2  3344.8   910.3 3364.02
#Mann= 8 ,-1,0
       0     .06       0     120      .1       0     420     .12       0
  435.66    .045       0   467.8      .1       0     550     .12       0
     680      .1       0     800     .12       0
Bank Sta=435.66,467.8
XS Rating Curve= 0 ,0
Exp/Cntr=0.3,0.1

Type RM Length L Ch R = 1 ,66264   ,384.5,370.8,354.5
XS GIS Cut Line= 3
     2340583.906        589206.52340430.67186062 589853.45367391
     2340454.517      590178.142
#Sta/Elev= 30
       0 3333.81    23.3 3323.39    93.2 3286.88   154.8 3260.35   200.1 3241.83
   212.4 3238.24   241.3 3224.85   281.2 3210.59   297.8 3206.62   331.6 3192.15
   343.9 3191.04   384.2 3195.82   401.5 3195.31     422 3190.83   434.4 3188.88
   454.9 3190.74   479.6 3192.23   578.2 3189.72   603.6 3191.03   606.9 3192.13
     644 3218.13   668.6  3229.5   724.7 3245.69   781.8 3275.34     821 3289.82
     833 3292.36   853.1 3300.29   905.1 3316.01   957.3 3339.22   990.4 3351.42
#Mann= 7 ,-1,0
       0      .1       0     190     .06       0     290      .1       0
     390     .12       0     422    .045       0   454.9     .12       0
  984.85      .1       0
#XS Ineff= 2 , 0
          379.72  3209.4
Permanent Ineff=
       F       F
Bank Sta=422,454.9
XS Rating Curve= 0 ,0
Exp/Cntr=0.3,0.1

Type RM Length L Ch R = 1 ,65894   ,365.3,349.3,316.2
XS GIS Cut Line= 3
2340104.76473872 589263.561308442340191.57218185589903.042806185
2340352.16595165590133.082530488
#Sta/Elev= 30
       0 3290.71    29.9 3277.49      54 3269.19   110.6 3237.13   122.7 3232.58
   134.8 3225.81     155 3218.14   195.4 3207.01   223.7  3191.5   239.8 3187.51
   251.9 3187.41   280.2 3193.91   324.6 3189.75   340.7 3191.32   356.9 3188.57
   484.3 3186.16   518.3 3186.66   544.4 3186.67   554.7 3190.85   578.9 3189.46
   607.1 3193.07   646.4 3200.44   660.4 3204.77   687.5 3215.82   706.5 3220.38
   779.2 3244.99   808.2 3258.21   828.3 3269.83   857.7 3284.28   925.9 3308.87
#Mann= 9 ,-1,0
       0     .12       0      20      .1       0     220     .06       0
     420      .1       0   518.3    .045       0   544.4      .1       0
     620     .12       0  675.35      .1       0  735.35     .12       0
#XS Ineff= 2 , 0
          301.41 3204.62
Permanent Ineff=
       F       F
Bank Sta=518.3,544.4
XS Rating Curve= 0 ,0
Exp/Cntr(USF)=0,0
Exp/Cntr=0.3,0.1

Type RM Length L Ch R = 1 ,65544   ,279.7,280,279.5
XS GIS Cut Line= 2
2339740.29732483 589652.316135262340272.23945667 590142.90083594
#Sta/Elev= 30
       0 3289.78    11.8 3280.54    20.3 3271.73    45.8 3249.28    59.7 3238.81
      78 3228.08    97.8 3213.72   113.4 3205.48   125.2  3200.4   150.6 3186.88
   166.5 3182.56   184.5 3181.81  195.02 3182.59   219.6 3185.15   241.1 3185.94
   269.4 3186.15   283.6 3184.58   297.8 3188.08     310  3186.7   337.6 3187.38
   386.2 3185.43   439.3  3187.4   456.9  3194.1   481.7 3199.91     491 3201.05
   505.9 3204.85   576.6 3226.34   586.5  3230.7   641.9 3251.91   723.6 3288.22
#Mann= 6 ,-1,0
       0      .1       0      40     .06       0   166.5    .045       0
  195.02     .12       0     500      .1       0     620     .12       0
Bank Sta=166.5,195.02
XS Rating Curve= 0 ,0
Exp/Cntr(USF)=0,0
Exp/Cntr=0.3,0.1

Type RM Length L Ch R = 1 ,65264   ,517.8,569.4,624.6
XS GIS Cut Line= 2
2339576.68612633589881.3409454022340075.82892434 590337.08002185
#Sta/Elev= 30
       0 3258.31    58.9 3222.78    76.9  3213.3   106.5 3194.45   124.3 3184.07
   132.6 3181.29   149.6 3179.93   161.8 3178.62   180.7 3179.94   197.7 3181.78
     216  3180.4   240.2 3180.92   260.8 3180.25     281 3183.68   329.7 3180.51
   343.8 3181.73   361.9 3181.43   373.3 3183.01   383.9 3187.02   391.3 3192.13
   397.2 3194.66   432.8 3202.22   480.3 3210.75     512 3220.75   521.8 3223.12
   535.5 3228.89   573.5 3242.83   638.5  3273.4   658.3 3281.73   675.9 3287.79
#Mann= 8 ,-1,0
       0     .06       0     140      .1       0   149.6    .045       0
   180.7      .1       0     190     .12       0     460      .1       0
     580     .12       0     590      .1       0
Bank Sta=149.6,180.7
XS Rating Curve= 0 ,0
Exp/Cntr(USF)=0,0
Exp/Cntr=0.3,0.1

Type RM Length L Ch R = 1 ,64695   ,404.1,442.9,475.2
XS GIS Cut Line= 2
2339507.24017182589859.6390846192339081.88370047590390.611278448
#Sta/Elev= 30
       0 3260.53    24.1 3250.84    48.8  3239.3    99.4 3221.04   119.9 3210.42
   135.2 3204.87   165.5 3190.04   193.9 3181.04   205.3 3179.04     280 3181.02
   360.7 3178.17   376.1  3171.9     408 3174.31   421.6 3174.03   427.2 3172.81
   432.5 3171.26   446.4 3171.02   458.6 3172.84     507  3207.5   518.3 3217.09
   529.9 3223.86   541.1 3231.89   561.5 3242.52   580.9 3254.12   593.5 3259.38
   629.3 3281.72   638.3 3285.74   660.6 3299.47   670.3 3303.71   680.3 3311.33
#Mann= 5 ,-1,0
       0      .1       0     150     .06       0     280      .1       0
   427.2    .045       0   458.6      .1       0
Bank Sta=427.2,458.6
XS Rating Curve= 0 ,0
Exp/Cntr(USF)=0,0
Exp/Cntr=0.3,0.1