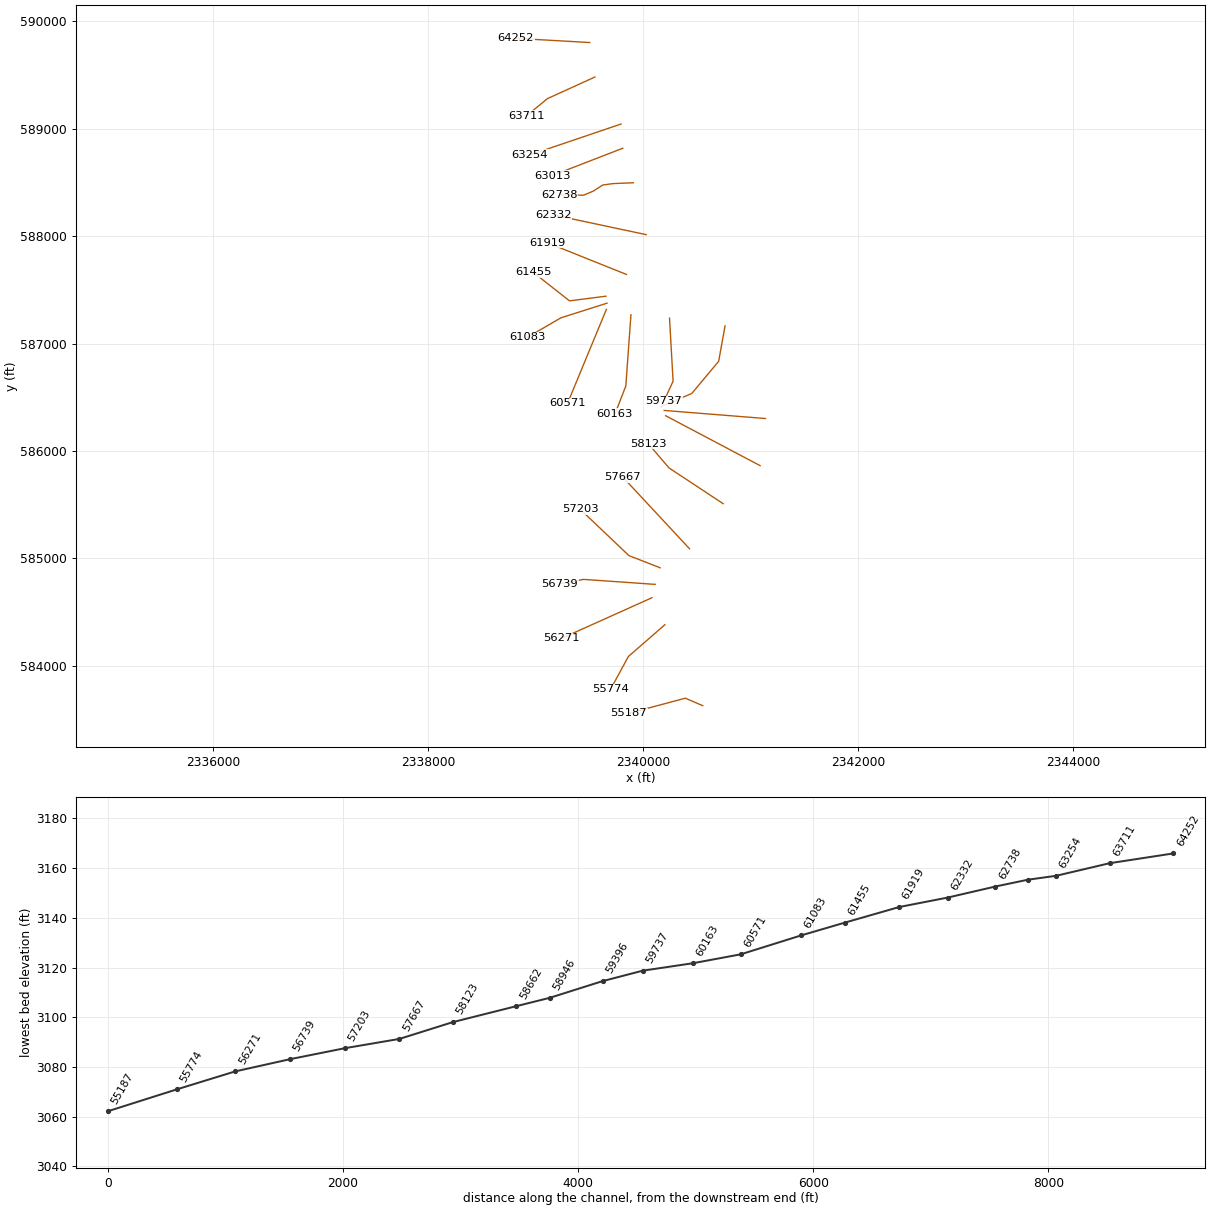
HEC-RAS study EFGRNBRRRV.prj: EFGRNBRRRV

--- EFGRNBRRRV.g01 (geometry) --- (continued)

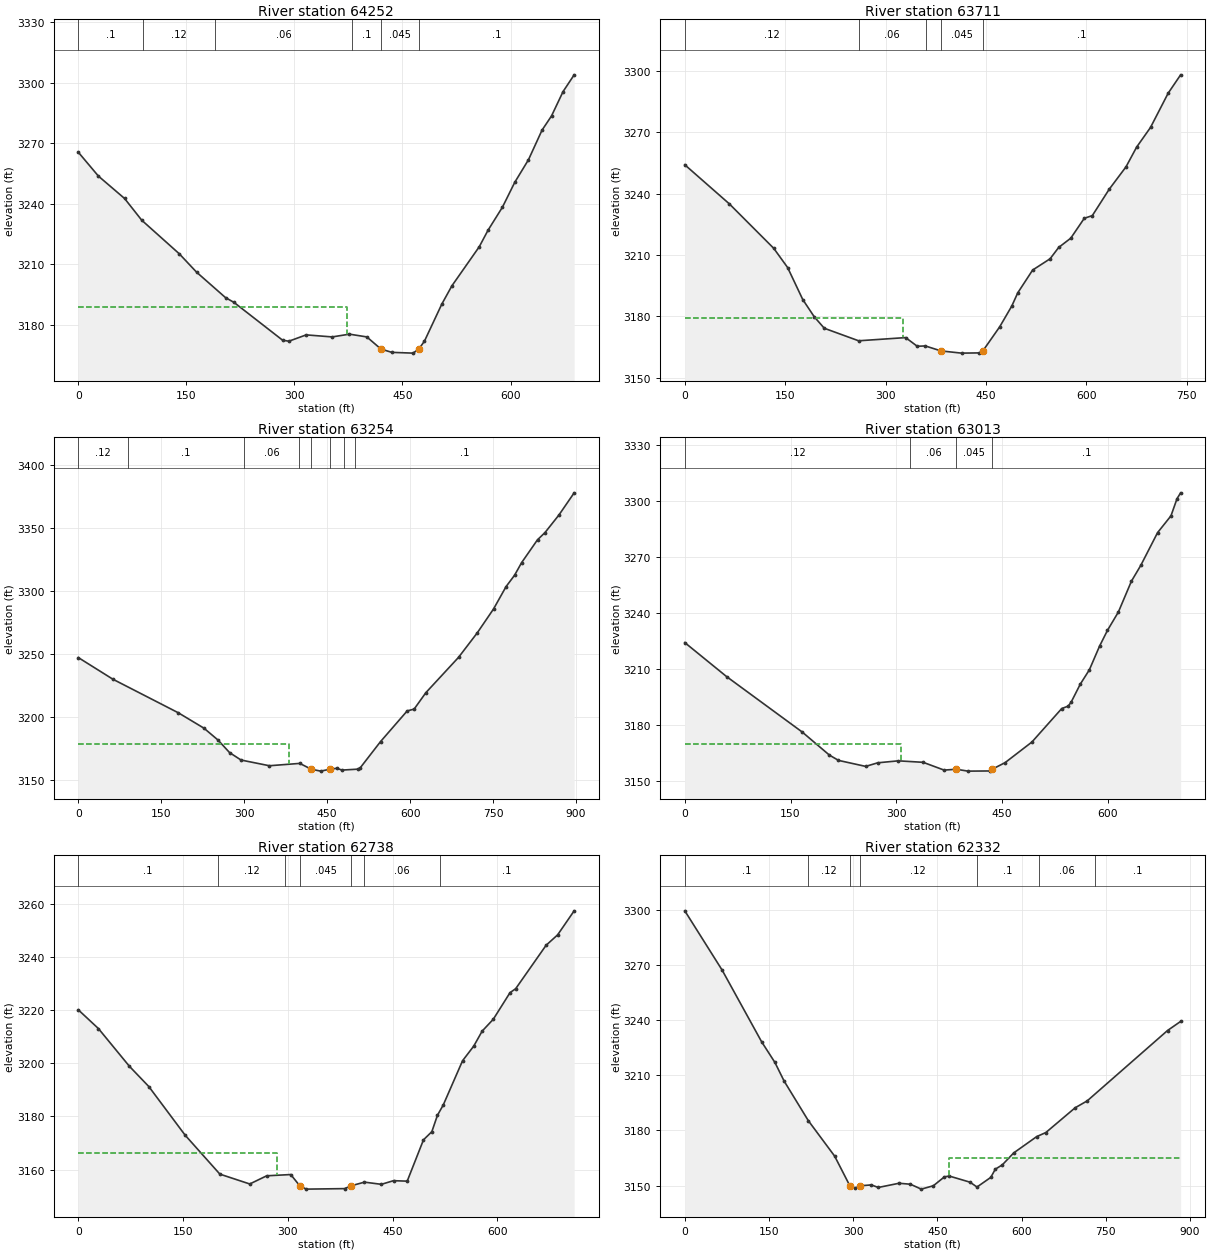
Type RM Length L Ch R = 1 ,64252   ,513.3,541.6,562.3
XS GIS Cut Line= 2
2339500.00621823589801.7674558642338812.78062676589840.830805273
#Sta/Elev= 30
       0 3265.46    27.9 3253.63    64.2 3242.55      88 3231.79   140.1 3215.16
   164.1 3206.06   204.3 3193.44   216.2 3191.04   283.6 3172.32   292.3 3171.84
   316.3 3174.97   352.4 3173.96   376.4 3175.33   400.5 3173.96   420.1 3167.95
   435.2 3166.31   464.6 3165.93   472.6 3167.92   480.5 3171.88   504.6 3190.24
   518.6 3199.29   556.6 3218.66   568.7  3226.8   588.8 3238.28   605.8 3250.53
   624.9 3261.76   643.7 3276.41   656.9 3283.46   672.9 3295.52   688.3 3303.82
#Mann= 6 ,-1,0
       0      .1       0      90     .12       0     190     .06       0
     380      .1       0   420.1    .045       0   472.6      .1       0
#XS Ineff= 2 , 0
          373.07 3188.94
Permanent Ineff=
       F       F
Bank Sta=420.1,472.6
XS Rating Curve= 0 ,0
Exp/Cntr(USF)=0,0
Exp/Cntr=0.3,0.1

Type RM Length L Ch R = 1 ,63711   ,459.5,456.7,453.5
XS GIS Cut Line= 3
2339548.62868252589480.8665633012339106.79024663589279.756645348
 2338909.4289579589117.341521461
#Sta/Elev= 30
       0 3254.05    66.6 3234.94     133  3213.2   153.7 3203.82   176.3  3188.2
   193.4  3179.8   208.5 3174.15   259.8 3168.03   330.1 3169.59   347.4 3165.36
   359.5 3165.51   382.9 3163.08   413.6    3162     440 3162.11445.50543163.095
   470.7 3174.87   488.8 3185.05   497.7 3191.48   519.9  3202.6     546 3208.11
   558.8 3213.64   576.9 3218.18   597.1  3227.9   609.1  3229.2   634.3 3242.07
   659.5 3253.06   675.3 3262.66   696.1  3272.3   722.4 3288.99   741.1 3298.01
#Mann= 5 ,-1,0
       0     .12       0     260     .06       0     360      .1       0
   382.9    .045       0445.5054      .1       0
#XS Ineff= 2 , 0
          326.76 3178.99
Permanent Ineff=
       F       F
Bank Sta=382.9,445.5054
XS Rating Curve= 0 ,0
Exp/Cntr(USF)=0,0
Exp/Cntr=0.3,0.1

Type RM Length L Ch R = 1 ,63254   ,236.5,240.7,243.3
XS GIS Cut Line= 2
2339791.38513922589043.270651502     2338942.193       588755.08
#Sta/Elev= 30
       0 3246.95    62.5  3229.8   180.8 3203.19   227.3 3190.95   252.6 3181.58
   273.7 3171.55   294.3 3165.72   345.5 3161.19   400.5 3163.05   421.6 3158.38
   438.5 3156.92   455.4 3158.46     468 3159.19   476.5 3157.74   506.1  3158.5
   510.3 3159.79   546.6 3180.34   594.8 3204.66   607.4 3206.12   628.6 3219.14
   687.7 3247.14   721.5 3266.53   751.1 3285.58   773.7 3303.27   789.1 3312.29
   801.7 3322.19   830.5 3340.36     844 3346.05   869.3 3360.03   896.8 3377.59
#Mann= 8 ,-1,0
       0     .12       0      90      .1       0     300     .06       0
     400      .1       0   421.6    .045       0   455.4      .1       0
     480     .06       0     500      .1       0
#XS Ineff= 2 , 0
          380.85 3178.27
Permanent Ineff=
       F       F
Bank Sta=421.6,455.4
XS Rating Curve= 0 ,0
Exp/Cntr=0.3,0.1

Type RM Length L Ch R = 1 ,63013   ,264.3,275.6,279.6
XS GIS Cut Line= 2
2339807.49678518588817.8477449542339151.40332077 588563.63055573
#Sta/Elev= 30
       0 3224.16    59.3 3205.96   166.6 3176.28   205.2 3163.92   218.1 3161.09
   256.7 3157.87   273.8  3159.8     303 3160.85   338.2 3160.06   367.9  3155.9
   385.4 3156.33   401.9 3155.34   432.5 3155.43   435.9 3156.31   454.5 3159.88
   492.6 3170.93   534.9 3188.85   544.1 3190.15   548.4 3192.38   561.2  3201.9
   574.1 3209.59   588.6  3222.3   599.8 3230.72   615.3 3240.55   633.8 3257.05
     647 3265.46   670.9 3283.04   689.9 3292.03   698.5 3301.23   703.6 3304.35
#Mann= 4 ,-1,0
       0     .12       0     320     .06       0   385.4    .045       0
   435.9      .1       0
#XS Ineff= 2 , 0
          306.93 3170.08
Permanent Ineff=
       F       F
Bank Sta=385.4,435.9
XS Rating Curve= 0 ,0
Exp/Cntr(USF)=0,0
Exp/Cntr=0.3,0.1

Type RM Length L Ch R = 1 ,62738   ,434.1,406.1,387.4
XS GIS Cut Line= 6
2339904.98054275588496.4817405392339715.07173127588488.564581023
2339619.61083549588474.8117401052339533.85782741588418.991385788
2339442.05732328588380.4750942172339220.41230867588386.811030772
#Sta/Elev= 30
       0 3220.13    28.8 3213.08    73.1 3198.89   100.9 3191.26   152.9 3172.95
   202.7 3158.26   245.5 3154.55   269.8 3157.63   304.2  3158.1316.84473153.964
   326.2 3152.61   381.3  3152.8390.99823153.895   409.8 3155.24     434 3154.42
   451.4 3155.79     471 3155.61   494.3 3171.17   506.3 3174.26   514.3 3180.42
   522.6 3184.29   550.3 3200.98   566.3 3206.48   578.3 3212.11   594.3  3216.6
   618.3 3226.63   626.3 3228.08   669.9 3244.45   686.4 3248.37   710.1 3257.43
#Mann= 7 ,-1,0
       0      .1       0  200.07     .12       0  296.52      .1       0
316.8447    .045       0390.9982      .1       0  408.84     .06       0
  518.39      .1       0
#XS Ineff= 2 , 0
          284.85 3166.08
Permanent Ineff=
       F       F
Bank Sta=316.8447,390.9982
XS Rating Curve= 0 ,0
Exp/Cntr=0.3,0.1

Type RM Length L Ch R = 1 ,62332   ,414.7,412.1,401.1
XS GIS Cut Line= 2
2340025.19124918588013.5341273262339161.45719001588197.276548624
#Sta/Elev= 30
       0 3299.29    66.5  3267.1   136.8 3228.19   160.5 3216.95   176.9 3206.84
     220 3185.34   266.9 3166.08   293.9 3150.02   303.7 3148.66   311.8 3149.95
   332.3 3150.45   344.6 3149.06   381.6 3151.35   401.8 3150.82   421.2 3148.16
   442.7 3149.99   462.5 3154.85   471.3 3155.24   508.1 3151.92   520.4  3149.3
   544.9 3154.52   553.1 3159.01   565.4 3161.31   585.8 3167.82   626.7 3176.67
   643.1  3178.9   695.2 3192.33   716.7 3196.08   859.8  3234.3   883.1 3239.23
#Mann= 7 ,-1,0
       0      .1       0     220     .12       0   293.9    .045       0
   311.8     .12       0     520      .1       0     630     .06       0
     730      .1       0
#XS Ineff= 2 , 0
                          470.99         3164.92
Permanent Ineff=
       F       F
Bank Sta=293.9,311.8
XS Rating Curve= 0 ,0
Exp/Cntr(USF)=0,0
Exp/Cntr=0.3,0.1

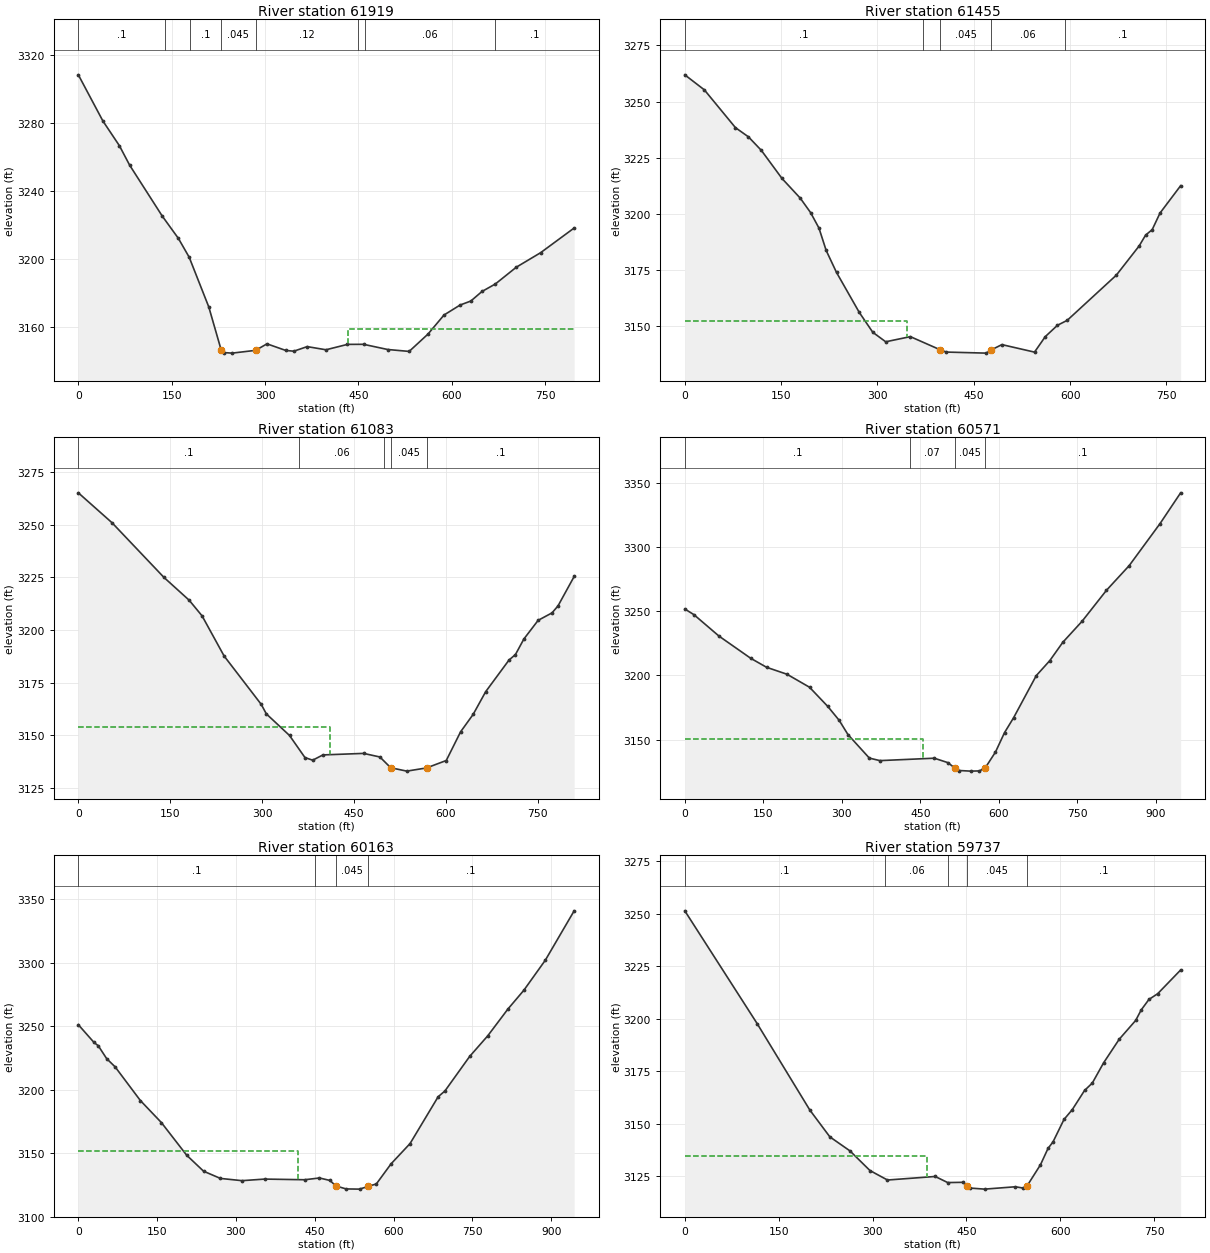
Type RM Length L Ch R = 1 ,61919   ,475.2,464.6,452.3
XS GIS Cut Line= 2
2339841.44882789587643.1557032932339102.13877054587939.747800663
#Sta/Elev= 30
       0 3308.53    39.4 3281.34      66 3266.71    82.5  3255.2   134.8 3225.22
   160.8 3212.01   178.1 3200.93   209.6 3171.59  229.64 3146.01   234.1 3144.68
     247 3144.36   284.8    3146   303.1 3149.84   333.2 3145.95   346.2  3145.5
   367.7  3148.2   397.9 3146.34   432.4 3149.52   458.2 3149.56     497  3146.5
   531.5 3145.37   561.7 3155.57   587.5 3166.84   613.4 3172.74   630.6 3175.09
   648.5 3180.72     670 3185.15   703.7 3195.06   742.7  3203.6   796.6 3218.17
#Mann= 8 ,-1,0
       0      .1       0     140     .12       0     180      .1       0
  229.64    .045       0   284.8     .12       0     450      .1       0
     460     .06       0     670      .1       0
#XS Ineff= 2 , 0
                          433.58         3158.77
Permanent Ineff=
       F       F
Bank Sta=229.64,284.8
XS Rating Curve= 0 ,0
Exp/Cntr(USF)=0,0
Exp/Cntr=0.3,0.1

Type RM Length L Ch R = 1 ,61455   ,296.8,371.7,425.4
XS GIS Cut Line= 3
2339650.47245299587440.6050026492339311.92342477587397.201281083
2338973.37439656587663.410773357
#Sta/Elev= 30
       0 3261.94    30.5 3255.23    78.9 3238.42    99.1 3234.33   119.3 3228.27
   151.3 3215.82   179.8 3207.04   195.9  3200.6   208.9 3193.72   220.1 3183.78
   236.2 3173.99   271.6 3156.21   292.7 3147.34   312.8 3143.11   351.2  3145.4
     397 3139.63   407.2 3138.53   469.3 3138.06   477.2  3139.5   493.7 3141.85
   544.5 3138.51   561.3 3145.41   580.2 3150.45   595.4 3152.65   671.8 3172.74
   707.4 3185.76   717.5 3190.61   727.7    3193   739.9  3200.4     772 3212.58
#Mann= 5 ,-1,0
       0      .1       0  371.32     .12       0     397    .045       0
   477.2     .06       0  591.32      .1       0
#XS Ineff= 2 , 0
          346.59 3152.36
Permanent Ineff=
       F       F
Bank Sta=397,477.2
XS Rating Curve= 0 ,0
Exp/Cntr(USF)=0,0
Exp/Cntr=0.3,0.1

Type RM Length L Ch R = 1 ,61083   ,474.4,511.7,538.8
XS GIS Cut Line= 3
2339660.59998803  587375.49942032339232.34993524587239.501092725
2338921.28993068587058.652252864
#Sta/Elev= 30
       0 3265.18      55 3250.96   139.8 3224.96   180.9 3214.13   201.9 3206.71
   237.9 3187.62   298.4 3164.66   306.8 3160.12   344.6 3149.86   369.8 3139.36
   382.4 3138.11   399.1 3140.61   465.5 3141.34   492.1 3139.63   509.7 3134.54
   509.7 3134.53   509.7 3134.52     536 3132.91   568.2 3134.43   600.4 3137.96
   623.8  3151.6   644.3 3159.89   664.7 3170.66   702.8 3185.71   713.3 3188.32
   727.1 3195.73   750.3 3204.57     773 3208.13   782.7 3211.42   809.1 3225.42
#Mann= 5 ,-1,0
       0      .1       0     360     .06       0  499.33      .1       0
   509.7    .045       0   568.2      .1       0
#XS Ineff= 2 , 0
           410.7 3153.77
Permanent Ineff=
       F       F
Bank Sta=509.7,568.2
XS Rating Curve= 0 ,0
Exp/Cntr(USF)=0,0
Exp/Cntr=0.3,0.1

Type RM Length L Ch R = 1 ,60571   ,389.9,407.9,421.7
XS GIS Cut Line= 2
2339654.81282515587317.6277915442339293.11514543586442.319406621
#Sta/Elev= 30
       0 3251.87    17.4 3247.48    65.4  3230.7     126 3213.38   156.3 3206.36
   195.2 3200.95   238.2 3190.82   273.2  3175.8   294.8 3165.02   311.7 3153.85
   352.5 3135.51   372.7 3133.53   476.6 3135.42   502.5 3131.96   515.5 3127.83
   524.2 3125.81   545.8 3125.33   562.8  3125.5  573.933127.903   593.4 3140.18
   610.7 3155.36   628.1 3167.03   671.3 3199.84   697.3 3211.63   722.1  3225.9
   758.8 3242.27   805.5  3266.5   848.8  3285.7   907.7 3318.49   947.1 3342.55
#Mann= 4 ,-1,0
       0      .1       0     430     .07       0   515.5    .045       0
  573.93      .1       0
#XS Ineff= 2 , 0
          454.65 3150.57
Permanent Ineff=
       F       F
Bank Sta=515.5,573.93
XS Rating Curve= 0 ,0
Exp/Cntr(USF)=0,0
Exp/Cntr=0.3,0.1

Type RM Length L Ch R = 1 ,60163   ,418.7,425.9,434.1
XS GIS Cut Line= 3
2339883.40575873587266.9901163832339835.66166501586604.359967136
2339734.38631469586343.937637737
#Sta/Elev= 30
       0  3251.2    29.9 3237.21    37.9 3234.66      54 3224.46      70 3218.03
   118.1  3191.5   158.2  3174.1   206.3 3148.42   238.4 3135.85   270.5 3130.17
   311.5  3128.4   354.7 3129.65   430.9 3129.13     459 3130.52     479 3128.56
   490.2 3124.25   509.7  3121.9   535.2 3121.74   551.7 3123.88   567.3 3125.85
   595.4 3141.71   631.4  3157.6   684.9 3194.47   697.8 3199.03     745 3226.28
   779.3 3242.45   817.8 3263.59     848 3278.31   888.9 3301.99   943.8 3340.88
#Mann= 4 ,-1,0
       0      .1       0     450     .06       0   490.2    .045       0
   551.7      .1       0
#XS Ineff= 2 , 0
          418.59 3151.51
Permanent Ineff=
       F       F
Bank Sta=490.2,551.7
XS Rating Curve= 0 ,0
Exp/Cntr(USF)=0,0
Exp/Cntr=0.3,0.1

Type RM Length L Ch R = 1 ,59737   ,369.3,341.6,304.2
XS GIS Cut Line= 3
2340242.20985702587236.6075112872340275.48604355586649.210479421
2340190.12539114586464.021267404
#Sta/Elev= 30
       0 3251.36   115.6 3197.63   199.7 3156.48   231.8 3143.65   263.9 3136.98
   295.9  3127.6   323.9 3123.09   400.1 3124.78   420.1 3121.88   444.1 3121.99
   451.7  3120.3   456.2 3119.25   479.1 3118.75   528.2 3119.87   540.9 3119.26
   547.3 3120.47   568.3 3130.33   580.4 3138.14   588.4 3141.26   605.9 3151.94
   619.2 3156.64   638.8 3165.77   651.2 3169.31   669.2 3178.92   694.1 3190.14
   720.5 3199.14   729.3 3204.13   741.6 3209.12   755.7 3211.88   792.3 3223.16
#Mann= 5 ,-1,0
       0      .1       0     320     .06       0     420      .1       0
   451.7    .045       0   547.3      .1       0
#XS Ineff= 2 , 0
          386.25 3134.57
Permanent Ineff=
       F       F
Bank Sta=451.7,547.3
XS Rating Curve= 0 ,0
Exp/Cntr(USF)=0,0
Exp/Cntr=0.3,0.1

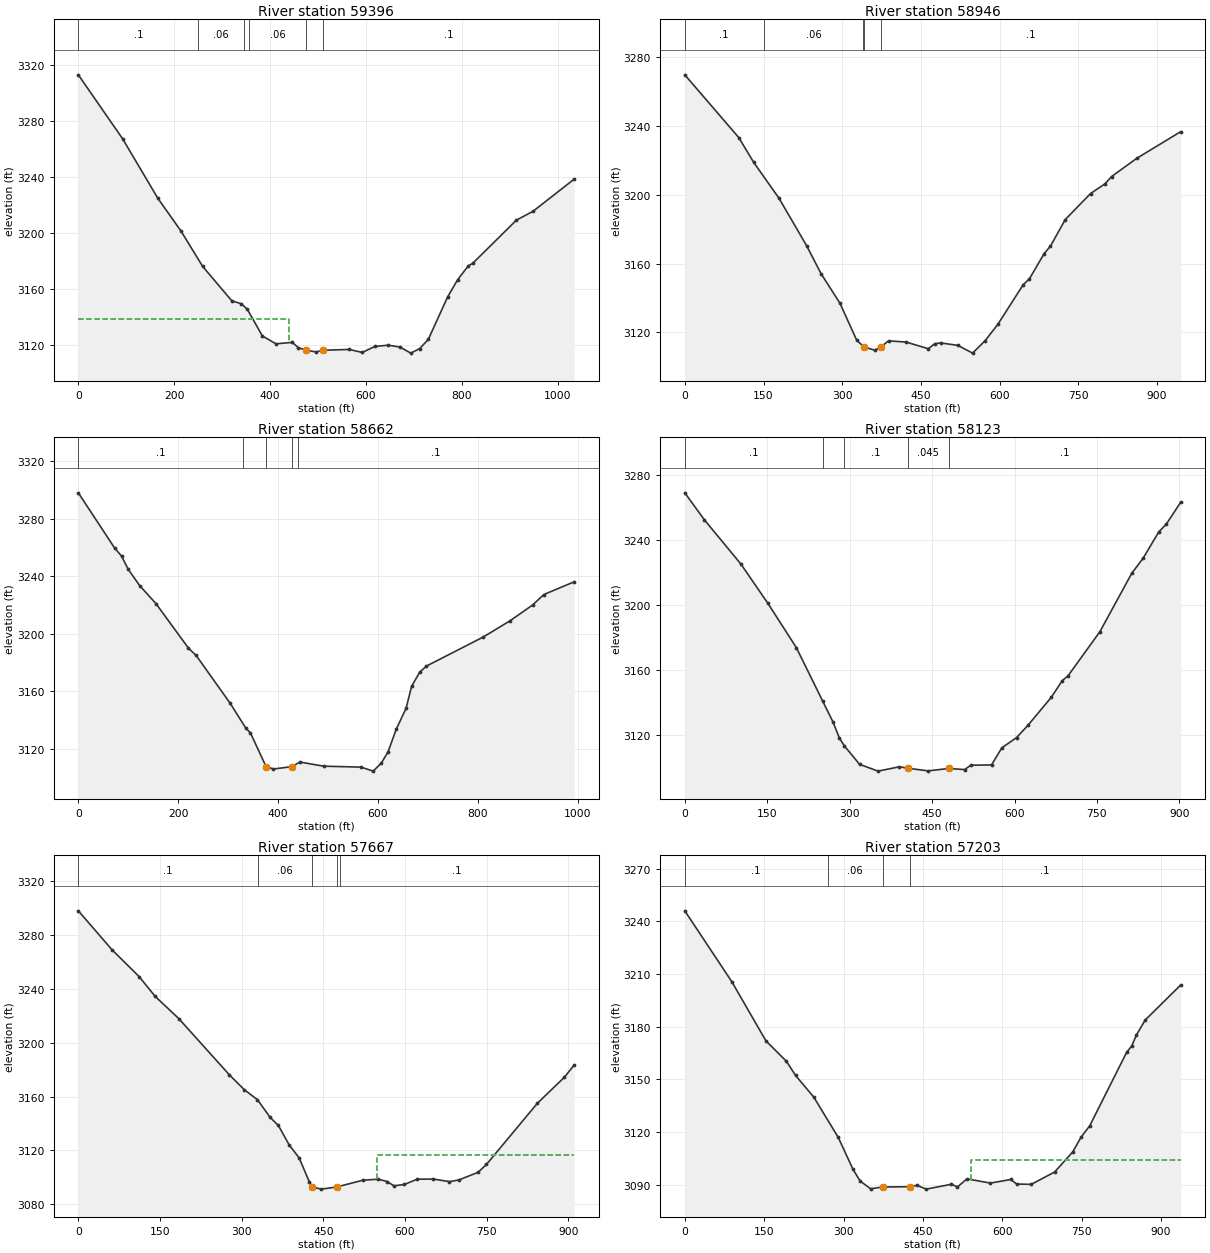
Type RM Length L Ch R = 1 ,59396   ,480.2,449.7,409.7
XS GIS Cut Line= 4
2340758.71414366587164.2679753432340699.39572418586834.399691438
2340449.10092982586534.9140126292340165.52994891586413.383592243
#Sta/Elev= 30
       0 3312.69    92.6 3267.02   165.7 3224.84   214.5 3201.26   259.2 3176.32
   320.1 3151.76   340.2 3149.69   352.5 3145.71   383.8 3126.79   412.1 3121.17
   446.2 3122.19   458.7 3118.46   475.33116.612   496.1 3115.39  510.563116.602
   564.7 3117.16   592.2 3115.06   618.3 3119.28   645.8  3120.2   670.6  3118.9
   693.3 3114.55   712.1 3117.84   729.9 3124.38   770.1 3154.54   790.8 3166.71
   813.5 3176.81   822.2  3178.4   913.6 3209.23   948.4 3215.58    1034 3238.41
#Mann= 6 ,-1,0
       0      .1       0     250     .06       0  345.16      .1       0
  355.16     .06       0   475.3    .045       0  510.56      .1       0
#XS Ineff= 2 , 0
          438.76 3138.63
Permanent Ineff=
       F       F
Bank Sta=475.3,510.56
XS Rating Curve= 0 ,0
Exp/Cntr(USF)=0,0
Exp/Cntr=0.3,0.1

Type RM Length L Ch R = 1 ,58946   ,304,284.5,268.3
XS GIS Cut Line= 2
2341134.87973057 586301.980706892340193.01897257586377.213824271
#Sta/Elev= 30
       0 3269.89     103  3233.3   131.1 3219.01   179.3 3198.12   232.2 3170.38
   259.5 3154.19   295.6 3136.93   327.7 3115.31   341.6 3111.44   362.2  3109.5
   373.4 3111.38   388.2 3114.99   421.7 3114.27   464.2 3110.39   476.2 3113.33
   488.3 3113.75   520.4 3112.34   548.4 3107.83   572.5 3115.12   596.6 3124.61
   644.9 3147.68   656.8 3151.12   684.9 3165.83   696.9 3170.16     725 3185.59
   773.2 3200.76   800.7  3206.4   813.3 3210.66   861.4 3221.29   944.9 3236.76
#Mann= 5 ,-1,0
       0      .1       0     150     .06       0     340      .1       0
   341.6    .045       0   373.4      .1       0
Bank Sta=341.6,373.4
XS Rating Curve= 0 ,0
Exp/Cntr(USF)=0,0
Exp/Cntr=0.3,0.1

Type RM Length L Ch R = 1 ,58662   ,525.9,538.8,532.5
XS GIS Cut Line= 2
2341084.66995268585863.519579614 2340206.5687698586327.853561427
#Sta/Elev= 30
       0 3297.92    72.6 3259.59    86.5 3253.97   100.1 3244.68   122.7  3233.5
   155.5 3220.94   220.6 3189.97   235.9 3184.94   304.5 3151.49   335.4 3134.42
   344.9 3130.95   376.1 3107.62   390.9 3105.95  427.793107.577     444 3110.78
   491.3 3107.91   566.2 3107.26   590.6 3104.47   606.9    3110   620.5 3117.85
   636.8 3133.54   656.7 3148.22   667.5 3163.33   683.8  3173.2   697.4  3177.5
   810.5 3197.56   864.8 3208.96     910 3219.93   932.7 3227.24   993.3 3236.07
#Mann= 5 ,-1,0
       0      .1       0     330     .06       0   376.1    .045       0
  427.79     .06       0     440      .1       0
Bank Sta=376.1,427.79
XS Rating Curve= 0 ,0
Exp/Cntr=0.3,0.1

Type RM Length L Ch R = 1 ,58123   ,452.7,456,439.6
XS GIS Cut Line= 3
     2340741.519      585509.1392340237.86948486585841.901258285
 2340043.7152566586068.856303004
#Sta/Elev= 30
       0    3269    35.6 3252.43   101.7 3225.43   151.1 3201.19     203 3173.93
   250.9 3141.09   269.5 3128.41     281 3118.67   290.3  3113.6     318 3102.27
   351.6 3098.07   390.7 3100.75   406.4 3099.83   442.7 3098.22   480.2 3099.69
   509.1 3099.03   520.6 3101.69   558.2 3101.88   576.9 3112.35   603.7 3118.68
   624.7 3126.28   666.8 3143.37   686.9 3153.63   697.5 3156.65   755.4 3183.72
   813.3 3219.53   834.1 3228.88   862.5 3244.95   876.4 3249.86   902.3 3263.14
#Mann= 5 ,-1,0
       0      .1       0   250.9     .06       0   290.3      .1       0
   406.4    .045       0   480.2      .1       0
Bank Sta=406.4,480.2
XS Rating Curve= 0 ,0
Exp/Cntr=0.3,0.1

Type RM Length L Ch R = 1 ,57667   ,460.6,463.5,465.8
XS GIS Cut Line= 2
     2340428.247      585089.941     2339807.901      585756.576
#Sta/Elev= 30
       0 3297.87    61.8 3268.99   111.7 3249.02     141 3234.41   184.7 3217.79
   277.6 3176.04   304.9 3165.05   328.9 3157.72   352.4 3144.46   367.4 3138.55
   387.6 3123.85   405.3 3114.66   424.1 3096.83   429.7 3092.84   446.4 3091.29
     475 3092.94   522.7 3097.92   550.8 3098.66   567.2 3096.92   579.7 3093.75
     599 3094.77   622.2 3098.66   651.9 3098.78   681.6 3096.84   698.8 3098.11
   734.1 3103.75   749.5 3109.59   842.9 3154.95   892.6 3174.31   910.6 3183.42
#Mann= 5 ,-1,0
       0      .1       0     330     .06       0   429.7    .045       0
     475     .06       0     480      .1       0
#XS Ineff= 2 , 0
                          548.17          3116.9
Permanent Ineff=
       F       F
Bank Sta=429.7,475
XS Rating Curve= 0 ,0
Exp/Cntr=0.3,0.1

Type RM Length L Ch R = 1 ,57203   ,427.9,464.7,490.9
XS GIS Cut Line= 3
2340155.11444222584912.6175832622339864.59747939585025.911292836
2339411.75299818585456.870604185
#Sta/Elev= 30
       0 3246.01      89 3205.58   153.4 3171.95   192.1 3160.32   209.2 3152.33
   243.8 3139.93     290    3117   317.9 3098.79   331.4 3092.15   351.2 3087.76
   373.9 3088.78   424.8 3088.93   438.9 3089.74     456 3087.56     504 3090.32
   515.3  3088.8   533.3 3093.41   577.5    3091   616.1 3093.05   627.2 3090.45
   654.8 3090.28   698.9 3097.31   733.2 3108.78   748.6 3117.03   765.2  3123.6
     835 3165.44   844.6 3169.11   853.6 3175.37   870.1 3183.87     937 3203.73
#Mann= 4 ,-1,0
       0      .1       0     270     .06       0   373.9    .045       0
   424.8      .1       0
#XS Ineff= 2 , 0
                          540.28         3103.97
Permanent Ineff=
       F       F
Bank Sta=373.9,424.8
XS Rating Curve= 0 ,0
Exp/Cntr=0.3,0.1

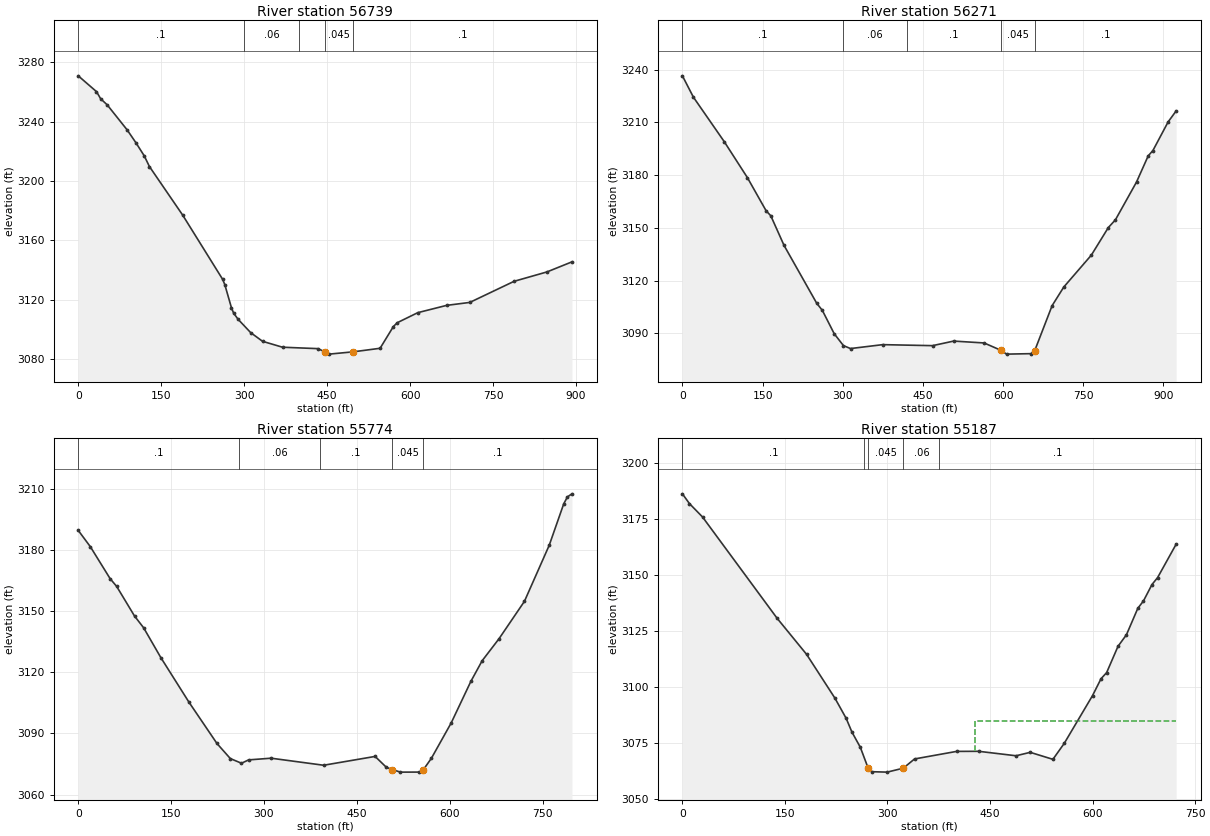
Type RM Length L Ch R = 1 ,56739   ,433.1,467.8,487.6
XS GIS Cut Line= 3
  2340108.540303584758.3238162012339442.13458947584804.552312847
2339221.37623385584762.993278434
#Sta/Elev= 30
       0 3270.86      33 3260.21    40.5 3255.43    52.5 3251.23    88.6 3234.32
   104.3 3225.73   119.3 3216.92   128.7 3209.69   188.8 3176.94     261 3133.65
     265 3130.03     277 3114.42     281 3110.75   289.1 3106.62   311.8 3097.65
   333.2 3091.81   369.3 3087.82   433.4 3086.86   445.9 3084.71   453.5 3083.16
   497.1 3084.71   545.7  3087.1   569.7 3101.75   576.7 3104.34   613.8 3111.12
     666 3116.04   707.9 3118.04     788 3132.28   847.3 3138.59   892.6  3145.4
#Mann= 5 ,-1,0
       0      .1       0     300     .06       0     400      .1       0
   445.9    .045       0   497.1      .1       0
Bank Sta=445.9,497.1
XS Rating Curve= 0 ,0
Exp/Cntr=0.3,0.1

Type RM Length L Ch R = 1 ,56271   ,463.7,497,525.8
XS GIS Cut Line= 2
2340078.99044222 584633.897723392339236.49823385584255.035234764
#Sta/Elev= 30
       0 3236.47    20.6 3224.32    78.3 3199.03   121.5 3178.63   156.6 3159.75
   165.4 3156.88   190.2 3140.02   251.2  3107.2   261.9 3103.06     284 3089.84
   301.3 3083.07   314.5  3081.4   374.8 3083.62     468 3083.05   507.5 3085.65
   564.5 3084.58   596.7  3080.3   606.4 3078.23   652.2  3078.5   659.2 3080.23
   691.7 3105.79   713.6 3116.41   765.1 3134.52   796.9  3150.2   810.1 3154.56
   849.6 3176.06   871.5 3190.97   880.3 3193.99   908.8 3210.29   923.8 3216.52
#Mann= 5 ,-1,0
       0      .1       0     300     .06       0     420      .1       0
   596.7    .045       0   659.2      .1       0
Bank Sta=596.7,659.2
XS Rating Curve= 0 ,0
Exp/Cntr=0.3,0.1

Type RM Length L Ch R = 1 ,55774   ,626,586.4,552.2
XS GIS Cut Line= 3
2340198.97167516584382.6022137162339859.07632532584086.308251801
2339693.87617456583781.671274598
#Sta/Elev= 30
       0 3189.73    19.6  3181.7    51.5 3166.03    62.1  3162.2    90.9 3147.68
   105.7 3141.86   133.4 3127.26   178.8 3105.38   224.1 3085.06   245.7 3077.65
   263.7 3075.37   275.2 3077.01   311.5 3077.84   396.4 3074.38   479.5 3078.71
   497.7 3073.37507.37953072.257   520.4    3071   551.2 3071.02557.47913072.194
   570.5 3077.84   602.4 3095.16   634.2 3115.58   652.4  3125.7   679.7 3136.53
   720.7 3154.88   760.7 3182.38   784.2 3202.78   790.2  3206.2   797.5 3207.68
#Mann= 5 ,-1,0
       0      .1       0     260     .06       0     390      .1       0
507.3795    .045       0557.4791      .1       0
Bank Sta=507.3795,557.4791
XS Rating Curve= 0 ,0
Exp/Cntr=0.3,0.1

Type RM Length L Ch R = 1 ,55187   ,520.2,503.4,486.7
XS GIS Cut Line= 3
2340551.20774054583629.1389651242340389.54187711583698.946445747
2339862.00655486583557.448799602
#Sta/Elev= 30
       0 3186.37    10.2 3182.04    29.4 3176.05   138.4  3130.9   181.7 3114.73
   223.1 3095.21   239.6 3086.17   247.9 3080.13   260.3 3073.26   271.7 3063.98
   276.9 3062.39   299.5  3062.2323.06453063.952   339.6 3068.08   401.1 3071.45
   433.4 3071.49   488.1  3069.5   508.8 3071.03     542 3067.91   558.5    3075
     600 3096.37   612.4 3103.88   620.6  3106.6   637.2 3118.32   649.6 3123.51
   666.2 3135.29   674.5  3138.6   686.9 3145.88   695.2 3149.02   722.3 3163.91
#Mann= 5 ,-1,0
       0      .1       0  266.09     .06       0   271.7    .045       0
323.0645     .06       0  376.09      .1       0
#XS Ineff= 2 , 0
                          428.62         3084.97
Permanent Ineff=
       F       F
Bank Sta=271.7,323.0645
XS Rating Curve= 0 ,0
Exp/Cntr=0.3,0.1