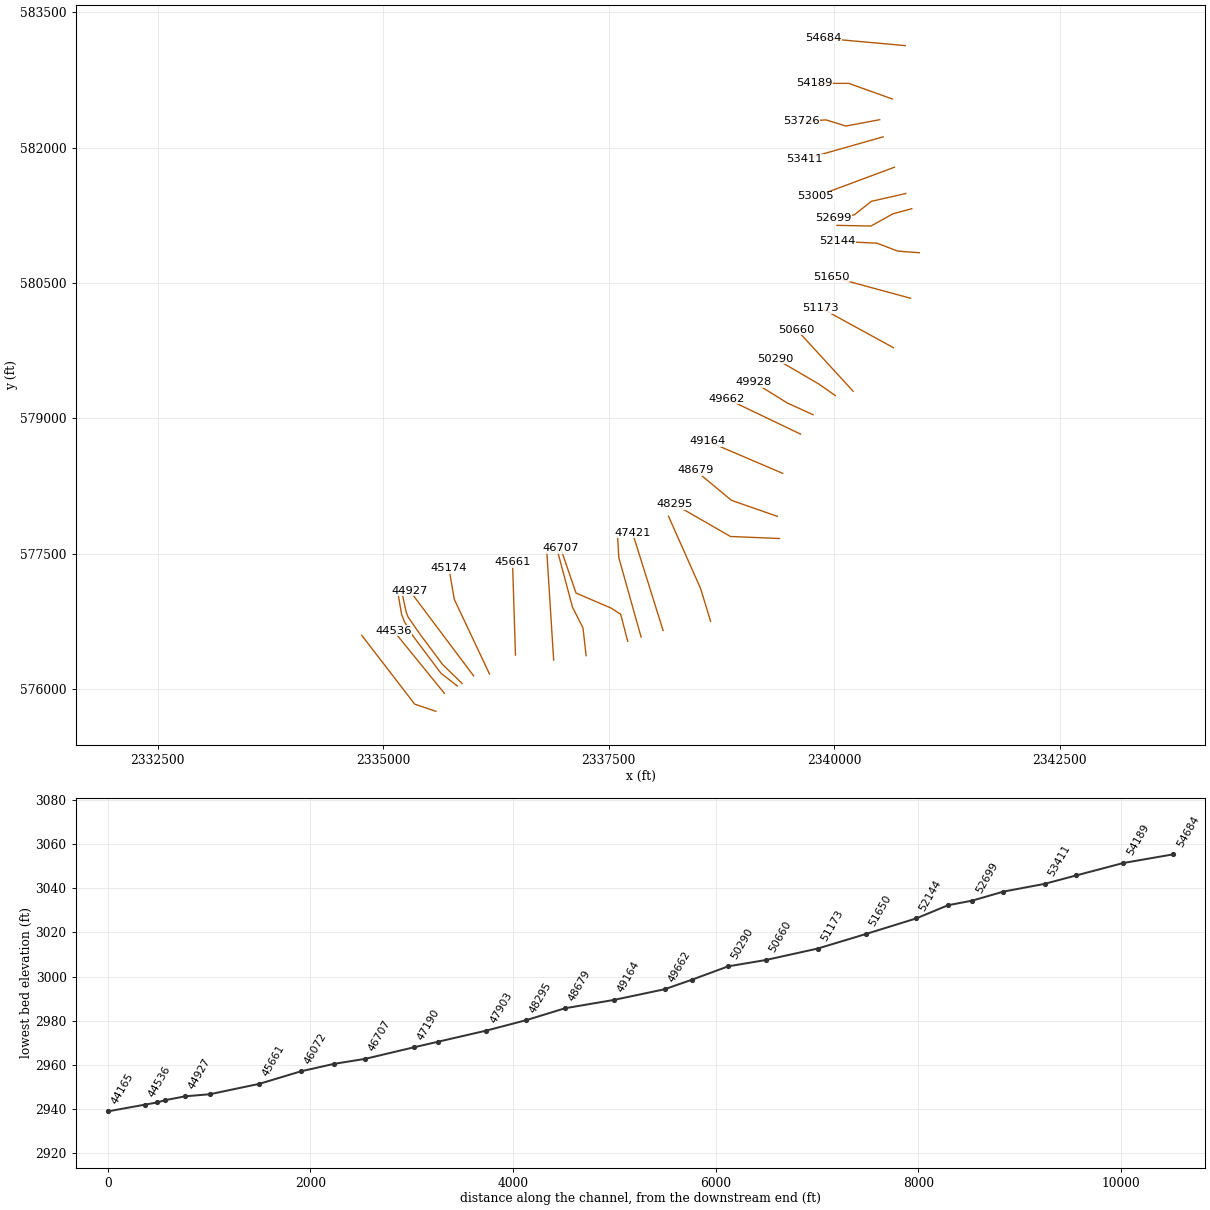
HEC-RAS study EFGRNBRRRV.prj: EFGRNBRRRV

--- EFGRNBRRRV.g01 (geometry) --- (continued)

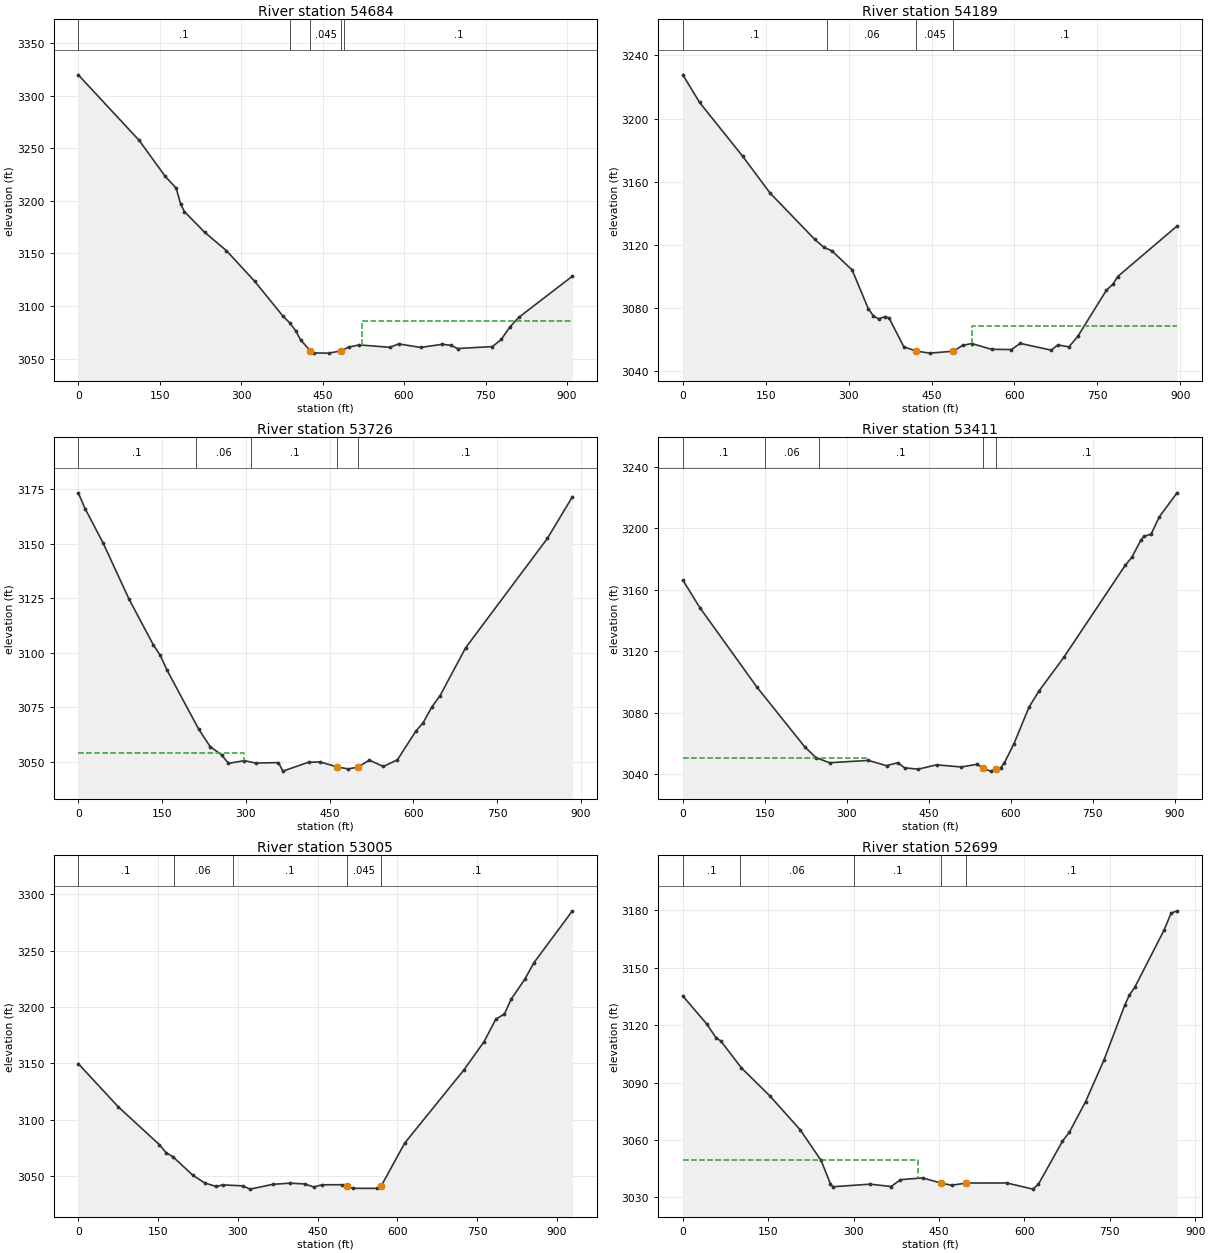
Type RM Length L Ch R = 1 ,54684   ,507.9,495.4,482.3
XS GIS Cut Line= 2
     2340787.865      583132.508     2339881.567      583214.501
#Sta/Elev= 30
       0 3319.88   112.1  3257.6   160.3 3223.27   180.4 3212.03   188.5 3197.04
   195.5 3189.86   232.6 3170.26   272.9 3152.69     325 3123.53   377.2 3090.31
   389.3 3084.18   400.8 3076.25   409.6 3067.76   427.3 3057.46   433.5 3055.41
   461.6 3055.25   484.7 3057.47   497.7 3060.97   517.8 3063.06     574 3060.77
   590.1 3064.02   630.4 3060.65   670.4 3063.66   686.5 3062.66   698.5 3059.63
   762.8 3061.47   778.9 3068.23   794.9 3080.11   811.4 3089.29     910  3128.4
#Mann= 5 ,-1,0
       0      .1       0     390     .06       0   427.3    .045       0
   484.7     .06       0     490      .1       0
#XS Ineff= 2 , 0
                          522.25         3086.18
Permanent Ineff=
       F       F
Bank Sta=427.3,484.7
XS Rating Curve= 0 ,0
Exp/Cntr=0.3,0.1

Type RM Length L Ch R = 1 ,54189   ,461.8,462.5,462.9
XS GIS Cut Line= 3
     2340644.653      582540.7682340159.61572952582714.302022186
2339780.56599264582714.128966485
#Sta/Elev= 30
       0 3227.69    30.2 3210.22   108.1 3176.15   157.7 3152.81   238.4 3123.51
   255.4 3118.32   269.8 3116.11   306.4 3103.98   335.5 3079.52   344.6 3074.94
   354.3 3073.02   365.9 3074.44     373 3073.68   399.8 3055.33422.16863052.588
   446.6 3051.31489.49843052.524   506.1 3056.21   522.6  3057.4   558.6 3053.72
   594.6  3053.6   610.6 3057.46   666.6  3053.2   678.6 3056.56   698.6 3055.22
   714.6 3061.93   766.6 3091.24   778.6  3095.1   786.6 3099.77   894.2 3131.83
#Mann= 4 ,-1,0
       0      .1       0     260     .06       0422.1686    .045       0
489.4984      .1       0
#XS Ineff= 2 , 0
                          523.38         3068.59
Permanent Ineff=
       F       F
Bank Sta=422.1686,489.4984
XS Rating Curve= 0 ,0
Exp/Cntr=0.3,0.1

Type RM Length L Ch R = 1 ,53726   ,293,314.7,332.6
XS GIS Cut Line= 4
2340504.30348436 582311.297772212340129.03344825582240.691020257
2339909.44799167582308.8383227762339637.29014013 582292.13874249
#Sta/Elev= 30
       0 3173.32    12.3 3166.06    44.9 3150.11      91 3124.52   134.4 3103.62
   146.7 3098.84   158.9 3092.02   215.9 3064.81   236.2 3056.94   256.6 3053.17
   268.8 3049.28   297.3 3050.52   317.6 3049.42   358.2 3049.63   366.4 3045.72
   412.1 3049.81     433 3049.91  463.98 3047.63   483.3 3046.72   501.2 3047.63
     521 3050.76   546.1 3047.85   571.2 3050.91   604.7 3064.22   617.1 3067.85
   633.1 3075.21   647.7 3080.38   693.2 3102.22   839.8 3152.48   884.4  3171.5
#Mann= 5 ,-1,0
       0      .1       0     210     .06       0     310      .1       0
  463.98    .045       0   501.2      .1       0
#XS Ineff= 2 , 0
          297.43 3053.89
Permanent Ineff=
       F       F
Bank Sta=463.98,501.2
XS Rating Curve= 0 ,0
Exp/Cntr=0.3,0.1

Type RM Length L Ch R = 1 ,53411   ,404.6,406.3,406.9
XS GIS Cut Line= 2
2340542.65324387582121.2671061782339672.79196636581874.059638325
#Sta/Elev= 30
       0 3166.13    31.2 3148.19   135.6 3096.53     223  3057.7   243.8  3050.6
   268.7 3047.34   339.4 3048.86   372.7 3045.44   393.5 3047.35   405.9 3044.01
   430.9 3043.16   464.2 3045.99   509.9 3044.57     539  3046.4  548.67 3043.61
     564 3041.88   572.3 3043.51   581.7 3044.11   588.2 3047.13   605.5 3059.38
   633.5 3083.53   651.3  3093.8     697 3115.84   809.3 3175.67   821.8 3181.09
   838.4 3192.31     844 3194.64   856.9 3196.05   871.7 3207.19   904.3 3222.95
#Mann= 5 ,-1,0
       0      .1       0     150     .06       0     250      .1       0
  548.67    .045       0   572.3      .1       0
#XS Ineff= 2 , 0
          337.83 3050.37
Permanent Ineff=
       F       F
Bank Sta=548.67,572.3
XS Rating Curve= 0 ,0
Exp/Cntr(USF)=0,0
Exp/Cntr=0.3,0.1

Type RM Length L Ch R = 1 ,53005   ,290.3,305.8,323
XS GIS Cut Line= 2
2340666.96380743581783.6769591992339796.53750056581459.959639466
#Sta/Elev= 30
       0 3149.69    75.5 3111.25   152.3 3077.91   165.1  3070.7     178 3067.09
   215.6 3050.61   237.7 3043.88   259.2 3040.72   271.8 3042.13     309 3041.28
   323.1 3038.38   365.7 3042.63   397.3 3043.67   425.5 3042.98   442.5 3040.32
   458.3 3042.23   495.6 3042.29  504.67 3040.93   516.9  3039.1     562 3039.08
   569.4  3041.2   613.8 3079.37   724.2 3143.74   762.6  3169.1   784.9  3189.2
     801 3193.69   813.8 3206.97   839.4 3224.62   856.3  3239.1   928.7 3285.21
#Mann= 5 ,-1,0
       0      .1       0     180     .06       0     290      .1       0
  504.67    .045       0   569.4      .1       0
Bank Sta=504.67,569.4
XS Rating Curve= 0 ,0
Exp/Cntr=0.3,0.1

Type RM Length L Ch R = 1 ,52699   ,248.9,239.8,227.9
XS GIS Cut Line= 4
2340793.08197065581492.4252919352340412.02601512581406.147404661
2340223.40157767 581257.021470152339989.98962784581216.505071888
#Sta/Elev= 30
       0 3135.22    41.9 3120.62    58.3 3113.38    66.6 3111.76   102.9 3097.66
   152.7 3083.06     206 3065.37   242.9 3049.28   259.3 3037.05   263.4 3035.57
     329 3036.91   365.9 3035.69   382.3 3039.26   421.1 3040.19454.0711 3037.45
   472.1 3036.34497.67013037.507     569 3037.54   614.9 3034.32   624.5 3036.82
   666.9 3059.34   679.1 3064.12   707.5 3080.02     740 3101.89   776.5 3130.56
   784.6 3135.79     794 3139.81   845.5 3169.71   857.7 3178.48   868.1 3179.72
#Mann= 5 ,-1,0
       0      .1       0     100     .06       0     300      .1       0
454.0711    .045       0497.6701      .1       0
#XS Ineff= 2 , 0
          412.39 3049.55
Permanent Ineff=
       F       F
Bank Sta=454.0711,497.6701
XS Rating Curve= 0 ,0
Exp/Cntr=0.3,0.1

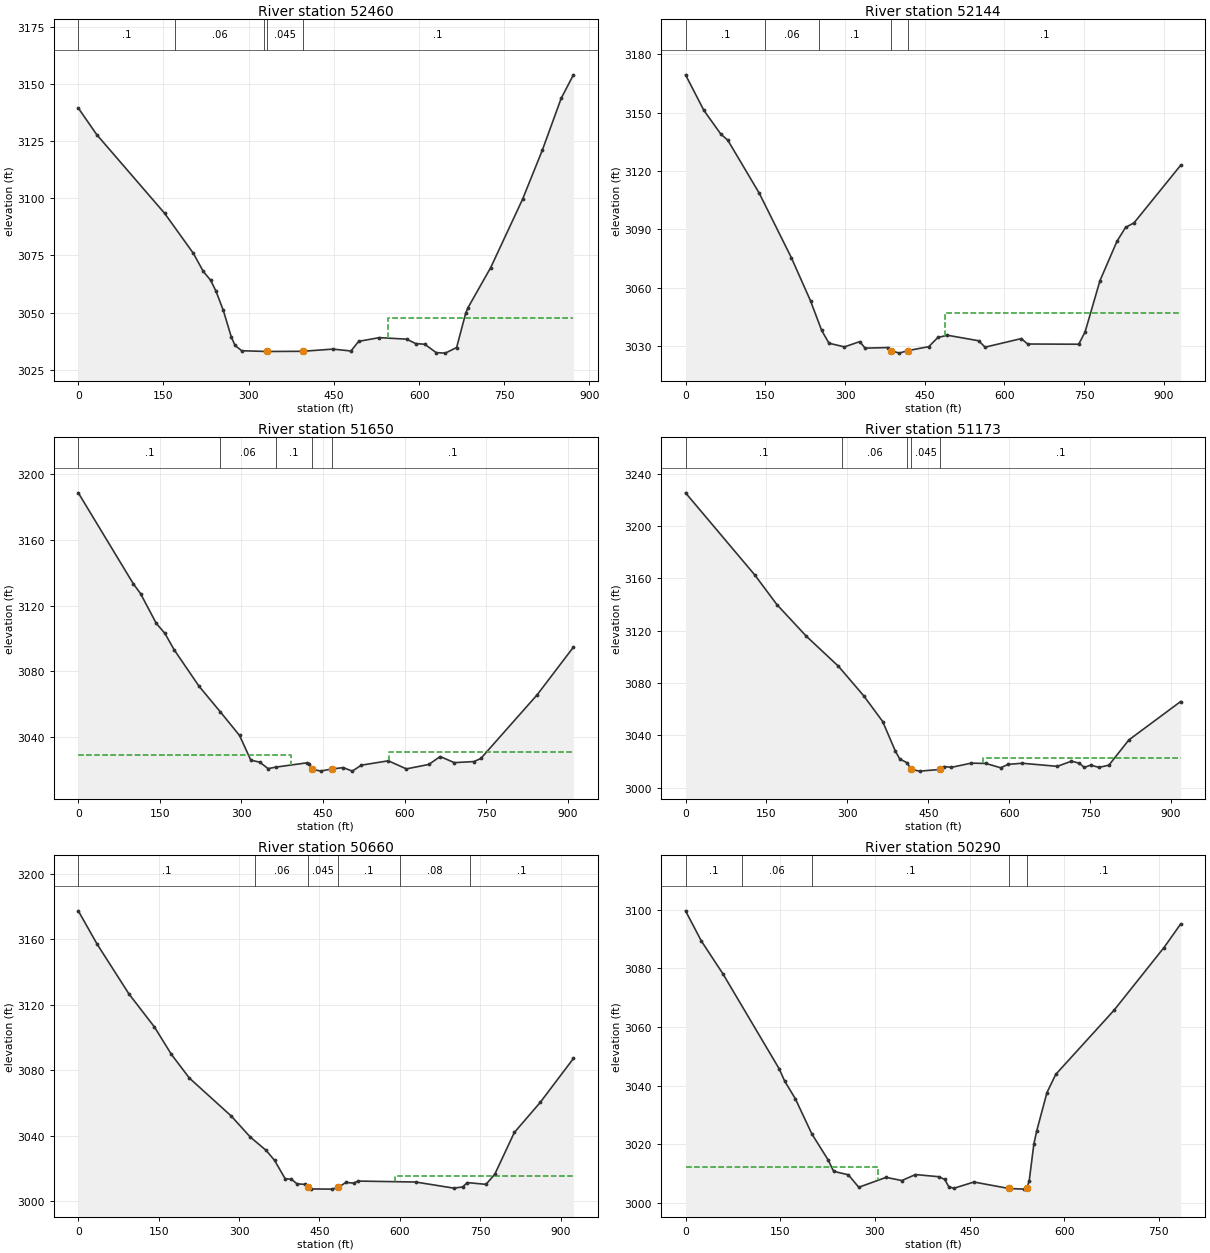
Type RM Length L Ch R = 1 ,52460   ,344.5,315.2,270.4
XS GIS Cut Line= 4
2340859.62993589581324.190994616 2340649.5305126581266.935494938
2340406.75193651581132.0483248272340030.60684369581139.300662126
#Sta/Elev= 30
       0 3139.55    32.6 3127.86   151.9 3093.48   202.6 3075.93     220 3068.03
     233 3064.14   242.2  3059.5   255.3 3050.97   269.6 3039.14   275.9 3035.64
   287.7 3033.28   331.8 3032.95  394.99 3033.03   448.1 3033.99   480.1 3033.17
   493.6 3037.38   530.1 3039.02   578.1 3038.35   594.1 3036.41   610.1 3036.12
   630.1 3032.46   646.1 3032.23   666.1 3034.69   682.1 3049.75   686.1 3052.12
   726.1  3069.7   782.1 3099.57   817.1 3121.17   850.1 3143.75   871.7 3154.09
#Mann= 5 ,-1,0
       0      .1       0     170     .06       0  327.76      .1       0
   331.8    .045       0  394.99      .1       0
#XS Ineff= 2 , 0
                          544.79         3047.61
Permanent Ineff=
       F       F
Bank Sta=331.8,394.99
XS Rating Curve= 0 ,0
Exp/Cntr(USF)=0,0
Exp/Cntr=0.3,0.1

Type RM Length L Ch R = 1 ,52144   ,491.1,494.8,498.2
XS GIS Cut Line= 4
2340942.61194499580835.9694798022340702.62044234580853.901424307
2340473.54659985580942.1664131132340028.50476498580961.811451237
#Sta/Elev= 30
       0  3169.4    34.5  3151.1    66.6 3138.83    79.4 3135.82   138.8 3108.45
     199 3075.39   235.1 3053.17   256.1 3037.95   269.8 3031.36     299 3029.46
   327.7 3032.17   337.9 3028.81   380.5 3029.12   387.4 3027.52   401.9 3026.25
   418.4 3027.54   457.6 3029.58   474.8 3034.31   492.8 3035.45   551.5 3032.61
   563.6 3029.32   631.7 3033.72   643.7 3030.94   739.8 3030.83   751.8 3037.18
   779.8 3063.56   811.8 3083.79   827.9 3090.92   843.9 3093.27   931.6 3122.88
#Mann= 5 ,-1,0
       0      .1       0     150     .06       0  250.66      .1       0
   387.4    .045       0   418.4      .1       0
#XS Ineff= 2 , 0
                          488.45         3046.93
Permanent Ineff=
       F       F
Bank Sta=387.4,418.4
XS Rating Curve= 0 ,0
Exp/Cntr=0.3,0.1

Type RM Length L Ch R = 1 ,51650   ,488.5,476.6,467
BEGIN DESCRIPTION:
LOB IFA added to correct profile crossing
END DESCRIPTION:
XS GIS Cut Line= 2
      2340846.32      580330.958     2339967.762      580569.713
#Sta/Elev= 30
       0 3188.83   101.3 3133.33   114.4 3127.46   143.2 3109.39   159.3 3103.15
   176.3 3093.17   221.9 3071.03     261 3055.42   296.5 3040.97   317.2 3025.94
   333.8 3024.67     349 3020.75   362.8 3021.65   420.9 3024.31     425 3023.76
   429.2 3020.42   445.7 3019.28   466.1 3020.52   487.2 3021.39   503.8 3019.23
   520.4 3022.86   570.1 3025.52   603.3 3020.59   644.7 3023.32   665.4 3028.13
   691.3 3024.41   727.6 3025.06   740.2 3026.95   843.7 3065.73   910.4 3094.77
#Mann= 5 ,-1,0
       0      .1       0     261     .06       0   362.8      .1       0
   429.2    .045       0   466.1      .1       0
#XS Ineff= 2 , 0
           390.7 3029.03  571.82         3030.66
Permanent Ineff=
       F       F
Bank Sta=429.2,466.1
XS Rating Curve= 0 ,0
Exp/Cntr=0.3,0.1

Type RM Length L Ch R = 1 ,51173   ,530.7,513.2,499.9
XS GIS Cut Line= 2
     2340656.771      579782.588     2339851.452       580223.25
#Sta/Elev= 30
       0 3225.35   128.4 3162.56   169.4 3139.91   224.1 3115.69   283.4 3092.83
   330.4 3070.19   365.5 3050.57   388.7 3028.25     397 3021.99   411.1 3018.96
   417.9 3014.07   417.9 3014.06   433.8 3012.64     472  3013.9   479.4 3016.15
   493.1 3015.54   529.6 3018.75     557  3018.5   584.3  3015.2     598 3017.81
   624.2 3018.66   689.2  3016.3   715.5 3020.24   730.3 3018.68   739.3 3015.43
   750.9 3017.23   766.7 3015.52   784.9 3017.18     822  3036.5     918 3065.85
#Mann= 5 ,-1,0
       0      .1       0     290     .06       0     410      .1       0
   417.9    .045       0     472      .1       0
#XS Ineff= 2 , 0
                          551.31          3022.7
Permanent Ineff=
       F       F
Bank Sta=417.9,472
XS Rating Curve= 0 ,0
Exp/Cntr=0.3,0.1

Type RM Length L Ch R = 1 ,50660   ,350.6,370.2,379.5
XS GIS Cut Line= 2
     2340208.946      579300.5052339584.80023112579981.379091899
#Sta/Elev= 30
       0 3177.35      35 3157.07    94.4 3126.66     142 3106.46   173.7 3089.71
   207.1 3075.29   285.3  3052.1   320.9 3039.23   350.4 3031.13   366.2 3024.99
   385.9  3013.8   397.7 3013.48   407.9 3010.72   422.9 3010.34   428.5 3008.71
   434.2 3007.57     473 3007.45   485.1 3008.52   499.3 3011.56   513.5 3011.11
   522.1 3012.37   629.5 3011.79   700.9 3008.04   717.2 3008.83   725.8 3011.43
   760.6 3010.37   776.9 3016.45   813.5 3042.03   861.7 3060.35   923.7  3087.2
#Mann= 6 ,-1,0
       0      .1       0     330     .06       0   428.5    .045       0
   485.1      .1       0     600     .08       0     730      .1       0
#XS Ineff= 2 , 0
                          591.39         3015.16
Permanent Ineff=
       F       F
Bank Sta=428.5,485.1
XS Rating Curve= 0 ,0
Exp/Cntr=0.3,0.1

Type RM Length L Ch R = 1 ,50290   ,363.3,361.9,359.5
XS GIS Cut Line= 3
 2340012.6141643579251.164614994 2339826.0175531579381.576545905
2339345.38789402579662.521030981
#Sta/Elev= 30
       0  3099.7    24.9 3089.43    59.1 3078.21   148.3 3045.73   157.1  3041.5
   174.1 3035.42     200  3023.5   225.8 3014.61   234.6 3010.68   257.9  3009.5
   274.4 3005.24   317.8 3008.62   342.7 3007.53   364.2 3009.58   401.2 3008.84
   410.5 3007.92   417.1 3005.42     425 3004.89   456.9 3007.03   512.2 3004.82
   535.6  3004.6  540.61 3004.86   544.5 3007.52   551.8 3019.95   556.2 3024.37
   572.6 3037.61   586.5 3043.81   678.7 3065.69     758 3087.16   784.4  3095.2
#Mann= 5 ,-1,0
       0      .1       0      90     .06       0     200      .1       0
   512.2    .045       0  540.61      .1       0
#XS Ineff= 2 , 0
          305.01 3012.02
Permanent Ineff=
       F       F
Bank Sta=512.2,540.61
XS Rating Curve= 0 ,0
Exp/Cntr=0.3,0.1

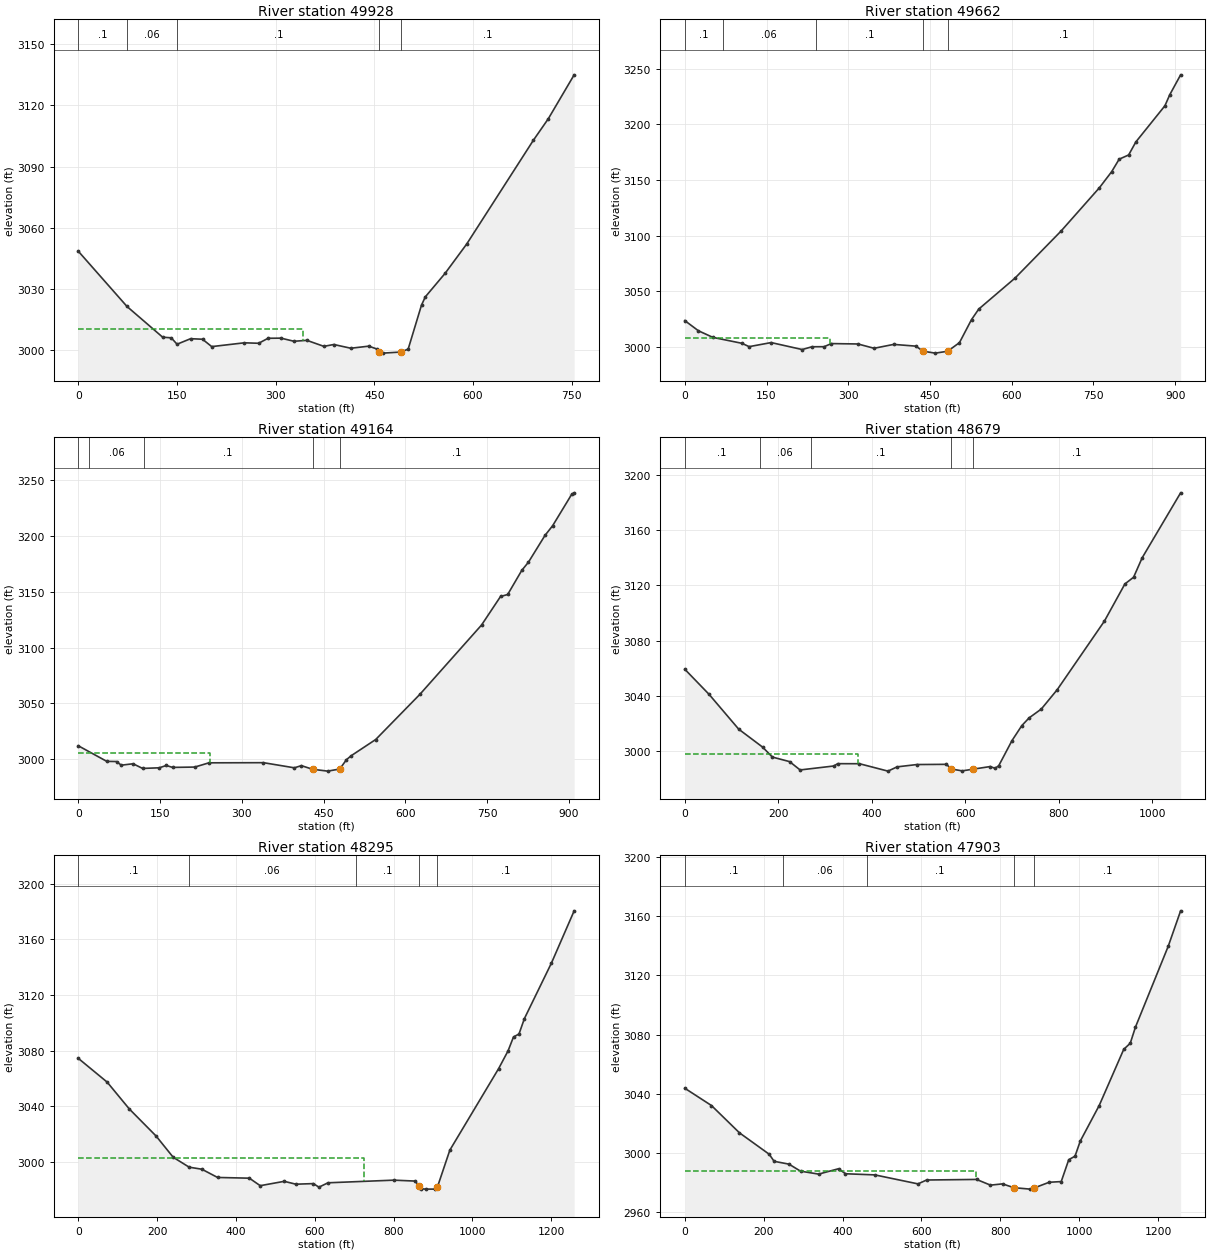
Type RM Length L Ch R = 1 ,49928   ,261.3,265.7,270.9
XS GIS Cut Line= 3
2339764.91227293579040.0136977752339481.32110086579168.491466337
 2339105.2886075579401.944972628
#Sta/Elev= 30
       0 3048.47      74 3021.38   128.2 3006.31   141.3    3006   150.1 3002.86
   170.7 3005.57   188.8 3005.31   202.8 3001.69   252.3 3003.55   274.2 3003.33
   288.5 3005.78   308.2 3005.84   327.8 3004.31   347.5 3004.76   373.3 3001.82
   388.5 3002.72   414.3 3000.89   441.6 3001.91   453.9 3000.52   457.9  2999.1
   463.3 2998.49   489.9 2999.02   501.5 3000.45   521.8 3022.06   527.6  3026.1
   557.5 3037.57   590.5 3052.01   691.8 3102.89   714.6 3113.49   753.9 3135.03
#Mann= 5 ,-1,0
       0      .1       0      74     .06       0   150.1      .1       0
   457.9    .045       0   489.9      .1       0
#XS Ineff= 2 , 0
           340.9 3010.57
Permanent Ineff=
       F       F
Bank Sta=457.9,489.9
XS Rating Curve= 0 ,0
Exp/Cntr(USF)=0,0
Exp/Cntr=0.3,0.1

Type RM Length L Ch R = 1 ,49662   ,496.6,498.4,500.2
XS GIS Cut Line= 2
     2339626.719      578824.284     2338806.101      579217.586
#Sta/Elev= 30
       0  3023.5      25 3014.35    51.6  3008.4   104.8 3003.08   118.1 3000.07
   158.5 3003.73   215.5 2997.47   233.4 2999.97   255.7 3000.03     269 3002.83
   317.8 3002.47   347.4  2998.6   383.4 3002.09   424.2 3000.52   437.1 2995.98
   459.7 2994.24   482.3 2995.91   504.1 3003.67   526.2 3024.38   539.5 3033.86
   606.1 3061.74   690.4 3103.96     761 3143.04   783.5  3157.5   797.2  3168.7
   814.6  3172.5   827.9 3184.26   881.2 3216.76   890.1  3226.7     910 3244.58
#Mann= 5 ,-1,0
       0      .1       0      70     .06       0     240      .1       0
   437.1    .045       0   482.3      .1       0
#XS Ineff= 2 , 0
          266.09 3007.64
Permanent Ineff=
       F       F
Bank Sta=437.1,482.3
XS Rating Curve= 0 ,0
Exp/Cntr=0.3,0.1

Type RM Length L Ch R = 1 ,49164   ,496.4,484.5,471.4
XS GIS Cut Line= 2
     2339428.578      578389.098     2338591.979      578747.164
#Sta/Elev= 30
       0  3012.1    52.2 2998.17    70.1 2998.02    78.8 2994.74   100.5 2996.02
   117.9 2991.85   148.4  2992.4   161.4 2994.47     173 2992.77   213.7 2993.06
   239.7 2996.86   339.8 2996.99   396.4  2992.4   409.4 2994.33     430 2991.08
   457.7 2989.43   479.8 2991.32   492.1 2999.68   500.8 3003.22   545.8 3017.73
     627 3058.22   740.1 3120.21   774.9 3145.72     788 3147.49   813.9  3169.1
   826.1  3176.4   856.5 3200.39   870.6  3209.1   905.4 3237.07     910 3238.47
#Mann= 5 ,-1,0
       0      .1       0      20     .06       0     120      .1       0
     430    .045       0   479.8      .1       0
#XS Ineff= 2 , 0
           241.4 3005.93
Permanent Ineff=
       F       F
Bank Sta=430,479.8
XS Rating Curve= 0 ,0
Exp/Cntr=0.3,0.1

Type RM Length L Ch R = 1 ,48679   ,376.8,384.2,391.3
XS GIS Cut Line= 3
2339369.15597999577912.6253503222338860.52472048578089.996586518
     2338458.767      578423.612
#Sta/Elev= 30
       0 3059.28    51.9 3041.15   115.4 3015.96   166.3 3003.05   187.4  2995.8
   224.2 2992.53   246.7  2986.5   318.8 2989.36   327.2 2991.04   373.8    2991
   434.7 2985.65   454.3 2988.74   496.7 2990.41   559.9 2990.56   570.3 2987.18
   593.7 2985.83   617.1 2987.08   653.5 2988.96   663.9 2987.67   671.8 2989.61
   700.2 3007.78   721.1 3018.55   736.7 3024.13   762.8 3030.52   796.8 3044.48
   897.9 3094.11   941.7 3120.94   960.3 3125.79   978.6 3139.82  1060.9 3186.78
#Mann= 5 ,-1,0
       0      .1       0     160     .06       0     270      .1       0
   570.3    .045       0   617.1      .1       0
#XS Ineff= 2 , 0
          370.86 2998.37
Permanent Ineff=
       F       F
Bank Sta=570.3,617.1
XS Rating Curve= 0 ,0
Exp/Cntr=0.3,0.1

Type RM Length L Ch R = 1 ,48295   ,421.6,391.3,364.3
XS GIS Cut Line= 3
2339393.27758873577666.560792543 2338849.6890853577689.204702188
2338230.76698428578045.359342727
#Sta/Elev= 30
       0 3074.35    73.2 3057.25   129.2 3037.99   197.3 3018.47   240.7 3003.18
   281.3 2996.04   313.4 2994.58   353.3 2988.65     434 2988.13   461.5 2982.73
   522.4 2985.86     552  2983.8   596.6 2984.23   610.4 2981.65   633.5 2984.81
   800.6 2986.71     855 2986.04   864.4 2982.24   868.9  2980.5     882 2980.25
   905.8 2980.27   911.3 2981.87   942.7 3008.34  1066.6 3067.06  1090.4 3079.78
  1104.2 3089.78  1118.1 3091.89  1131.9 3103.03  1200.5 3142.99  1258.1 3180.55
#Mann= 5 ,-1,0
       0      .1       0     280     .06       0  704.06      .1       0
   864.4    .045       0   911.3      .1       0
#XS Ineff= 2 , 0
          724.06 3002.45
Permanent Ineff=
       F       F
Bank Sta=864.4,911.3
XS Rating Curve= 0 ,0
Exp/Cntr=0.3,0.1

Type RM Length L Ch R = 1 ,47903   ,488,482.7,477.6
XS GIS Cut Line= 3
  2338629.160259576748.4690682762338518.16927473577112.747170514
2338162.42894051577913.874403168
#Sta/Elev= 30
       0 3043.72    67.6 3032.05   138.7 3013.58     214 2999.14   226.5 2994.36
   264.2 2992.44   293.5 2987.69   339.4 2985.71     390 2989.34   407.5 2985.94
   481.9 2985.18   591.4  2979.1   613.2 2981.72   739.9 2982.11   775.2 2978.25
   805.8 2979.11   834.2 2976.55   875.8 2975.56   885.8 2976.32     924  2980.2
   954.6 2980.66   973.7 2995.46   989.6 2997.81  1002.8 3007.97  1050.9 3032.05
  1113.1 3069.99  1129.7 3074.14  1142.8    3085    1226 3139.67  1257.4 3163.59
#Mann= 5 ,-1,0
       0      .1       0     250     .06       0  460.81      .1       0
   834.2    .045       0   885.8      .1       0
#XS Ineff= 2 , 0
           739.6 2987.89
Permanent Ineff=
       F       F
Bank Sta=834.2,885.8
XS Rating Curve= 0 ,0
Exp/Cntr(USF)=0,0
Exp/Cntr=0.3,0.1

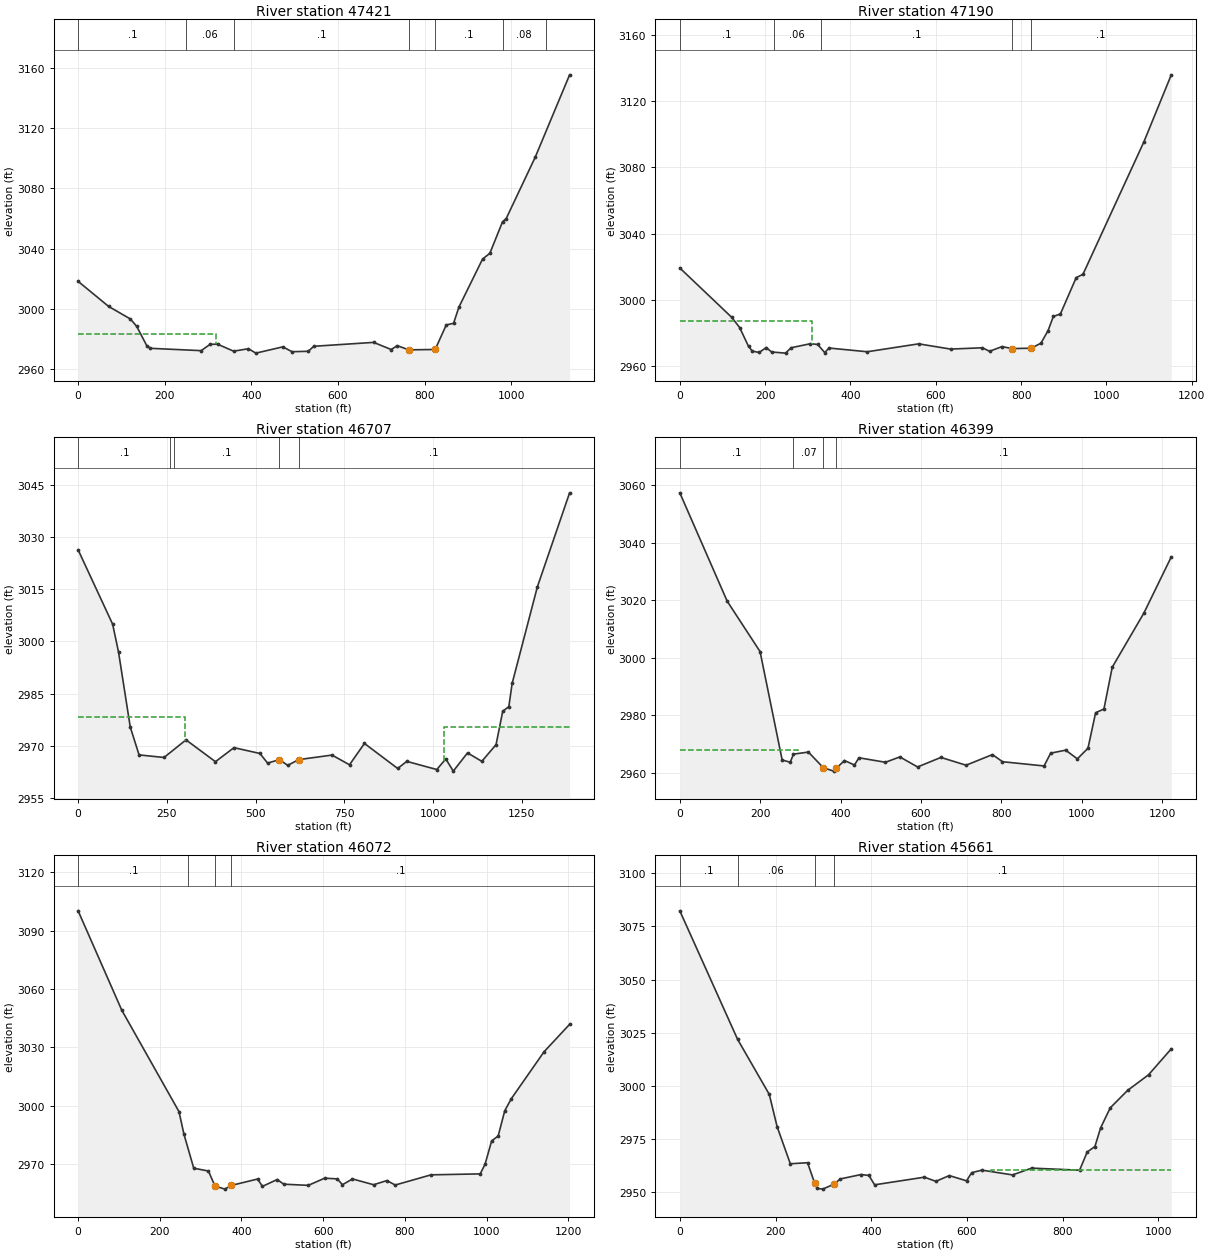
Type RM Length L Ch R = 1 ,47421   ,233.5,231.1,229.8
XS GIS Cut Line= 2
2338102.66456436576646.0158520232337763.99976619577728.889429375
#Sta/Elev= 30
       0 3018.22    70.4 3001.54   120.7 2993.18   135.4  2988.2   158.4 2975.47
   166.8 2973.66   284.1 2972.11   304.6  2976.3   321.8 2976.43   358.9 2971.76
   393.1 2973.39   410.4 2970.46   472.7 2974.64   493.7  2971.4   531.4 2971.68
     544 2975.01   682.3 2977.61   722.8 2972.85   736.7 2975.44   763.3 2972.64
   824.3 2972.89   849.9 2989.24   866.7 2990.28   879.2 3001.15   933.7 3033.07
   950.5 3036.88   979.8 3057.88   988.2 3059.98  1055.3 3100.86  1134.6 3155.63
#Mann= 7 ,-1,0
       0      .1       0     250     .06       0     360      .1       0
   763.3    .045       0   824.3      .1       0     980     .08       0
    1080      .1       0
#XS Ineff= 2 , 0
          318.04 2983.25
Permanent Ineff=
       F       F
Bank Sta=763.3,824.3
XS Rating Curve= 0 ,0
Exp/Cntr(USF)=0,0
Exp/Cntr=0.3,0.1

Type RM Length L Ch R = 1 ,47190   ,439.7,483.1,517.5
XS GIS Cut Line= 3
2337858.68744573576574.1034619742337611.82215543577454.132506101
2337598.10741708577691.854637502
#Sta/Elev= 30
       0 3019.38   121.3 2989.71   140.3 2983.45   161.1 2972.09     170 2969.24
     186 2968.42   202.6 2971.39   215.1 2968.71   247.9 2968.02   260.8 2971.25
   306.3 2973.71   323.1 2973.25   339.7 2968.37   349.9 2971.09   439.4 2968.85
   559.9 2973.62   634.7 2970.46   709.4 2971.25   726.1 2969.11   755.1 2971.95
   779.4 2970.76  823.48 2970.98   846.5    2974   863.2 2981.57   875.6 2990.12
   892.2 2991.66   929.1  3013.5   945.1 3015.58  1087.7 3095.32  1152.1 3135.85
#Mann= 5 ,-1,0
       0      .1       0     220     .06       0     330      .1       0
   779.4    .045       0  823.48      .1       0
#XS Ineff= 2 , 0
          309.63 2987.14
Permanent Ineff=
       F       F
Bank Sta=779.4,823.48
XS Rating Curve= 0 ,0
Exp/Cntr(USF)=0,0
Exp/Cntr=0.3,0.1

Type RM Length L Ch R = 1 ,46707   ,339.5,307.5,283.7
XS GIS Cut Line= 5
2337710.44155605576527.0095641092337632.31843026576826.728886635
2337526.30397138576895.0242233842337137.58911989577061.691078517
2336966.76627815577559.088881225
#Sta/Elev= 30
       0 3026.31    97.3 3004.96   113.9 2996.93   146.9 2975.44   171.7 2967.43
     242 2966.69     304 2971.74   386.9 2965.48   439.1 2969.51   512.2 2967.84
   533.9 2965.07     567 2966.07   590.5 2964.44621.77982966.081   715.4 2967.38
   764.6 2964.59   806.7 2970.72   900.4 2963.53   925.9 2965.57  1010.5 2963.23
  1035.9 2966.27    1057 2962.77  1097.1 2968.01  1137.4 2965.58  1177.5 2970.38
  1196.3 2979.95  1213.5 2981.29  1222.8 2987.94  1293.9 3015.68  1384.7 3042.68
#Mann= 5 ,-1,0
       0      .1       0     260     .06       0     270      .1       0
     567    .045       0621.7798      .1       0
#XS Ineff= 2 , 0
           301.3 2978.22 1031.66         2975.58
Permanent Ineff=
       F       F
Bank Sta=567,621.7798
XS Rating Curve= 0 ,0
Exp/Cntr=0.3,0.1

Type RM Length L Ch R = 1 ,46399   ,342.9,327.3,311.8
XS GIS Cut Line= 4
2337249.21527518576368.1104147362337214.35460524576677.102716522
2337098.68056406576903.6970711642336929.13094205577539.112009707
#Sta/Elev= 30
       0 3057.38   117.8 3019.69   199.7 3002.13   254.7  2964.4   274.8  2963.6
   282.9 2966.43     320 2967.14   357.2 2961.69   382.9 2960.51   389.9 2961.56
   409.8  2964.2   434.6 2962.64   445.8 2965.16   511.8 2963.59   547.5 2965.46
   591.7 2961.96   649.7 2965.28   712.4 2962.57     778 2966.27   802.9 2963.79
   906.4 2962.31   922.9 2966.77   960.2 2967.81   989.2 2964.78  1015.7 2968.48
  1034.7 2980.83  1055.4 2982.14  1076.1 2996.69  1154.8 3015.53    1223 3035.09
#Mann= 4 ,-1,0
       0      .1       0   282.9     .07       0   357.2    .045       0
   389.9      .1       0
#XS Ineff= 2 , 0
             295 2967.84
Permanent Ineff=
       F       F
Bank Sta=357.2,389.9
XS Rating Curve= 0 ,0
Exp/Cntr(USF)=0,0
Exp/Cntr=0.3,0.1

Type RM Length L Ch R = 1 ,46072   ,412,411,409.6
XS GIS Cut Line= 2
2336889.41703145576318.6742214962336813.61992792577519.657483627
#Sta/Elev= 30
       0 3100.26   106.7 3049.23     247 2996.99     259 2985.48   283.1  2967.9
   319.1 2966.43     335 2958.77   359.2 2957.13   375.2 2959.04   439.4 2962.32
   451.4 2958.55   487.5 2962.08   503.5 2959.67   563.6 2959.07   603.7 2962.76
   634.5  2962.4   647.3 2959.41   671.8 2962.36   723.6 2959.39     756 2961.53
   776.4 2959.24   864.2 2964.48   984.5 2964.97   996.5 2969.98  1012.5 2981.93
  1028.5 2984.46  1044.6 2997.41  1060.6 3003.62  1140.8 3027.76  1203.4 3041.88
#Mann= 4 ,-1,0
       0      .1       0     270     .07       0     335    .045       0
   375.2      .1       0
Bank Sta=335,375.2
XS Rating Curve= 0 ,0
Exp/Cntr=0.3,0.1

Type RM Length L Ch R = 1 ,45661   ,469.2,487.1,504.5
XS GIS Cut Line= 2
2336466.21311599576374.4028630442336433.42130931577400.723692667
#Sta/Elev= 30
       0 3082.33   120.7 3021.92   186.9 2996.03   203.3 2980.82   230.9  2963.4
   266.9 2963.89   281.9 2954.17   286.9 2951.84   298.4 2951.47   322.7 2953.85
   334.9 2956.24     379 2958.34     395 2957.89     407  2953.5     511 2957.09
     535 2955.14     563 2957.84   599.1 2955.37   609.7  2959.2   631.1  2960.4
   695.1 2958.15   735.2 2961.35   835.2 2960.37   851.2 2968.96   867.2 2971.49
   879.2 2980.29   899.2 2989.67   935.4 2997.87   979.3 3005.24  1026.8 3017.44
#Mann= 4 ,-1,0
       0      .1       0   120.7     .06       0   281.9    .045       0
   322.7      .1       0
#XS Ineff= 2 , 0
                           651.1          2960.5
Permanent Ineff=
       F       F
Bank Sta=281.9,322.7
XS Rating Curve= 0 ,0
Exp/Cntr=0.3,0.1

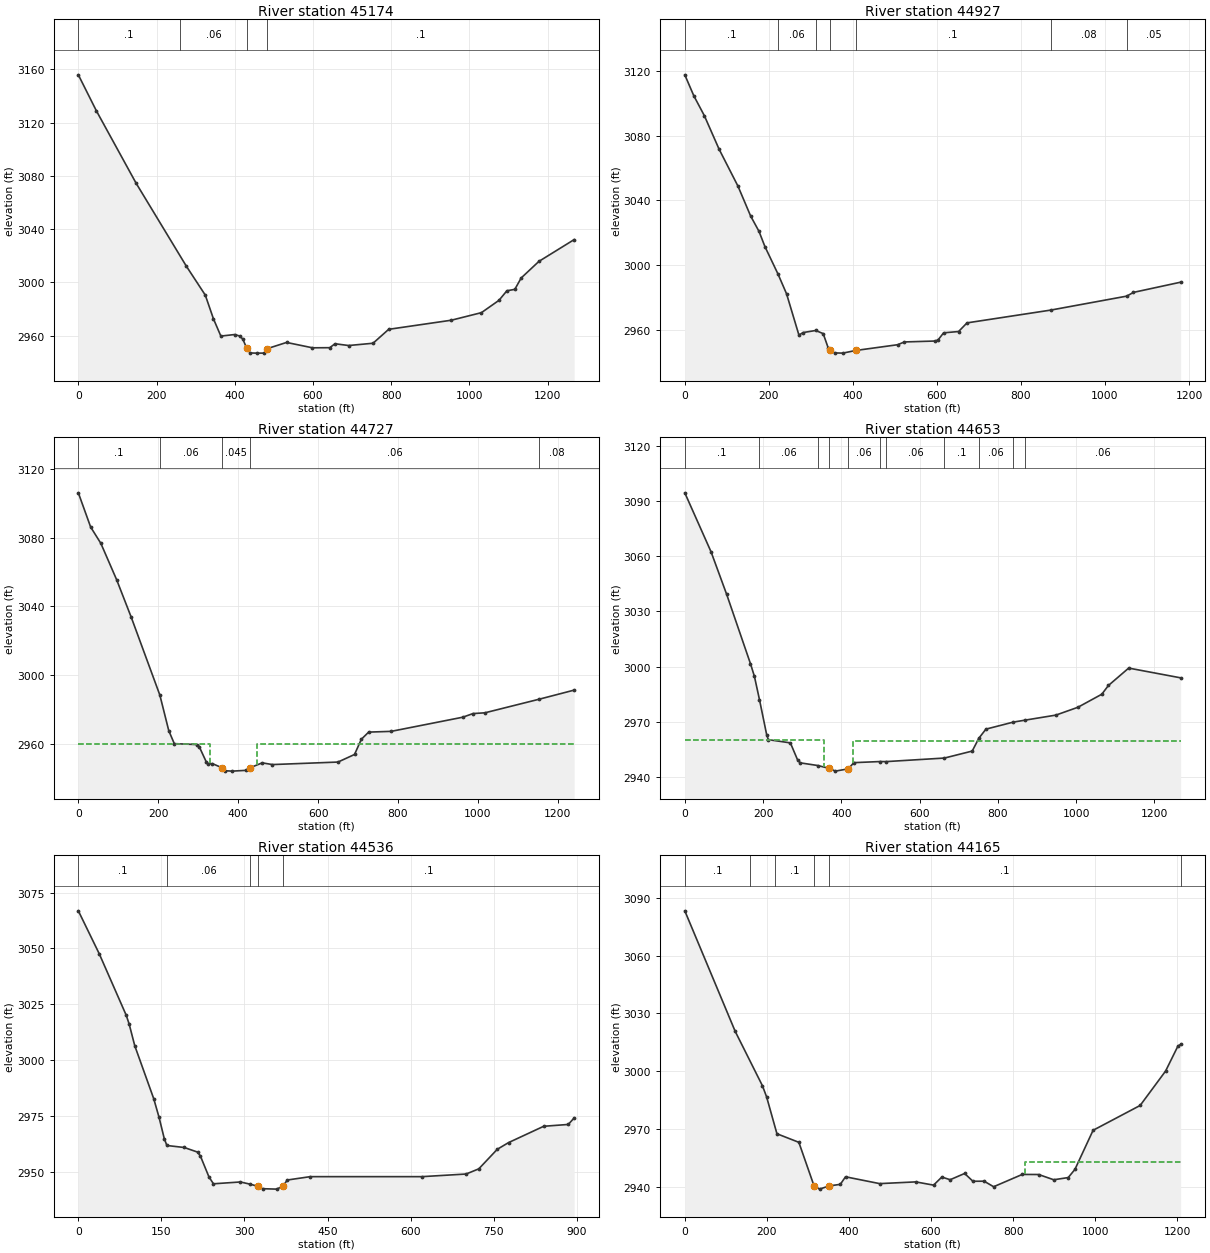
Type RM Length L Ch R = 1 ,45174   ,236.9,246.4,256.1
XS GIS Cut Line= 3
     2336178.379      576163.5552335787.50646929576993.218418217
 2335728.0404692577338.759372879
#Sta/Elev= 30
       0 3155.92      46 3128.95   147.7 3074.48   275.9 3012.25   324.6 2990.38
   345.5 2972.53   364.4 2959.59   399.7 2960.75     413 2959.61   420.7 2957.21
   430.7 2950.32   439.5 2946.89   455.7 2946.78   474.9 2946.79  482.032950.065
   532.4 2954.81   598.7 2950.78   642.9 2950.87   656.2 2953.82   691.2  2952.5
   753.5 2954.21   793.5 2964.67   953.6 2971.51  1030.7 2977.21  1075.4 2986.44
  1095.7 2993.63    1116 2994.71  1132.2 3003.25  1177.7 3015.75  1267.7  3032.1
#Mann= 4 ,-1,0
       0      .1       0     260     .06       0   430.7    .045       0
  482.03      .1       0
Bank Sta=430.7,482.03
XS Rating Curve= 0 ,0
Exp/Cntr=0.3,0.1

Type RM Length L Ch R = 1 ,44927   ,200.1,200.5,200.8
BEGIN DESCRIPTION:
structure xs 4
END DESCRIPTION:
XS GIS Cut Line= 2
2336001.85265944576143.9490266882335293.64480208 577087.79928143
#Sta/Elev= 30
       0 3117.54    21.5 3104.58    46.5 3092.35    81.6 3071.66   126.6 3048.82
   156.6 3030.47   176.6 3020.95   190.6 3011.61   221.6 2994.74   242.1 2982.47
   271.6 2956.96   281.6 2958.52   311.6 2959.79   329.4 2957.85   341.6 2948.79
   344.9 2947.67   356.6 2945.96     376 2945.82   406.6 2947.45   506.6 2951.01
   522.6 2952.72     596 2953.29   602.6 2953.92     616 2958.35   651.6 2959.15
   671.6 2964.48   870.6 2972.36  1051.7 2980.99  1067.8  2983.3    1180 2989.59
#Mann= 7 ,-1,0
       0      .1       0   221.6     .06       0   311.6      .1       0
   344.9    .045       0   406.6      .1       0   870.6     .08       0
  1051.7     .05       0
Bank Sta=344.9,406.6
XS Rating Curve= 0 ,0
Exp/Cntr(USF)=0,0
Exp/Cntr=0.5,0.3

Type RM Length L Ch R = 1 ,44727   ,75,73.6,73.8
BEGIN DESCRIPTION:
structure xs 3
END DESCRIPTION:
XS GIS Cut Line= 6
2335874.30711084576059.7557812352335658.01698763576270.354059091
2335403.30690833576611.8647799382335275.24038802 576796.84975373
2335253.89596796576852.3452458682335206.93824385577075.750175755
#Sta/Elev= 30
       0 3106.01    30.8  3086.1    56.3 3076.62    95.9  3055.4   132.6 3033.47
     204 2988.28   226.3 2967.57   240.1 2960.03   296.7 2959.49   302.4 2958.32
   320.4 2949.27   325.4 2948.07   335.3 2948.41   359.5    2946   368.1 2944.24
   385.2 2944.03   418.7 2944.47  429.512945.964   460.1 2948.85   485.6 2947.85
   649.7 2949.31   691.1 2953.72   708.2 2962.58   726.5 2966.74   782.9 2967.18
   962.1 2975.42   987.5 2977.53  1017.3 2977.97    1153 2985.88  1240.7 2991.19
#Mann= 5 ,-1,0
       0      .1       0     204     .06       0   359.5    .045       0
  429.51     .06       0    1153     .08       0
#XS Ineff= 2 , 0
             330 2959.96     448         2959.64
Permanent Ineff=
       F       F
Bank Sta=359.5,429.51
XS Rating Curve= 0 ,0
Exp/Cntr(USF)=0,0
Exp/Cntr=0.5,0.3

Type RM Length L Ch R = 1 ,44653   ,116.5,117.6,120.1
BEGIN DESCRIPTION:
structure xs 2
END DESCRIPTION:
XS GIS Cut Line= 6
2335820.60615989576032.0020668432335639.55360289576172.860595672
2335310.81442144576611.8647799382335235.39747058576744.200184266
2335204.09232117576825.3089804682335161.07451835577071.562251648
#Sta/Elev= 30
       0 3094.59    67.1 3062.46     107  3039.3   167.8 3001.57   177.9 2994.66
   190.8 2982.01   209.2 2962.91   213.4 2960.19   269.8 2958.43   288.4 2949.08
   295.1 2947.55   339.7 2946.11   369.7 2944.52   384.7 2943.05   417.8  2944.3
   432.1 2947.67   499.6 2948.27   514.9 2948.24   663.5 2950.17   734.5 2953.97
   751.4 2960.94   769.5 2965.91   839.4 2969.74   868.7 2970.78   948.4 2973.56
  1004.6 2977.82  1065.7 2984.93  1082.6 2989.69  1134.4 2999.16  1267.1 2993.85
#Mann= 11 ,-1,0
       0      .1       0   190.8     .06       0   339.7      .1       0
   369.7    .045       0   417.8     .06       0   499.6      .1       0
   514.9     .06       0   663.5      .1       0   751.4     .06       0
   839.4      .1       0   868.7     .06       0
#XS Ineff= 2 , 0
           356.4 2959.96   431.1         2959.64
Permanent Ineff=
       F       F
Bank Sta=369.7,417.8
XS Rating Curve= 0 ,0
Exp/Cntr=0.5,0.3

Type RM Length L Ch R = 1 ,44536   ,368.9,370.4,367.9
XS GIS Cut Line= 2
2335678.04404807575950.082867047  2335113.453986576644.962943449
#Sta/Elev= 30
       0 3066.84    37.7 3047.62    86.5 3020.02    91.8 3016.06   101.9 3006.36
   136.2 2982.59   145.7 2974.32   155.2 2964.72   159.9 2961.66   191.2 2960.76
   215.3  2958.7   220.5 2956.89   235.9 2947.55     244 2944.49   292.6 2945.31
   310.6  2944.3   324.8 2943.33   332.8 2942.29   358.2  2942.1   369.9 2943.49
   377.2 2946.18   418.7 2947.69   620.6 2947.69   700.2 2948.87   723.1 2951.19
   756.5 2959.96   776.8 2962.95   840.3 2970.27   884.7 2971.09   895.3 2974.01
#Mann= 5 ,-1,0
       0      .1       0     160     .06       0   310.6      .1       0
   324.8    .045       0   369.9      .1       0
Bank Sta=324.8,369.9
XS Rating Curve= 0 ,0
Exp/Cntr(USF)=0,0
Exp/Cntr=0.3,0.1

Type RM Length L Ch R = 1 ,44165   ,228.2,227.2,225.9
XS GIS Cut Line= 3
2335584.80421596575750.0080942822335349.53529811575829.821727304
2334764.06836811576590.143109967
#Sta/Elev= 30
       0 3083.15   122.8 3020.72   189.1 2992.58   199.2 2986.87   224.5 2967.69
   277.9 2963.25  314.72 2940.82   328.4 2939.01   351.6 2940.68   378.9 2941.48
   391.6  2945.4   474.8 2941.86   562.7 2942.76   606.1 2941.08   626.3 2945.27
   646.5 2943.88   681.8 2947.12     702 2943.09   729.3 2943.12   752.5 2940.25
   822.2 2946.62   862.2 2946.58   898.9 2943.86   934.2    2945   950.6 2949.24
   994.8 2969.48  1109.5 2982.35  1171.5 3000.17  1201.6 3013.14  1208.1 3013.92
#Mann= 6 ,-1,0
       0      .1       0     160     .06       0     220      .1       0
  314.72    .045       0   351.6      .1       0 1208.05     .06       0
#XS Ineff= 2 , 0
                           829.8         2953.07
Permanent Ineff=
       F       F
Bank Sta=314.72,351.6
XS Rating Curve= 0 ,0
Exp/Cntr=0.3,0.1