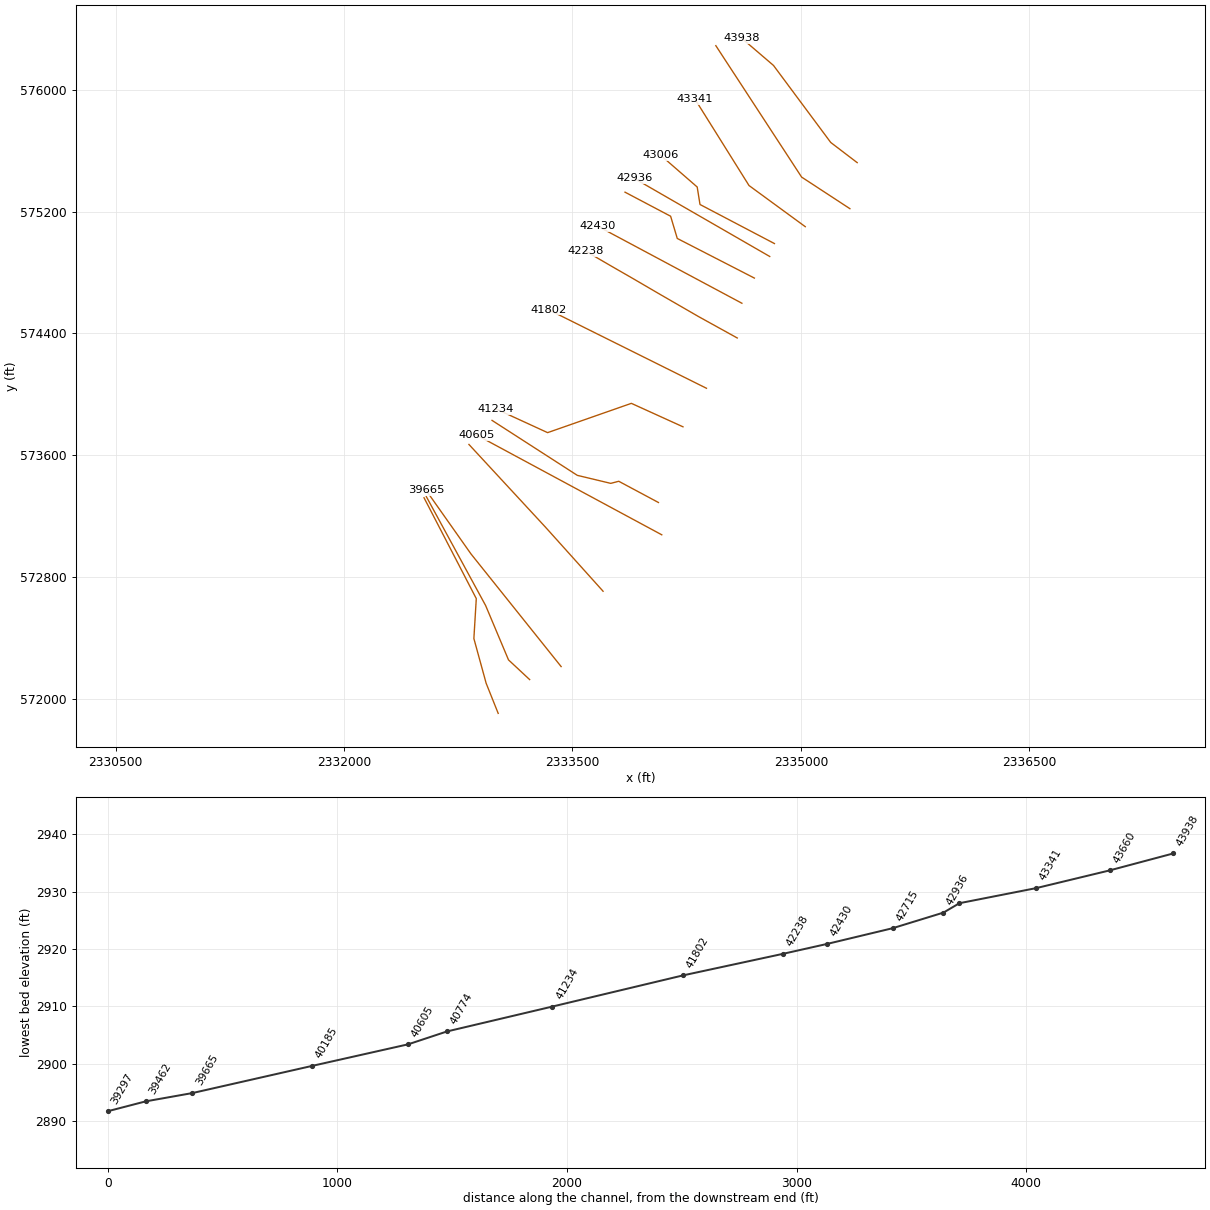
HEC-RAS study EFGRNBRRRV.prj: EFGRNBRRRV

--- EFGRNBRRRV.g01 (geometry) --- (continued)

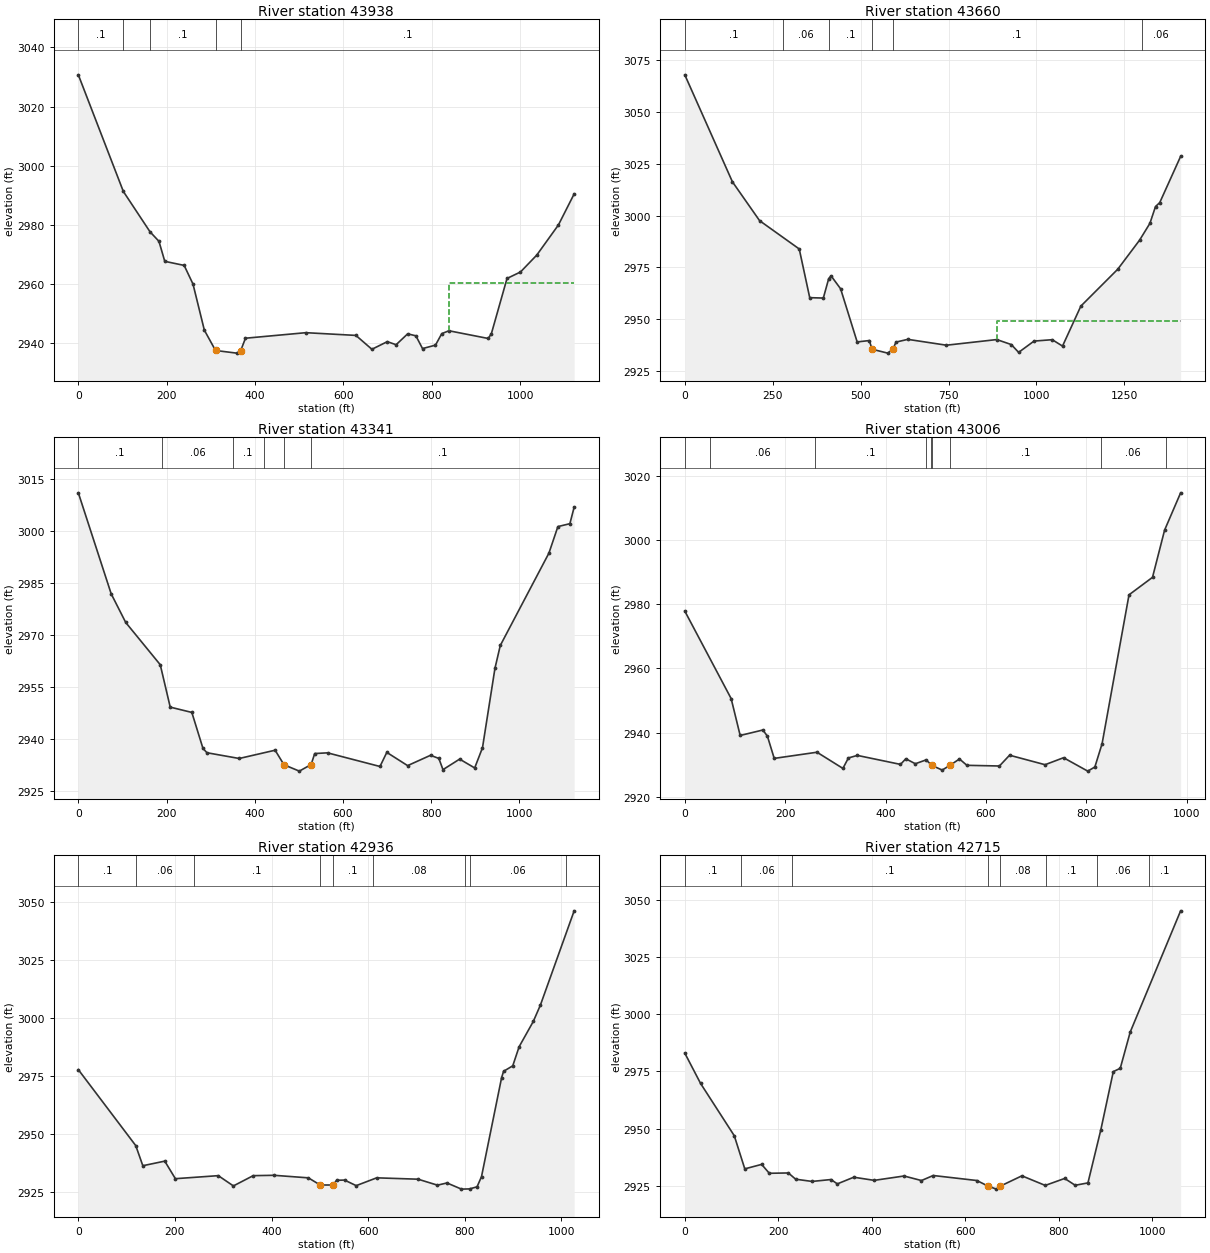
Type RM Length L Ch R = 1 ,43938   ,281.5,278.3,275.2
XS GIS Cut Line= 4
 2335369.2029026575522.4654555892335195.58870041575654.960504622
2334819.80532859576160.9545280862334611.92516545576339.137525062
#Sta/Elev= 30
       0 3030.74   101.9 2991.32   162.3 2977.68   182.5 2974.47   195.7  2967.7
   239.6 2966.32   259.6 2960.01   285.3 2944.43   310.62937.567   358.3 2936.67
   367.5 2937.49   378.4 2941.71   515.1 2943.58   628.4 2942.66   664.6 2937.97
   699.5 2940.55   719.4 2939.51   745.6 2943.19   764.2 2942.52   779.2 2938.21
   808.5 2939.37   822.8 2943.26     839 2944.23     928 2941.62   935.1 2943.25
   970.5 2961.91    1001  2964.1  1037.8  2969.8  1086.9    2980  1122.5 2990.49
#Mann= 5 ,-1,0
       0      .1       0   101.9     .06       0   162.3      .1       0
   310.6    .045       0   367.5      .1       0
#XS Ineff= 2 , 0
                          839.66         2960.25
Permanent Ineff=
       F       F
Bank Sta=310.6,367.5
XS Rating Curve= 0 ,0
Exp/Cntr(USF)=0,0
Exp/Cntr=0.3,0.1

Type RM Length L Ch R = 1 ,43660   ,315.4,318.8,317.8
XS GIS Cut Line= 3
2335321.39855917575219.9854239122335004.41902905575427.455396246
2334441.18304108576290.942246355
#Sta/Elev= 30
       0 3067.92   135.3 3016.35   212.7 2997.58   325.4 2983.93   355.2 2960.45
   393.9 2960.26   409.2 2969.65   415.9 2970.97     443 2964.73   490.1  2939.1
   524.8 2939.77  532.212935.588     577  2933.7   591.3 2935.54   600.6 2939.02
     634 2940.34   743.9 2937.52   887.1 2940.24   928.4 2937.83   949.2 2934.06
     993 2939.51  1044.7 2940.18    1074  2937.1  1126.1 2956.37    1231 2974.16
  1293.1 2988.18  1322.5  2996.3  1338.4  3004.4  1350.4 3006.28  1409.8 3028.59
#Mann= 6 ,-1,0
       0      .1       0     280     .06       0  408.84      .1       0
  532.21    .045       0   591.3      .1       0 1298.84     .06       0
#XS Ineff= 2 , 0
                          886.99         2949.35
Permanent Ineff=
       F       F
Bank Sta=532.21,591.3
XS Rating Curve= 0 ,0
Exp/Cntr=0.3,0.1

Type RM Length L Ch R = 1 ,43341   ,317.6,335,352.8
XS GIS Cut Line= 3
 2335028.3317262575101.6681149782334659.11182962575371.888625423
2334305.55825913575937.418996513
#Sta/Elev= 30
       0 3010.98    74.5 2981.82   107.5 2973.54   185.8 2961.34   208.4  2949.1
   257.4 2947.57   282.7 2937.17   291.7 2935.93   364.9 2934.27   446.3 2936.66
466.41652932.455   501.2 2930.62527.91612932.517   536.1  2935.7   565.1  2935.9
   684.1 2931.96   699.6 2936.03   746.8 2932.21   798.7 2935.19   817.6 2934.29
     827 2931.05   864.8 2934.09   898.9 2931.54   916.6 2937.37   944.9 2960.32
     957 2966.91  1067.3 2993.58  1087.6 3001.23  1114.8 3002.07  1124.5 3006.85
#Mann= 6 ,-1,0
       0      .1       0     190     .06       0     350      .1       0
     420     .07       0466.4165     .04       0527.9161      .1       0
Bank Sta=466.4165,527.9161
XS Rating Curve= 0 ,0
Exp/Cntr(USF)=0,0
Exp/Cntr=0.3,0.1

Type RM Length L Ch R = 1 ,43006   ,70.7,69.7,69.5
XS GIS Cut Line= 4
2334825.86495127574990.7376313242334337.20830331575247.420869611
2334318.75671774575362.3239252092334077.91915737575571.830477357
#Sta/Elev= 30
       0 2977.86    92.3  2950.6   110.3 2939.09   155.5  2940.8   164.6 2938.85
   178.1 2931.95   263.3 2933.87   314.9 2928.83   325.9 2932.09   343.7 2932.88
   429.6 2930.08   440.2 2931.83   459.2 2930.28   480.8 2931.49   491.8 2929.79
   512.7 2928.31  528.29  2929.8   547.1 2931.77   561.9 2929.79   626.7 2929.58
   646.9 2932.94   717.6 2929.98   754.4 2932.16   802.6 2927.98   816.8 2929.27
   831.2 2936.55   884.8 2982.93   931.6 2988.38   955.7 3003.11   987.6 3014.72
#Mann= 9 ,-1,0
       0      .1       0      50     .06       0     260      .1       0
     480     .08       0     490      .1       0   491.8     .04       0
  528.29      .1       0  828.35     .06       0  958.35      .1       0
Bank Sta=491.8,528.29
XS Rating Curve= 0 ,0
Exp/Cntr=0.3,0.1

Type RM Length L Ch R = 1 ,42936   ,233.6,221,196.7
XS GIS Cut Line= 2
2334795.14920505574905.7623294292333906.03778218575418.599473663
#Sta/Elev= 30
       0 2977.85   118.9 2945.09   133.5 2936.43   178.9 2938.41   200.9 2930.84
   289.7 2932.15     321 2927.72     362 2932.15   405.2  2932.3   476.2  2931.2
   500.7 2928.12  527.05 2928.12   534.7 2930.16   551.2 2930.24   575.2 2927.84
   617.6 2931.21   703.3 2930.62   743.4 2928.05   763.2    2929   793.1 2926.34
     810 2926.44   825.4 2927.34   834.6 2931.72   876.2 2974.39   880.3 2977.14
   899.3  2979.5   912.5 2987.74   941.8 2998.63   956.5 3005.67  1026.4 3046.32
#Mann= 9 ,-1,0
       0      .1       0     120     .06       0     240      .1       0
   500.7     .04       0  527.05      .1       0     610     .08       0
     800      .1       0     810     .06       0    1010      .1       0
Bank Sta=500.7,527.05
XS Rating Curve= 0 ,0
Exp/Cntr(USF)=0,0
Exp/Cntr=0.3,0.1

Type RM Length L Ch R = 1 ,42715   ,207.3,285.1,312.3
XS GIS Cut Line= 4
2334694.26305966574763.9356371212334187.91820188575024.324425894
2334144.30536325575170.2596935892333844.84068862575328.348061845
#Sta/Elev= 30
       0 2983.01    33.8 2969.75   105.8 2946.94   128.3 2932.47   164.3 2934.42
   180.7 2930.54   221.4 2930.68   237.1 2927.95   272.2 2926.98   312.7 2927.81
   326.2 2925.91   361.3 2928.82   405.1 2927.45   468.8 2929.35   506.1 2927.37
   531.2 2929.57   624.5 2927.38  647.72 2925.02   666.3 2923.62   674.6 2924.92
   720.9 2929.43   770.8 2925.24   812.3 2928.28   834.9  2925.3   862.1 2926.34
   889.7 2949.55   916.3 2974.92   931.2 2976.38   952.5  2992.2  1060.3 3045.14
#Mann= 8 ,-1,0
       0      .1       0     120     .06       0     230      .1       0
  647.72     .04       0   674.6     .08       0  771.69      .1       0
  881.69     .06       0  991.69      .1       0
Bank Sta=647.72,674.6
XS Rating Curve= 0 ,0
Exp/Cntr(USF)=0,0
Exp/Cntr=0.3,0.1

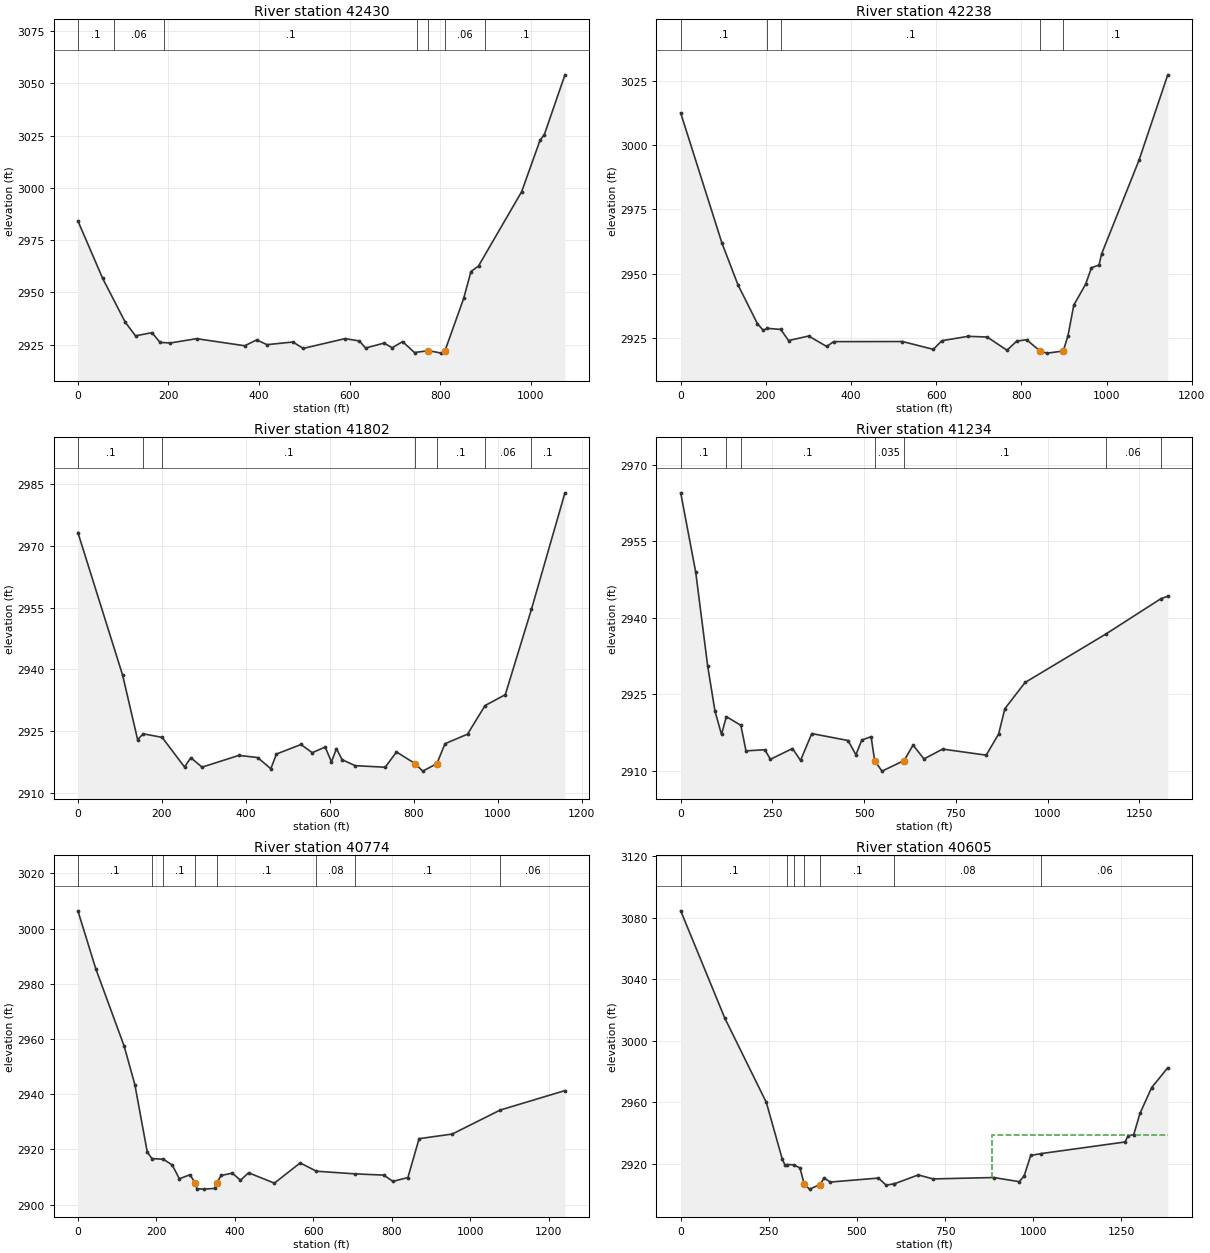
Type RM Length L Ch R = 1 ,42430   ,196.8,192.3,191.2
XS GIS Cut Line= 2
 2334612.3872895574598.5294969212333663.81650595575105.863018237
#Sta/Elev= 30
       0 2984.17    54.7 2956.66   104.6 2935.68   127.3 2929.16   163.5 2930.67
   181.7 2925.99   204.4 2925.75   262.2  2927.8   368.6  2924.4   394.9 2927.22
   417.6 2924.93     475 2926.21   497.5 2923.13   589.9 2927.82   621.7 2926.72
   635.3 2923.31   676.1 2925.68   694.3 2923.43     717  2926.4   743.5 2921.16
   774.2 2922.07   802.9 2920.88   810.82922.042   852.2 2947.17   868.1 2959.92
   884.8 2962.57   980.1 2998.15  1020.9 3022.85    1030 3025.35  1075.7 3054.07
#Mann= 7 ,-1,0
       0      .1       0      80     .06       0     190      .1       0
     750     .06       0   774.2     .04       0   810.8     .06       0
     900      .1       0
Bank Sta=774.2,810.8
XS Rating Curve= 0 ,0
Exp/Cntr(USF)=0,0
Exp/Cntr=0.3,0.1

Type RM Length L Ch R = 1 ,42238   ,430,436.3,438.2
BEGIN DESCRIPTION:
start EFG detailed reach
channel from lidar:
lidar invert = 2919.15
effective invert = 2922.10
END DESCRIPTION:
XS GIS Cut Line= 6
2334581.74421319 574370.383950842334326.88907159 574511.41944263
2334069.08130057574660.3305175392333890.12233778 574764.86713683
2333760.47983663574839.3398068182333589.42809252574938.919810783
#Sta/Elev= 30
       0 3012.44    96.6 2962.03   134.4 2945.71   180.1 2930.61   193.8 2927.99
   202.9 2928.78   234.9 2928.37   253.2 2924.04   300.4 2925.79   342.8 2921.74
   359.1 2923.62   520.8 2923.66   593.2 2920.61   613.2 2923.98   675.1 2925.68
   719.8 2925.41   766.1 2920.27   789.2 2923.83   812.3 2924.35   844.8 2919.84
   861.1 2919.15   898.2 2919.97   909.3 2925.84   923.1 2937.81   950.7 2945.89
   964.6 2952.34   982.4 2953.39   988.3 2957.68  1076.1 2994.07  1143.7 3027.29
#Mann= 5 ,-1,0
       0      .1       0   202.9    .016       0   234.9      .1       0
   844.8    .035       0   898.2      .1       0
Bank Sta=844.8,898.2
XS Rating Curve= 0 ,0
Exp/Cntr(USF)=0,0
Exp/Cntr=0.3,0.1

Type RM Length L Ch R = 1 ,41802   ,498.9,568,599
BEGIN DESCRIPTION:
channel from lidar:
lidar invert = 2915.38
effective invert = 2916.7
END DESCRIPTION:
XS GIS Cut Line= 2
2334379.59152497574039.9487972612333340.95824454574557.113584782
#Sta/Elev= 30
       0 2973.18   106.6 2938.61   142.3 2923.02   155.7 2924.42   200.7 2923.56
     254 2916.38     269 2918.63   295.8 2916.35   383.6 2919.19   428.3 2918.67
   459.6 2915.96     473 2919.52   531.5 2921.83   558.3 2919.85   589.2 2921.22
     604 2917.61     616 2920.82   629.4 2918.15   660.7  2916.7   732.2 2916.33
     759 2920.03   803.7 2917.18   821.5 2915.38   855.3  2917.2   874.5 2922.02
   928.2 2924.33     970 2931.26  1018.2  2933.9  1080.4 2954.55  1160.3 2982.79
#Mann= 7 ,-1,0
       0      .1       0   155.7    .016       0   200.7      .1       0
   803.7    .035       0   855.3      .1       0     970     .06       0
  1080.4      .1       0
Bank Sta=803.7,855.3
XS Rating Curve= 0 ,0
Exp/Cntr(USF)=0,0
Exp/Cntr=0.3,0.1

Type RM Length L Ch R = 1 ,41234   ,474.3,459.7,392.9
BEGIN DESCRIPTION:
channel burned 0.3' per effective xs:
effective invert = 2909.95
lidar invert = 2910.25
END DESCRIPTION:
XS GIS Cut Line= 4
2334225.36708157573786.734020648 2333886.4861504573940.845063625
2333336.64665693573748.4075316042332998.30055045573903.888359115
#Sta/Elev= 30
       0 2964.48    40.9 2948.94    73.5 2930.53    93.4 2921.71   111.2 2917.13
   124.3 2920.63   163.9 2918.93   177.9 2913.92   229.3 2914.14   244.4 2912.27
   304.5 2914.38   326.5 2912.05   357.2 2917.31     456 2915.95   477.4 2913.16
   493.4 2916.04   518.8  2916.7528.59252911.985   548.5 2909.95   608.6 2912.02
   633.2 2915.05   662.9 2912.34   713.8 2914.27   832.4 2913.08   866.3 2917.22
   883.3 2922.18   938.4 2927.32  1157.8 2936.78  1308.6 2943.74  1327.2 2944.22
#Mann= 7 ,-1,0
       0      .1       0   124.3    .016       0   163.9      .1       0
528.5925    .035       0   608.6      .1       0  1157.8     .06       0
  1308.6     .05       0
Bank Sta=528.5925,608.6
XS Rating Curve= 0 ,0
Exp/Cntr=0.3,0.1

Type RM Length L Ch R = 1 ,40774   ,185,168.7,92.8
BEGIN DESCRIPTION:
channel burned 0.78' per effective xs:
effective invert = 2905.60
lidar invert = 2906.38
END DESCRIPTION:
XS GIS Cut Line= 5
2334064.27650222573289.4236271392333803.69647357573428.856800365
2333751.12330989573415.1420620142333531.68749629 573467.71522569
2332971.66901367573828.870002241
#Sta/Elev= 30
       0 3006.43    45.5 2985.49   118.1 2957.36   145.3 2943.44     177 2918.95
     189 2916.67   217.9 2916.42   240.6 2914.34   258.7 2909.35   285.9 2910.83
   299.2 2907.76   303.3 2905.76   321.1  2905.6   348.8 2905.87     354  2907.8
   365.2 2910.54   393.8  2911.4   414.6 2908.81   435.2 2911.52     501 2907.77
   566.8  2915.1   608.1  2912.1   706.4 2911.13   779.6 2910.68   803.4 2908.41
   841.5  2909.8     870 2923.88   954.6 2925.56  1076.8 2934.25  1241.9  2941.3
#Mann= 8 ,-1,0
       0      .1       0     189    .016       0   217.9      .1       0
   299.2    .035       0     354      .1       0   608.1     .08       0
   706.4      .1       0  1076.8     .06       0
Bank Sta=299.2,354
XS Rating Curve= 0 ,0
Exp/Cntr(USF)=0,0
Exp/Cntr=0.3,0.1

Type RM Length L Ch R = 1 ,40605   ,429.2,419.7,364.6
BEGIN DESCRIPTION:
channel from lidar:
lidar invert = 2903.36
interpolated invert = 2904.31
END DESCRIPTION:
XS GIS Cut Line= 2
2334086.02734338573077.2355714242332869.56166709573733.244516391
#Sta/Elev= 30
       0 3084.49   124.8 3014.83     243 2959.77   288.4 2922.76   296.6 2918.75
   302.5 2919.36   320.1 2919.19   338.4 2917.17  350.75 2906.41   365.7 2903.36
  395.48 2906.34   406.6 2910.64   424.7 2907.97   561.1 2910.56   582.9 2905.97
   606.6 2906.84   606.6 2906.85   674.1 2912.61   716.2    2910   888.3 2910.92
   960.9  2908.2   974.6 2912.02   993.3 2925.28  1022.9 2926.49  1260.9 2934.05
    1270 2938.19  1285.6 2938.88  1303.3 2952.66  1336.3 2969.42  1382.1 2982.36
#Mann= 7 ,-1,0
       0      .1       0   302.5    .016       0   320.1      .1       0
  350.75    .035       0  395.48      .1       0   606.6     .08       0
  1022.9     .06       0
#XS Ineff= 2 , 0
                          884.34         2938.54
Permanent Ineff=
       F       F
Bank Sta=350.75,395.48
XS Rating Curve= 0 ,0
Exp/Cntr=0.3,0.1

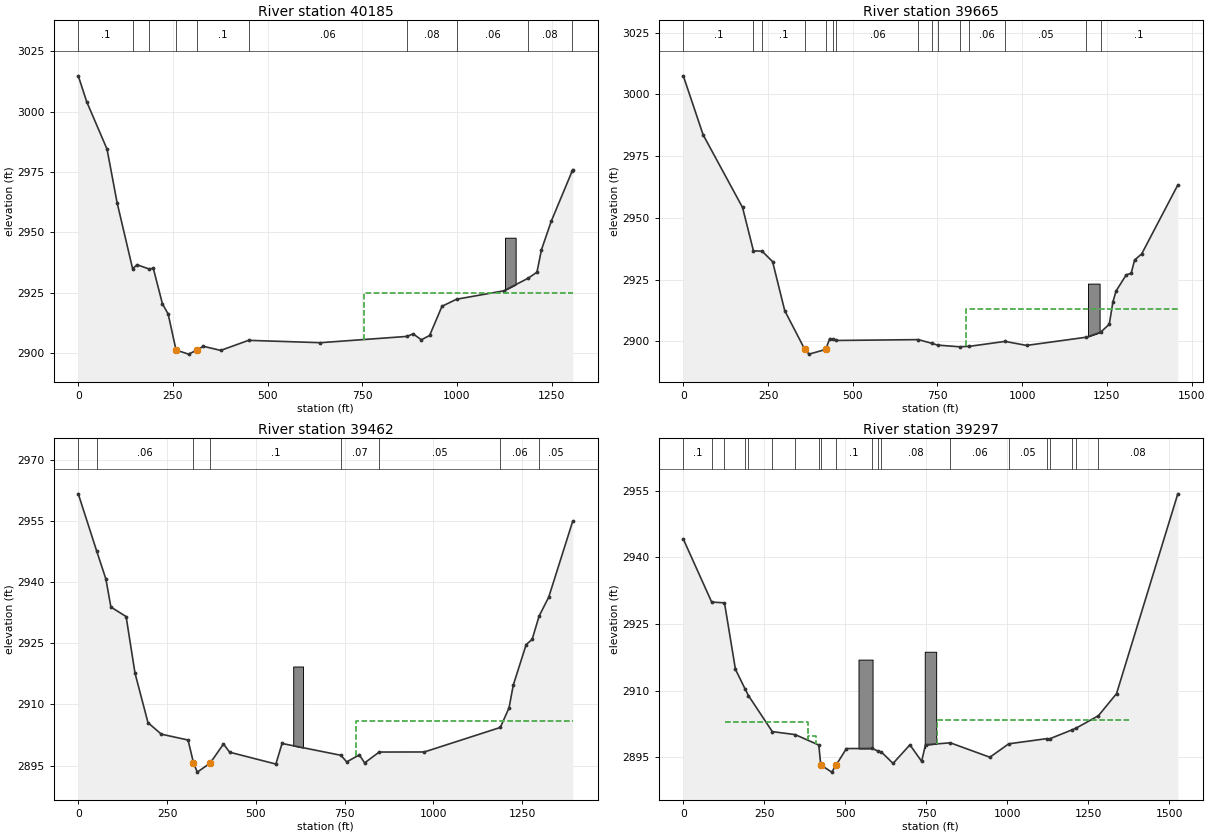
Type RM Length L Ch R = 1 ,40185   ,523.8,520.4,515.2
BEGIN DESCRIPTION:
channel from lidar:
lidar invert = 2899.58
effective invert = 2901.1
END DESCRIPTION:
Node Name=U
XS GIS Cut Line= 3
2333700.70085384572706.4204306932333323.57761041573126.230823382
2332820.03771887 573670.79024414
#Sta/Elev= 30
       0 3014.85    22.2 3004.15      76 2984.47   102.5 2962.35   143.5 2934.97
   155.3  2936.6   186.4 2934.88   198.3 2935.06   222.3  2920.4   237.4 2916.19
   258.2 2901.27   291.2 2899.58   313.9 2901.27     330 2902.84   376.2 2901.12
   449.7 2905.29   639.6 2904.32     868 2906.92   884.3 2907.96   906.1 2905.53
   927.9  2907.3   960.6 2919.41   999.1 2922.32  1123.2 2925.78    1188    2931
  1211.4 2933.53  1223.3 2942.83  1249.3 2954.69  1304.8 2975.57    1306 2975.98
#Mann= 10 ,-1,0
       0      .1       0   143.5    .016       0   186.4      .1       0
   258.2    .035       0   313.9      .1       0   449.7     .06       0
     868     .08       0   999.1     .06       0    1188     .08       0
  1304.8     .05       0
#XS Ineff= 2 , 0
                          754.22         2924.74
Permanent Ineff=
       F       F
#Block Obstruct= 1 ,-1
 1126.98 1155.07  2947.8
Bank Sta=258.2,313.9
XS Rating Curve= 0 ,0
Exp/Cntr(USF)=0,0
Exp/Cntr=0.3,0.1

Type RM Length L Ch R = 1 ,39665   ,211.1,203.4,126.7
BEGIN DESCRIPTION:
channel from lidar:
lidar invert = 2894.85
effective invert = 2895.70
END DESCRIPTION:
XS GIS Cut Line= 3
2333425.32687377572211.409556781 2332833.7967125572951.025073422
2332538.71533983573369.640334276
#Sta/Elev= 30
       0 3007.53    58.6 2983.63   174.8 2954.23     207 2936.67   232.6 2936.53
   263.5 2932.29   299.3 2912.46   357.8 2896.95     371 2894.85   420.4 2896.75
   431.8  2901.1   442.8 2900.95   451.7 2900.38   693.6 2900.72   734.7 2899.18
   750.1 2898.51   815.2 2897.82   844.5 2898.01   949.3    2900  1012.9 2898.38
  1189.5  2901.7  1231.2 2903.72  1256.9 2906.93  1267.8 2916.07    1277  2920.4
    1307 2926.96  1321.6 2927.57  1331.7 2932.97  1352.6 2935.43  1459.2 2963.34
#Mann= 15 ,-1,0
       0      .1       0     207    .016       0   232.6      .1       0
   357.8    .035       0   420.4      .1       0   442.8    .016       0
   451.7     .06       0   693.6     .05       0   734.7    .016       0
   750.1     .08       0   815.2     .07       0   844.5     .06       0
   949.3     .05       0  1189.5     .06       0  1231.2      .1       0
#XS Ineff= 2 , 0
                          834.42          2913.2
Permanent Ineff=
       F       F
#Block Obstruct= 1 ,-1
 1194.04 1228.41  2923.4
Bank Sta=357.8,420.4
XS Rating Curve= 0 ,0
Exp/Cntr(USF)=0,0
Exp/Cntr=0.3,0.1

Type RM Length L Ch R = 1 ,39462   ,168.8,165,33
BEGIN DESCRIPTION:
xs 4
channel from lidar:
lidar invert = 2893.4
interpolated invert = 2894.39
END DESCRIPTION:
XS GIS Cut Line= 4
2333218.69661648572125.8237206622333079.81696232572255.234307485
2332929.89006295572611.902510193 2332540.0801246573328.395271386
#Sta/Elev= 30
       0 2961.59    51.9 2947.56    77.7 2940.73    91.9 2933.85   134.7 2931.52
   159.8 2917.64   196.3 2905.52   233.8  2902.7   309.1 2901.27  324.34 2895.71
   335.1  2893.4   371.3  2895.6   408.9  2900.3   426.3 2898.28   556.4 2895.38
   573.8 2900.42   739.3 2897.53   755.9 2895.91   791.3 2897.63   806.3 2895.66
   847.3 2898.32   974.3 2898.34  1188.4 2904.35    1213 2909.18  1224.8 2914.72
  1261.2 2924.66  1277.9 2925.91  1297.7 2931.67  1324.7 2936.29  1392.4 2954.93
#Mann= 8 ,-1,0
       0      .1       0    51.9     .06       0  324.34    .035       0
   371.3      .1       0   739.3     .07       0   847.3     .05       0
  1188.4     .06       0  1297.7     .05       0
#XS Ineff= 2 , 0
                          783.13         2905.83
Permanent Ineff=
       F       F
#Block Obstruct= 1 ,-1
   605.2  632.92 2919.28
Bank Sta=324.34,371.3
XS Rating Curve= 0 ,0
Exp/Cntr(USF)=0,0
Exp/Cntr=0.5,0.3

Type RM Length L Ch R = 1 ,39297   ,49.7,50.3,44.9
BEGIN DESCRIPTION:
structure xs 3
channel burned per surveyed cross section data, banks placed persurvey data
END DESCRIPTION:
XS GIS Cut Line= 5
2333012.14985882571903.8379502762332933.09645121572101.471469285
2332852.46197546 572395.550145572332868.27265698572658.007458814
2332525.18086798573320.475014531
#Sta/Elev= 30
       0  2944.1    87.6 2929.92   127.2 2929.75     161  2914.8     191 2910.35
     201 2908.91   274.8 2900.79   345.3 2900.12   418.4 2897.77  424.36  2893.3
  458.33 2891.68  472.02  2893.3   503.7 2896.98   583.5    2897   599.6 2896.46
   611.6  2896.2   647.6 2893.64   699.7 2897.82   735.8 2894.11   747.8 2897.83
   824.4 2898.27   946.5 2895.03    1005 2898.05  1121.5  2899.2  1131.2 2899.17
  1201.6 2901.23  1212.2 2901.55  1281.7 2904.37  1337.6 2909.33  1526.8 2954.26
#Mann= 20 ,-1,0
       0      .1       0    87.6    .016       0   127.2      .1       0
     191    .016       0     201      .1       0   274.8     .07       0
   345.3    .016       0   418.4     .07       0  424.36    .035       0
  472.02      .1       0   583.5     .08       0   599.6    .016       0
   611.6     .08       0   824.4     .06       0    1005     .05       0
  1121.5    .016       0  1131.2     .05       0  1201.6    .016       0
  1212.2     .05       0  1281.7     .08       0
#XS Ineff= 4 ,-1
   129.8     384 2903.02     384  409.55 2899.84     507     700 2896.73
  784.05 1377.352903.444
Permanent Ineff=
       F       F       F       F
#Block Obstruct= 2 ,-1
  540.91  584.36 2916.98   745.4  780.72 2918.75
Bank Sta=424.36,472.02
XS Rating Curve= 0 ,0
Exp/Cntr(USF)=0,0
Exp/Cntr=0.5,0.3