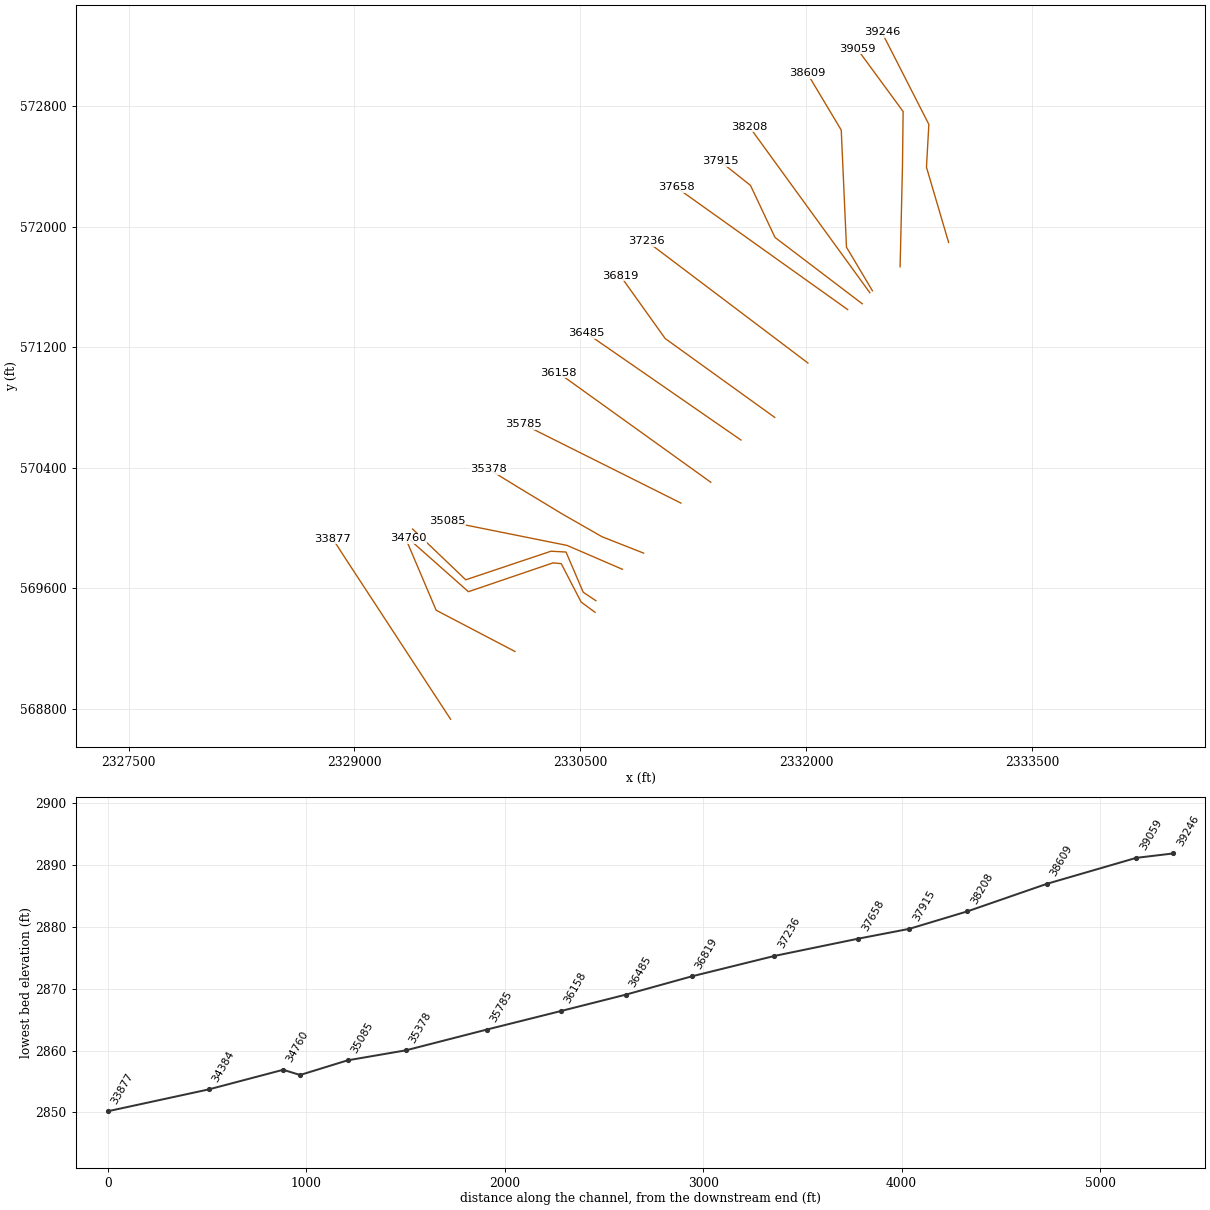
HEC-RAS study EFGRNBRRRV.prj: EFGRNBRRRV

--- EFGRNBRRRV.g01 (geometry) --- (continued)

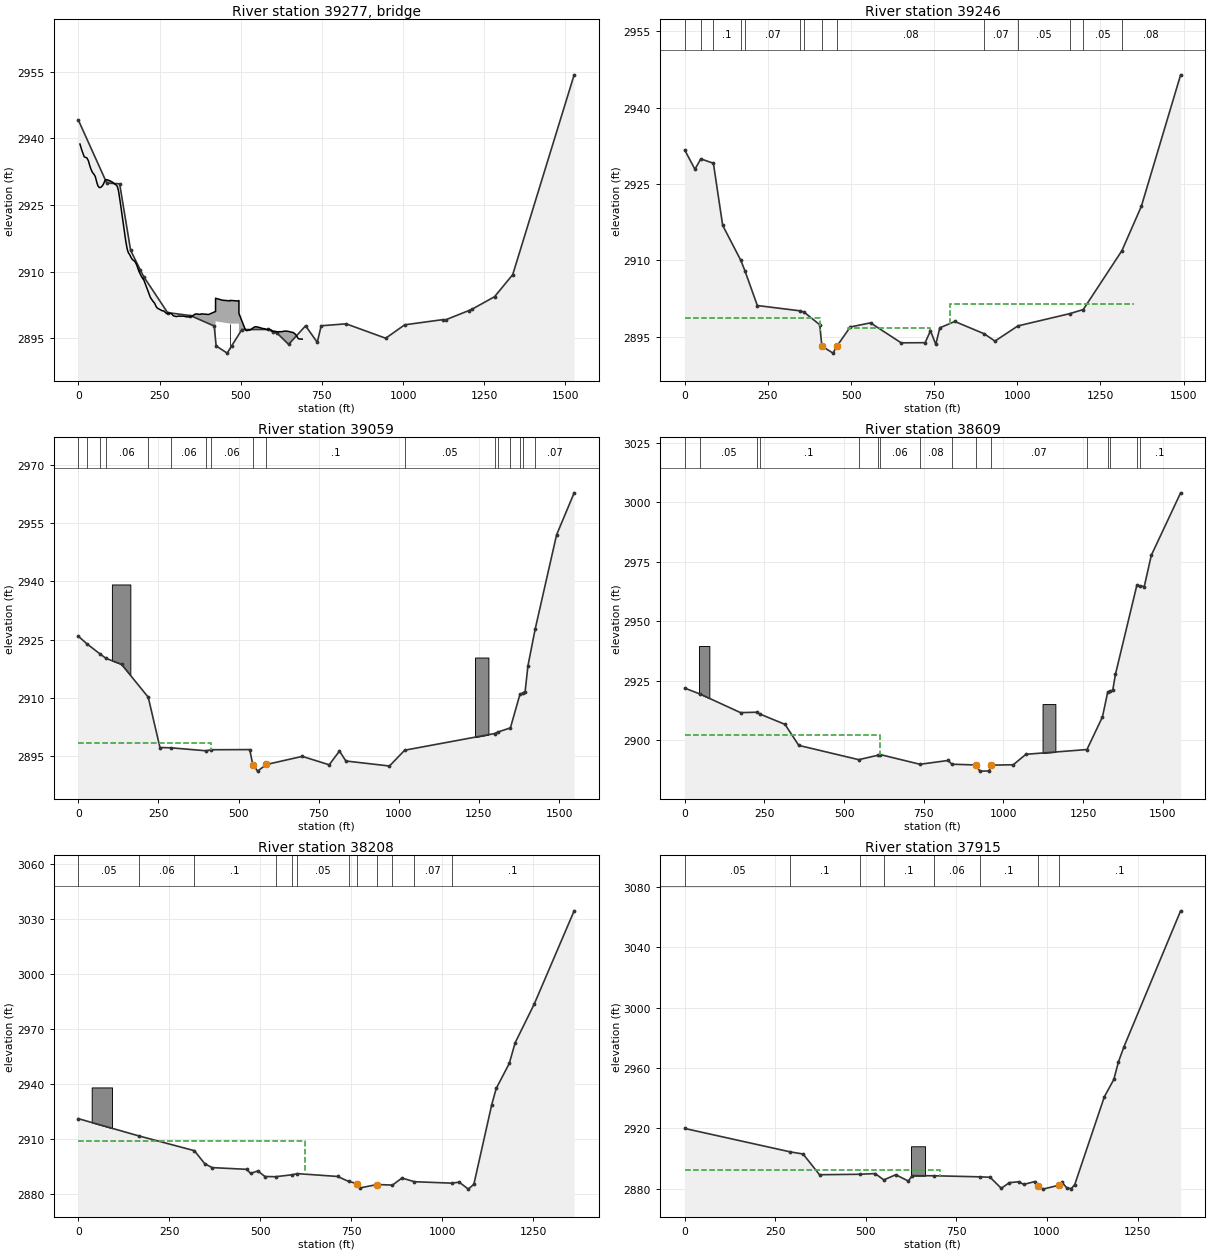
Type RM Length L Ch R = 3 ,39277   ,,,
BEGIN DESCRIPTION:
Bridge 54075EFG060
JV notes: road deck updated per surveyed XS data points
channel burned per surveyed cross section points
rail coded based on information provided in survey viewer
photos show wooden railing that is not very obstructive to flow - rail added along the opening of the structure
structure opening based on survey data, photos, and aerial imagery
surveyed inverts are 1' below inverts from lidar:
 surveyed invert US is 2891.85
 surveyed invert DS is 2891.94
END DESCRIPTION:
Bridge Culvert--1,0,-1,-1, 0
Deck Dist Width WeirC Skew NumUp NumDn MinLoCord MaxHiCord MaxSubmerge Is_Ogee
13,12,2.6,0, 197, 166, , , 0.98, 0, 0,0,,
       5     7.5     9.6    10.6    13.8    18.1    22.4    25.4    26.6    29.4
    30.9    32.5    33.9    35.1    38.8    41.9    43.6    48.2    51.3    52.1
    56.4    57.5    60.6    63.8    64.9    66.9    69.1    72.6    76.3    77.6
    81.9    82.5    84.4    85.7    88.8    94.6   103.1   104.4   111.6   115.9
   116.9   119.9   120.1   123.2   124.4   126.3   128.6   129.4   133.6   135.7
   137.1   141.4   141.9   145.6   148.2   149.9   151.3   153.5   154.4   157.6
   158.4   160.7   163.8   166.9   170.1   171.1   175.4   179.5     180   182.6
   185.7   188.1     192   192.4   195.1   196.6     200   201.3   202.6   207.6
   210.7   213.8     217     222   223.5   225.1   230.3   233.2   234.5   238.6
   239.7   242.8   246.2   251.1   252.7   255.3   255.9   259.9   262.4   263.6
   267.7   271.9   275.4     276   280.2   284.3   288.5   292.7   296.8   298.1
   301.3   306.1   307.8   309.3   313.4   317.3   321.7   323.5   330.5   334.2
   335.1   342.5   346.6   350.8     355   359.1   362.9   367.5   369.8   372.6
   376.3   378.8  400.95  422.49  422.55  422.55  444.02  466.99  467.05  491.09
  494.55  494.55  512.85   517.1   522.4   525.1   529.1   533.7   537.1   542.2
   545.2   549.2     555   561.2   565.2   573.2     578   580.5   581.8   585.2
   585.6   589.1   593.3     597   600.7   601.8   604.5   606.1   608.3   610.3
   613.3   615.9   617.3   625.3   629.3   633.3   635.9   637.3   641.3   642.4
   644.4   646.2   648.6   653.7   657.1   661.4   665.1   665.7   668.9   669.9
   672.7   674.2   676.4   677.4   680.2   686.9   689.4
 2938.69 2938.07 2937.59 2937.34 2936.68 2935.84 2935.67 2935.62 2935.55 2935.14
 2934.94 2934.54 2934.16 2933.87 2933.06 2932.53 2932.29  2931.9 2931.53  2931.4
 2930.14 2929.92 2929.26 2928.97  2928.9 2928.92 2928.96 2929.18 2929.55 2929.75
 2930.47 2930.55 2930.66  2930.7 2930.65 2930.52 2930.23 2930.16 2929.73 2929.53
 2929.46 2929.21 2929.17 2928.31 2927.86 2926.99 2925.85 2925.41 2923.28 2922.17
 2921.41 2919.15 2918.86 2917.07 2915.94 2915.29 2914.86 2914.41  2914.2 2913.86
 2913.79 2913.43 2913.01 2912.69 2912.56  2912.5 2912.16 2911.57 2911.45  2910.9
 2910.27 2909.83 2909.24 2909.17 2908.81 2908.64 2908.31 2908.16 2907.96 2906.99
 2906.45 2905.85 2905.21 2904.18 2904.02 2903.81 2903.28 2903.04 2902.95 2902.27
 2902.14 2901.83 2901.68  2901.5 2901.42 2901.32 2901.28 2901.18 2901.18 2901.15
 2900.85 2900.58 2900.62 2900.64 2900.64 2900.62 2900.43 2900.07 2900.01 2899.96
 2899.91 2899.96 2900.01 2900.02 2899.97    2900 2900.01 2899.99 2899.88 2899.83
 2899.84 2899.84 2899.94    2900 2900.24 2900.43  2900.5 2900.47 2900.43  2900.4
 2900.41 2900.51 2900.37 2901.04 2901.12 2904.02 2903.58 2903.43 2903.54 2903.41
 2903.51 2900.61 2897.21 2896.73 2896.79 2896.81 2896.89 2897.11 2897.31 2897.54
 2897.62 2897.59  2897.5 2897.37 2897.26 2897.16 2897.02 2897.01 2896.99    2897
 2896.99 2897.01 2896.91  2896.7 2896.59 2896.57 2896.61 2896.57 2896.55 2896.49
 2896.45 2896.47  2896.5  2896.5 2896.53 2896.62 2896.63 2896.65 2896.64 2896.61
 2896.59 2896.55 2896.54 2896.43 2896.39 2896.31 2896.12  2896.1 2895.85 2895.79
 2895.46 2895.33 2895.03 2894.93 2894.87 2894.82 2894.82
                                                                                
                                                                                
                                                                                
                                                                                
                                                                                
                                                                                
                                                                                
                                                                                
                                                                                
                                                                                
                                                                                
                                                                                
                                                                                
                                 2898.84 2898.842898.5892898.321 2898.32 2898.32
 2898.32 2898.32
                                                                                
                                                                                
                                                                                
                                                                                
                                                        
    -5.5      -3     -.9      .1     3.3     7.6    11.9    14.9    16.1    18.9
    20.4      22    23.4    24.6    28.3    31.4    33.1    37.7    40.8    41.6
    45.9      47    50.1    53.3    54.4    56.4    58.6    62.1    65.8    67.1
    71.4      72    73.9    75.2    78.3    84.1    92.6    93.9   101.1   105.4
   106.4   109.4   109.6   112.7   113.9   115.8   118.1   118.9   123.1   125.2
   126.6   130.9   131.4   135.1   137.7   139.4   140.8     143   143.9   147.1
   147.9   150.2   153.3   156.4   159.6   160.6   164.9     169   169.5   172.1
   175.2   177.6   181.5   181.9   184.6   186.1   189.5   190.8   192.1   197.1
   200.2   203.3   206.5   211.5     213   214.6   219.8   222.7     224   228.1
   229.2   232.3   235.7   240.6   242.2   244.8   245.4   249.4   251.9   253.1
   257.2   261.4   264.9   265.5   269.7   273.8     278   282.2   286.3   287.6
   290.8   295.6   297.3   298.8   302.9   306.8   311.2     313     320   323.7
   324.6     332   336.1   340.3   344.5   348.6   352.4     357   359.3   362.1
   365.8   368.3  390.45  411.99  412.05  412.05  433.52  456.49  456.55  480.59
  484.05  484.05  502.35   506.6   511.9   514.6   518.6   523.2   526.6   531.7
   534.7   538.7   544.5   550.7   554.7   562.7   567.5     570   571.3   574.7
   575.1   578.6   582.8   586.5   590.2   591.3
 2938.69 2938.07 2937.59 2937.34 2936.68 2935.84 2935.67 2935.62 2935.55 2935.14
 2934.94 2934.54 2934.16 2933.87 2933.06 2932.53 2932.29  2931.9 2931.53  2931.4
 2930.14 2929.92 2929.26 2928.97  2928.9 2928.92 2928.96 2929.18 2929.55 2929.75
 2930.47 2930.55 2930.66  2930.7 2930.65 2930.52 2930.23 2930.16 2929.73 2929.53
 2929.46 2929.21 2929.17 2928.31 2927.86 2926.99 2925.85 2925.41 2923.28 2922.17
 2921.41 2919.15 2918.86 2917.07 2915.94 2915.29 2914.86 2914.41  2914.2 2913.86
 2913.79 2913.43 2913.01 2912.69 2912.56  2912.5 2912.16 2911.57 2911.45  2910.9
 2910.27 2909.83 2909.24 2909.17 2908.81 2908.64 2908.31 2908.16 2907.96 2906.99
 2906.45 2905.85 2905.21 2904.18 2904.02 2903.81 2903.28 2903.04 2902.95 2902.27
 2902.14 2901.83 2901.68  2901.5 2901.42 2901.32 2901.28 2901.18 2901.18 2901.15
 2900.85 2900.58 2900.62 2900.64 2900.64 2900.62 2900.43 2900.07 2900.01 2899.96
 2899.91 2899.96 2900.01 2900.02 2899.97    2900 2900.01 2899.99 2899.88 2899.83
 2899.84 2899.84 2899.94    2900 2900.24 2900.43  2900.5 2900.47 2900.43  2900.4
 2900.41 2900.51 2900.37 2901.04 2901.12 2904.02 2903.58 2903.43 2903.54 2903.41
 2903.51 2900.61 2897.21 2896.73 2896.79 2896.81 2896.89 2897.11 2897.31 2897.54
 2897.62 2897.59  2897.5 2897.37 2897.26 2897.16 2897.02 2897.01 2896.99    2897
 2896.99 2897.01 2896.91  2896.7 2896.59 2896.57
                                                                                
                                                                                
                                                                                
                                                                                
                                                                                
                                                                                
                                                                                
                                                                                
                                                                                
                                                                                
                                                                                
                                                                                
                                                                                
                                 2898.84 2898.842898.5892898.321 2898.32 2898.32
 2898.32 2898.32
                                                                                
                                                
Pier Skew, UpSta & Num, DnSta & Num=  ,467.05, 2 ,456.55, 2 , 0 , 0 , 0 ,,
       2       2
       0  2898.5
       2       2
       0  2898.5
BR Coef=-1 ,-1 , 0 ,, 0 ,,,0.8,0,2,0,
WSPro=,,,, 1 ,,,, 0 ,,,, 0 ,,,,-1 ,-1 ,-1 , 0 , 0 , 0 , 0 , 0
BR U #Sta/Elev= 30
       0  2944.1    87.6 2929.92   127.2 2929.75     161  2914.8     191 2910.35
     201 2908.91   274.8 2900.79   345.3 2900.12   418.4 2897.77  424.36  2893.3
  458.33 2891.68  472.02  2893.3   503.7 2896.98   583.5    2897   599.6 2896.46
   611.6  2896.2   647.6 2893.64   699.7 2897.82   735.8 2894.11   747.8 2897.83
   824.4 2898.27   946.5 2895.03    1005 2898.05  1121.5  2899.2  1131.2 2899.17
  1201.6 2901.23  1212.2 2901.55  1281.7 2904.37  1337.6 2909.33  1526.8 2954.26
BR U #Mann= 20
       0      .1    87.6    .016   127.2      .1     191    .016     201     .01
   274.8     .07   345.3    .016   418.4     .07  424.36     .03  472.02      .1
   583.5     .08   599.6    .016   611.6     .08   824.4     .06    1005     .05
  1121.5    .016  1131.2     .05  1201.6    .016  1212.2     .05  1281.7     .08
BR D #Sta/Elev= 30
       0 2931.64    30.5 2927.89    48.1 2929.93      86 2929.07   113.9 2916.88
   168.1 2910.07   180.6 2908.01   218.1 2901.16   347.4 2900.11   359.8 2899.81
   405.8 2897.39  412.16  2893.2  445.67 2891.82  453.02 2892.67   497.5 2896.95
   558.5 2897.76   650.6 2893.84   722.7 2893.87   738.8  2896.2   754.8 2893.52
   766.8 2896.78     812 2898.03   900.5 2895.61   932.7 2894.18  1001.6 2897.16
  1157.3 2899.56  1198.2 2900.37  1314.5 2911.93  1372.8 2920.61    1491 2946.42
BR D #Mann= 14
       0      .1    48.1    .016      86      .1   168.1    .016   180.6     .07
   347.4    .016   359.8     .07  412.16     .03  453.02     .08   900.5     .07
  1001.6     .05  1157.3    .016  1198.2     .05  1314.5     .08
BC Design=,, 0 ,, 0 ,,,,,,
BC Use User HTab Curves=0
BC User HTab FreeFlow(D)= 0

Type RM Length L Ch R = 1 ,39246   ,197.1,187.6,175.7
BEGIN DESCRIPTION:
structure xs 2
channel burned per surveyed cross section data, banks placed persurvey data
END DESCRIPTION:
XS GIS Cut Line= 4
2332945.74499643571895.9326095162332798.70565829 572395.55014557
2332814.51633981572680.1424129432332503.04591385573290.434719642
#Sta/Elev= 30
       0 2931.64    30.5 2927.89    48.1 2929.93      86 2929.07   113.9 2916.88
   168.1 2910.07   180.6 2908.01   218.1 2901.16   347.4 2900.11   359.8 2899.81
   405.8 2897.39  412.16  2893.2  445.67 2891.82  456.86 2893.13   497.5 2896.95
   558.5 2897.76   650.6 2893.84   722.7 2893.87   738.8  2896.2   754.8 2893.52
   766.8 2896.78     812 2898.03   900.5 2895.61   932.7 2894.18  1001.6 2897.16
  1157.3 2899.56  1198.2 2900.37  1314.5 2911.93  1372.8 2920.61    1491 2946.42
#Mann= 14 ,-1,0
       0      .1       0    48.1    .016       0      86      .1       0
   168.1    .016       0   180.6     .07       0   347.4    .016       0
   359.8     .07       0  412.16    .035       0  456.86     .08       0
   900.5     .07       0  1001.6     .05       0  1157.3    .016       0
  1198.2     .05       0  1314.5     .08       0
#XS Ineff= 3 ,-1
       0   407.6 2898.65     492     738 2896.73  797.08 1350.612901.372
Permanent Ineff=
       F       F       F
Bank Sta=412.16,456.86
XS Rating Curve= 0 ,0
Exp/Cntr(USF)=0,0
Exp/Cntr=0.5,0.3

Type RM Length L Ch R = 1 ,39059   ,390.1,449.3,414.4
BEGIN DESCRIPTION:
structure xs 1
channel from lidar:
lidar invert = 2891.1
effective invert = 2891.8
END DESCRIPTION:
XS GIS Cut Line= 4
2332623.62143125571734.5372975322332639.30442368572400.711552048
2332643.76097938572765.5200931552332338.49438938573181.425879951
#Sta/Elev= 30
       0 2925.86    26.6 2923.91    66.7 2921.35    86.7 2920.14   134.7 2918.62
   218.1 2910.15   254.7 2897.18   288.5 2897.11   398.8 2896.34   414.8 2896.61
   534.8 2896.65  544.292892.788   559.4  2891.1   586.8 2892.81   698.8  2894.9
   782.8 2892.73   814.8 2896.28   834.8 2893.71   970.8 2892.42  1018.3 2896.49
  1298.7 2900.78  1308.2 2901.14  1348.2 2902.24  1378.1 2910.94    1388  2911.2
  1394.1 2911.59  1402.9 2918.24  1425.5 2927.71  1492.2 2951.96  1547.1  2962.8
#Mann= 17 ,-1,0
       0    .016       0    26.6     .05       0    66.7    .016       0
    86.7     .06       0   218.1      .1       0   288.5     .06       0
   398.8    .016       0   414.8     .06       0  544.29    .035       0
   586.8      .1       0  1018.3     .05       0  1298.7    .016       0
  1308.2     .05       0  1348.2     .08       0  1378.1    .016       0
    1388     .08       0  1425.5     .07       0
#XS Ineff= 2 , 0
          413.59 2898.29
Permanent Ineff=
       F       F
#Block Obstruct= 2 ,-1
  104.74  162.28 2939.19 1237.77 1279.54 2920.37
Bank Sta=544.29,586.8
XS Rating Curve= 0 ,0
Exp/Cntr(USF)=0,0
Exp/Cntr=0.3,0.1

Type RM Length L Ch R = 1 ,38609   ,269.5,401.1,433.4
BEGIN DESCRIPTION:
channel burned 1.35':
lidar invert = 2888.27
interpolated invert = 2886.92
END DESCRIPTION:
Node Name=T
XS GIS Cut Line= 4
2332439.80318777571574.9757746462332267.46675919571864.311246475
2332232.68325984572642.196777293 2332006.5905141573020.072065638
#Sta/Elev= 30
       0 2921.82      48 2919.33   174.8 2911.53     226 2911.69   234.8 2910.98
   314.5 2906.58   357.7 2897.74   545.8 2891.74   605.2 2893.58   613.9 2893.86
     738  2889.8   826.1  2891.4   838.1 2889.83  912.29 2889.52   926.2 2886.92
   954.3 2886.99   961.6 2889.44  1030.6  2889.6  1070.4    2894  1261.9    2896
  1310.5 2909.72  1326.8 2920.02  1333.8 2920.66  1342.7 2920.86  1351.3 2927.66
  1418.4 2965.07  1427.1 2964.85  1441.7 2964.56  1463.8 2977.69  1555.8 3003.97
#Mann= 16 ,-1,0
       0    .016       0      48     .05       0     226     .06       0
   234.8      .1       0   545.8     .05       0   605.2    .016       0
   613.9     .06       0     738     .08       0   838.1      .1       0
  912.29    .035       0   961.6     .07       0  1261.9      .1       0
  1326.8    .016       0  1333.8      .1       0  1418.4    .016       0
  1427.1      .1       0
#XS Ineff= 2 , 0
          612.06 2902.16
Permanent Ineff=
       F       F
#Block Obstruct= 2 ,-1
   44.39   77.06 2939.53 1122.56 1162.78 2915.12
Bank Sta=912.29,961.6
XS Rating Curve= 0 ,0
Exp/Cntr(USF)=0,0
Exp/Cntr=0.3,0.1

Type RM Length L Ch R = 1 ,38208   ,276.8,293.5,233.9
BEGIN DESCRIPTION:
channel burned 1.31':
lidar invert = 2884.45
interpolated invert = 2883.14
END DESCRIPTION:
XS GIS Cut Line= 2
2332422.41143809571562.3272294292331622.39095315572664.331731422
#Sta/Elev= 30
       0    2921   167.2 2911.51   318.7  2903.5   347.3 2896.34   367.4 2894.24
   461.9  2893.3   473.3 2891.07   492.9 2892.41   512.6 2889.36     542 2889.27
   586.8 2890.31   601.6 2890.95   711.9  2889.4   742.3 2886.69   765.5  2885.5
     774 2883.14  820.65    2885   862.8 2884.68   888.9 2888.54   922.9 2886.53
  1025.1 2885.74  1046.1 2886.28  1071.2 2882.47  1086.4 2885.16  1135.5 2928.72
  1147.7 2937.51  1183.6 2951.22  1199.7 2962.49  1252.3 2983.74  1361.8 3034.65
#Mann= 12 ,-1,0
       0     .05       0   167.2     .06       0   318.7      .1       0
     542     .06       0   586.8    .016       0   601.6     .05       0
   742.3     .08       0   765.5    .035       0  820.65     .08       0
   862.8      .1       0   922.9     .07       0  1025.1      .1       0
#XS Ineff= 2 , 0
          621.52 2908.84
Permanent Ineff=
       F       F
#Block Obstruct= 1 ,-1
   36.69   92.55 2938.08
Bank Sta=765.5,820.65
XS Rating Curve= 0 ,0
Exp/Cntr(USF)=0,0
Exp/Cntr=0.3,0.1

Type RM Length L Ch R = 1 ,37915   ,198.6,256.4,271.2
BEGIN DESCRIPTION:
channel from lidar:
lidar invert = 2879.64
interpolated invert = 2881.15
END DESCRIPTION:
XS GIS Cut Line= 4
2332372.19268037571488.6459741552331792.75382619 571929.16968187
2331630.06041141572274.5803163282331427.31938684572436.022243303
#Sta/Elev= 30
       0 2919.85   291.6 2904.31   326.6 2902.91   371.9 2889.19   482.8 2889.49
   525.6 2889.96   549.4 2885.75   582.5 2889.19     617 2885.01   628.1 2888.57
   688.3  2888.5   813.7  2887.8   842.9 2887.51   873.8 2880.18   895.9 2883.92
   922.4 2884.56   935.7 2882.75   966.7 2884.69   975.5 2882.03   988.8 2879.64
  1031.9 2882.17  1041.8 2884.14  1055.1  2880.3  1067.2 2880.04  1076.6 2882.65
  1158.4 2940.91  1184.5 2952.37  1197.3 2964.04  1212.5 2974.06  1368.9 3064.14
#Mann= 8 ,-1,0
       0     .05       0   291.6      .1       0   482.8     .06       0
   549.4      .1       0   688.3     .06       0   813.7      .1       0
   975.5    .035       0  1031.9      .1       0
#XS Ineff= 2 , 0
          704.36 2892.59
Permanent Ineff=
       F       F
#Block Obstruct= 1 ,-1
  624.43  663.35 2908.04
Bank Sta=975.5,1031.9
XS Rating Curve= 0 ,0
Exp/Cntr(USF)=0,0
Exp/Cntr=0.3,0.1

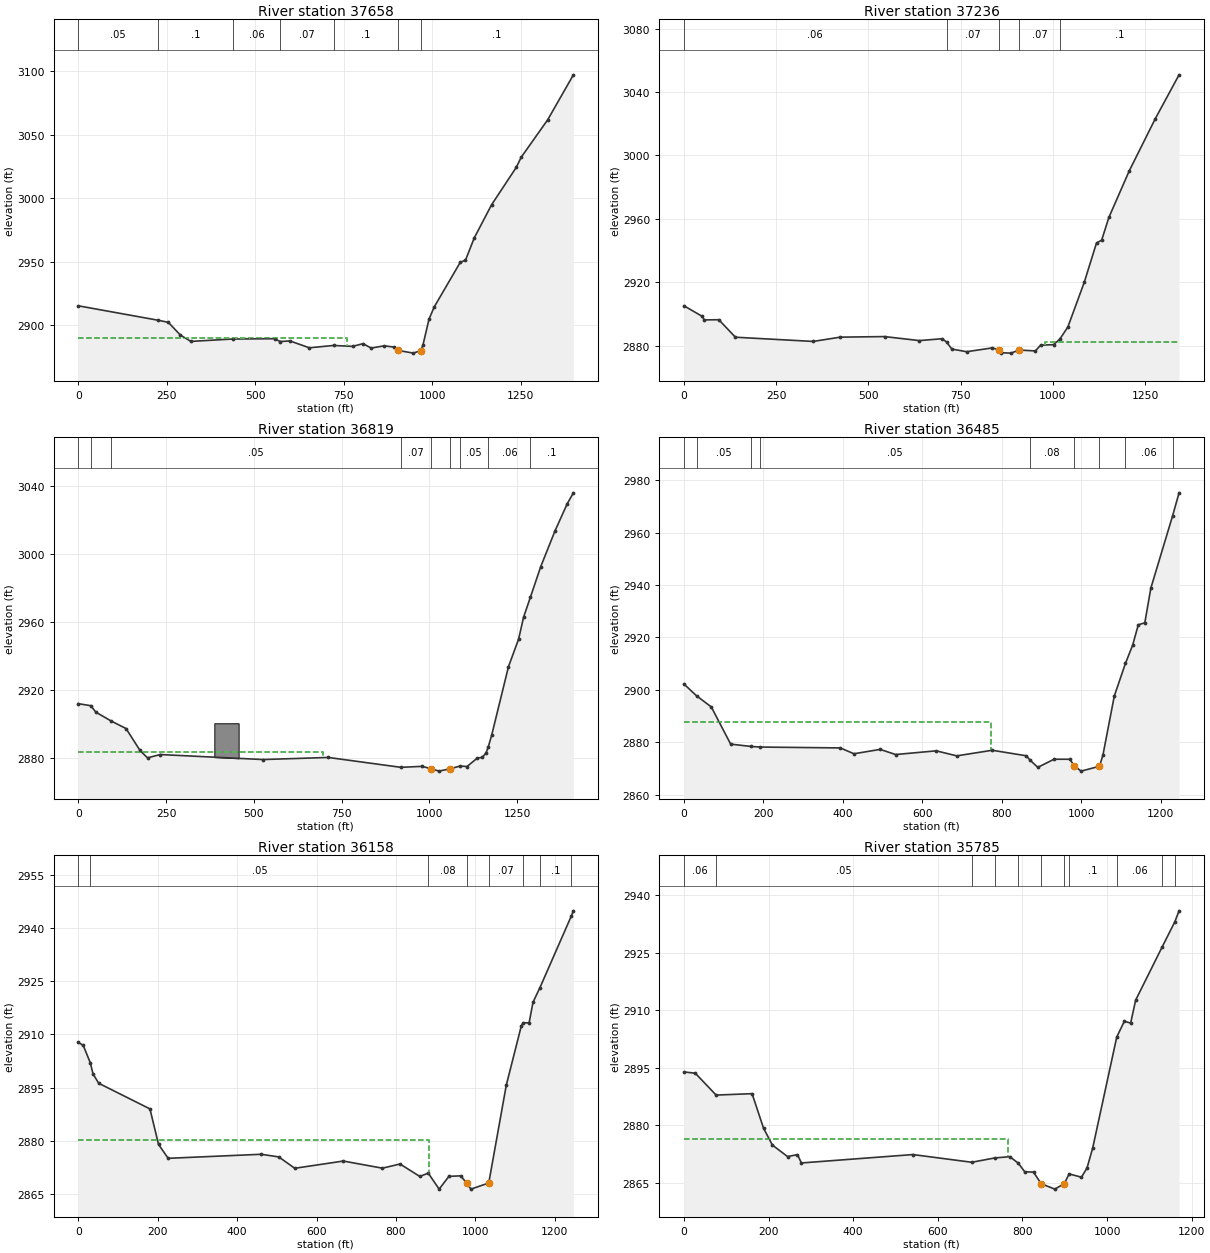
Type RM Length L Ch R = 1 ,37658   ,427.5,422.8,416.5
BEGIN DESCRIPTION:
channel from lidar:
lidar invert = 2878.06
interpolated invert = 2879.08
END DESCRIPTION:
XS GIS Cut Line= 2
2332275.37209995571450.071390632     2331136.009      572262.327
#Sta/Elev= 30
       0 2915.32   225.9 2903.94   254.5 2902.29   288.4  2892.3   318.3 2887.29
   436.2 2889.17   555.2  2889.4   570.4  2887.2   598.2 2887.65   653.1 2882.26
   721.5  2884.1   775.2 2883.38   804.7  2885.5   827.6 2882.09   864.9  2883.8
   893.1 2882.79   902.2 2880.28   947.1 2878.06     9682880.126   973.9 2884.15
   991.3 2904.89  1006.1 2914.49  1079.7 2949.62  1094.3 2951.18    1119 2968.71
  1168.2 2994.93  1237.7 3024.23    1252 3032.37  1326.6 3061.75  1399.3 3097.18
#Mann= 7 ,-1,0
       0     .05       0   225.9      .1       0   436.2     .06       0
   570.4     .07       0   721.5      .1       0   902.2    .035       0
     968      .1       0
#XS Ineff= 2 , 0
          758.48 2889.94
Permanent Ineff=
       F       F
Bank Sta=902.2,968
XS Rating Curve= 0 ,0
Exp/Cntr=0.3,0.1

Type RM Length L Ch R = 1 ,37236   ,452.1,417,396.4
BEGIN DESCRIPTION:
channel burned 1.18':
lidar invert = 2876.45
interpolated invert = 2875.27
END DESCRIPTION:
XS GIS Cut Line= 2
2332011.49608258571095.147934466      2330940.79      571904.025
#Sta/Elev= 30
       0 2905.14    49.3  2898.5    55.2 2896.22    94.4 2896.36   139.5 2885.31
   350.1 2882.65   423.6 2885.35   543.6 2885.71   637.8 2883.18   700.6 2884.37
     712 2882.15   726.1 2877.83   766.2 2876.16   834.8 2878.53   854.8 2877.44
   860.5  2875.5   886.2 2875.27   908.6 2877.22   952.3 2876.66   966.7 2880.29
  1001.8 2880.61  1018.7  2884.1  1040.5 2891.74    1085 2919.97  1118.2  2944.8
  1132.1 2946.53  1151.8 2960.94  1207.3 2990.47  1277.6 3023.23  1341.9 3050.87
#Mann= 5 ,-1,0
       0     .06       0     712     .07       0   854.8    .035       0
   908.6     .07       0  1018.7      .1       0
#XS Ineff= 2 , 0
                           978.8          2882.5
Permanent Ineff=
       F       F
Bank Sta=854.8,908.6
XS Rating Curve= 0 ,0
Exp/Cntr=0.3,0.1

Type RM Length L Ch R = 1 ,36819   ,284.9,333.3,342.5
BEGIN DESCRIPTION:
channel burned 0.13':
lidar invert = 2872.1
interpolated invert = 2871.97
END DESCRIPTION:
Node Name=S
XS GIS Cut Line= 3
2331790.86254846570734.0231919832331063.57119851571257.532424558
2330764.92499201571675.637113661
#Sta/Elev= 30
       0 2911.78    35.7 2910.59      50 2906.78    94.4 2901.46     136 2897.11
   175.8 2884.16   197.1  2879.8   233.4 2881.76   525.6 2878.81     712 2880.04
   918.4 2874.22   979.2 2874.78 1003.21 2873.46  1027.3 2871.97  1058.9 2873.36
  1087.4 2874.98    1107 2874.69  1135.9  2879.6  1150.6 2880.12  1161.1 2882.66
  1167.8 2886.49  1177.2 2893.18    1225  2933.6  1253.9  2949.9  1268.2 2962.93
  1287.3  2974.5  1316.9 2992.67  1357.7 3013.84  1392.2 3029.73  1409.9 3036.24
#Mann= 9 ,-1,0
       0    .016       0    35.7     .06       0    94.4     .05       0
   918.4     .07       0 1003.21    .035       0  1058.9     .07       0
  1087.4     .05       0  1167.8     .06       0  1287.3      .1       0
#XS Ineff= 2 , 0
          695.86 2883.44
Permanent Ineff=
       F       F
#Block Obstruct= 1 ,-1
  387.38  456.58 2900.22
Bank Sta=1003.21,1058.9
XS Rating Curve= 0 ,0
Exp/Cntr(USF)=0,0
Exp/Cntr=0.3,0.1

Type RM Length L Ch R = 1 ,36485   ,329.7,327.8,327.1
BEGIN DESCRIPTION:
channel from lidar
END DESCRIPTION:
XS GIS Cut Line= 2
2331566.39200198 570583.719191262330541.26015705571293.062185166
#Sta/Elev= 30
       0 2902.23    31.9 2897.71    68.8  2893.5   117.6 2879.31   169.4 2878.41
   192.4 2878.19   393.6 2877.86   428.1 2875.63     494  2877.3   532.9 2875.34
   635.2 2876.75   686.9 2874.83   776.1 2876.97   862.2 2874.86   870.9 2873.28
     891 2870.45   931.8 2873.55   971.5 2873.54     983 2871.02   999.9 2869.01
  1046.2 2870.86  1054.9 2875.08  1083.6 2897.67  1111.7 2910.12  1129.6 2916.97
    1144 2924.82  1160.4 2925.57  1175.6  2938.8  1230.2 2966.29  1246.6 2975.14
#Mann= 9 ,-1,0
       0     .06       0    31.9     .05       0   169.4      .1       0
   192.4     .05       0   870.9     .08       0     983    .035       0
  1046.2      .1       0  1111.7     .06       0  1230.2      .1       0
#XS Ineff= 2 , 0
          772.96 2887.59
Permanent Ineff=
       F       F
Bank Sta=983,1046.2
XS Rating Curve= 0 ,0
Exp/Cntr(USF)=0,0
Exp/Cntr=0.3,0.1

Type RM Length L Ch R = 1 ,36158   ,362.5,373,378.8
BEGIN DESCRIPTION:
channel from lidar
END DESCRIPTION:
XS GIS Cut Line= 2
2331366.16717841570303.3729666032330353.54972506571030.307842335
#Sta/Elev= 30
       0 2907.72    12.3 2906.95    30.5 2901.91    37.1 2898.85    51.4 2896.22
   180.4 2888.99     202 2878.97   226.3 2875.05   460.4 2876.19   504.7 2875.45
     545 2872.24   667.2 2874.28   765.7 2872.27     810 2873.45   859.8 2869.94
   881.1 2870.87   908.5 2866.37   933.1 2869.96   962.9 2870.11   977.4  2868.1
   988.7 2866.36 1033.43  2868.1  1077.6  2895.7  1115.3 2912.37  1120.2 2913.29
    1135 2913.26  1144.8 2919.06  1162.3  2923.2    1241 2943.32  1246.5 2944.86
#Mann= 8 ,-1,0
       0     .08       0    30.5     .05       0   881.1     .08       0
   977.4    .035       0 1033.43     .07       0  1120.2     .06       0
  1162.3      .1       0    1241     .08       0
#XS Ineff= 2 , 0
          881.93 2880.24
Permanent Ineff=
       F       F
Bank Sta=977.4,1033.43
XS Rating Curve= 0 ,0
Exp/Cntr(USF)=0,0
Exp/Cntr=0.3,0.1

Type RM Length L Ch R = 1 ,35785   ,403.7,406.5,397.2
BEGIN DESCRIPTION:
channel from lidar
END DESCRIPTION:
XS GIS Cut Line= 2
2331168.16935234570164.7744883512330121.60941451570688.054457263
#Sta/Elev= 30
       0 2893.95    26.8 2893.62      76 2887.91     161 2888.28   188.1 2879.26
     209 2874.87   244.8 2871.87   268.3 2872.37   277.6  2870.2   541.1 2872.39
   680.1 2870.38   734.3  2871.5   770.1 2871.84   790.4 2870.12   805.3  2867.9
   826.2 2867.81     844  2864.8   876.5 2863.37   898.9 2864.81   910.32867.343
   939.4 2866.48   952.6 2868.88     966 2874.09  1022.9 2903.07  1040.8 2907.17
  1055.7  2906.7  1067.6  2912.7  1130.3 2926.59  1160.1 2933.12  1170.1 2935.99
#Mann= 11 ,-1,0
       0     .06       0      76     .05       0   680.1     .08       0
   734.3      .1       0   790.4     .05       0     844    .035       0
   898.9     .05       0   910.3      .1       0  1022.9     .06       0
  1130.3      .1       0  1160.1     .08       0
#XS Ineff= 2 , 0
          766.65 2876.48
Permanent Ineff=
       F       F
Bank Sta=844,898.9
XS Rating Curve= 0 ,0
Exp/Cntr(USF)=0,0
Exp/Cntr=0.3,0.1

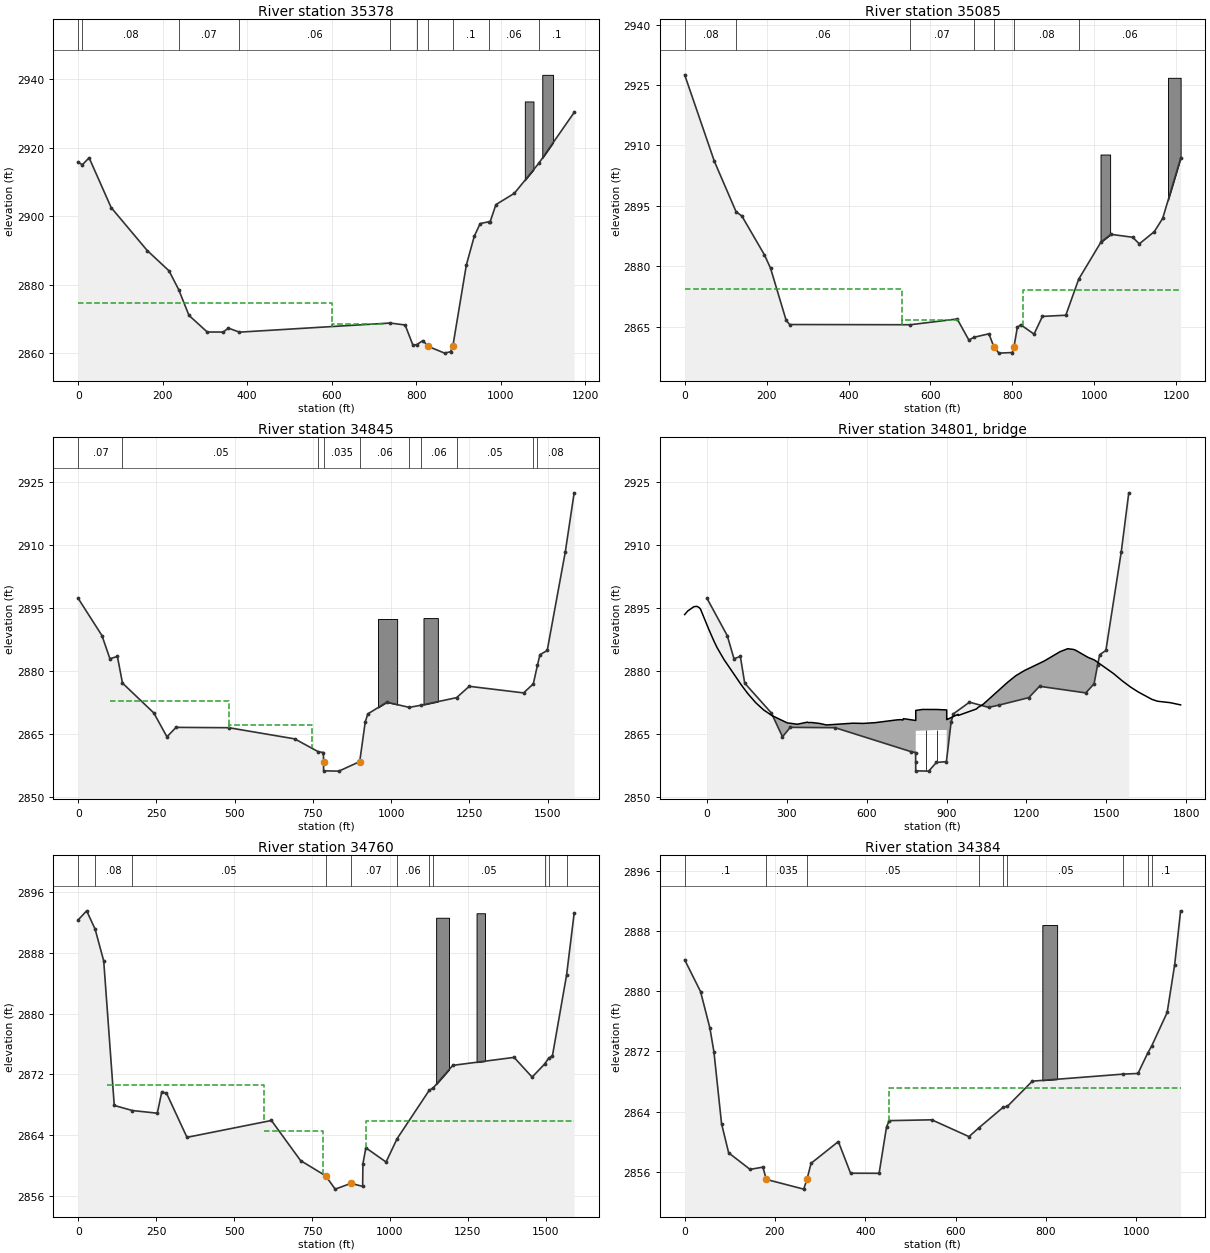
Type RM Length L Ch R = 1 ,35378   ,265.4,293.1,304.8
BEGIN DESCRIPTION:
channel from lidar
END DESCRIPTION:
Node Name=R
XS GIS Cut Line= 5
2330920.15011933569832.6008591052330643.42135052569941.605757238
2330382.82327628570090.7132448842330081.44006865570273.099621851
2329890.70116267570390.565839133
#Sta/Elev= 30
       0  2915.8     9.7 2915.06    25.8 2917.09      78 2902.55   163.3 2890.01
   214.9 2884.08   237.9 2878.57   262.2 2871.05   305.4  2866.2   343.5 2866.19
   355.2 2867.35   381.6 2866.16   738.3 2868.82   773.8 2868.25   792.5 2862.29
   801.8 2862.55   815.8 2863.69   828.6 2861.98   867.3 2860.03   881.3 2860.44
   886.8 2862.09   918.7 2885.76   937.4 2894.14   951.4 2897.88   971.3 2898.39
   974.9 2898.34   988.7 2903.42  1032.3 2906.71  1090.5 2915.54  1173.9 2930.34
#Mann= 10 ,-1,0
       0    .016       0     9.7     .08       0   237.9     .07       0
   381.6     .06       0   738.3      .1       0   801.8     .08       0
   828.6    .035       0   886.8      .1       0   971.3     .06       0
  1090.5      .1       0
#XS Ineff= 2 ,-1
       0   599.72874.796   599.7  729.23  2868.5
Permanent Ineff=
       F       F
#Block Obstruct= 2 ,-1
 1057.13 1077.58 2933.55 1098.45 1124.04 2941.33
Bank Sta=828.6,886.8
XS Rating Curve= 0 ,0
Exp/Cntr(USF)=0,0
Exp/Cntr=0.3,0.1

Type RM Length L Ch R = 1 ,35085   ,206,239.8,269.3
BEGIN DESCRIPTION:
structure xs 4 - channel from lidar
END DESCRIPTION:
XS GIS Cut Line= 3
2330779.52549455 569725.089578272330411.81977138569883.759874648
  2329617.325925570043.369048925
#Sta/Elev= 30
       0 2927.52    72.6 2906.01   125.6  2893.5   139.6 2892.47   194.3  2882.9
   209.6 2879.52   247.6 2866.61   256.3 2865.52   550.9 2865.47   665.3  2866.9
   693.9 2861.66   706.1 2862.35   742.8 2863.22   755.1 2859.93   767.3 2858.42
   799.9 2858.57     804    2860   812.2  2864.8   820.3 2865.48     853 2863.14
   873.4 2867.54   930.5 2867.83     962 2876.78  1016.3 2885.98  1040.7 2887.92
  1093.7 2887.19    1110 2885.55  1146.7 2888.59  1167.1 2891.89  1210.8 2906.78
#Mann= 7 ,-1,0
       0     .08       0   125.6     .06       0   550.9     .07       0
   706.1     .08       0   755.1    .035       0     804     .08       0
     962     .06       0
#XS Ineff= 3 ,-1
       0  530.592874.252  530.59  667.712866.574  826.51  1210.8    2874
Permanent Ineff=
       F       F       F
#Block Obstruct= 2 ,-1
 1015.32 1038.72 2907.73 1180.13 1210.85 2926.78
Bank Sta=755.1,804
XS Rating Curve= 0 ,0
Exp/Cntr=0.5,0.3

Type RM Length L Ch R = 1 ,34845   ,79.3,85.3,95.7
BEGIN DESCRIPTION:
structure xs 3
channel burned per surveyed cross section data
END DESCRIPTION:
XS GIS Cut Line= 6
2330603.30469202569516.6007148892330518.98105724569572.816471407
2330404.79280181569839.8413148682330304.65848551569845.111542041
2329738.98743555569655.3833637932329385.88221492569992.677902901
#Sta/Elev= 30
       0 2897.18    75.9 2888.33   101.3 2882.82   125.2 2883.36   141.5 2877.01
   241.6 2869.91   283.5 2864.22   312.7 2866.47   481.3 2866.39   691.8 2863.73
   767.2 2860.67   783.5 2860.48  784.01 2858.29  784.14 2856.12  832.92 2856.05
   899.5 2858.32   917.1 2867.74   925.4 2869.68   986.1 2872.47  1057.7 2871.23
  1096.4 2871.76    1209 2873.55  1249.5 2876.25  1423.3 2874.68  1454.3 2876.85
  1467.4 2881.28  1475.4 2883.78  1498.6 2884.78  1556.5 2908.31  1584.7 2922.33
#Mann= 10 ,-1,0
       0     .07       0   141.5     .05       0   767.2     .08       0
  784.01    .035       0   899.5     .06       0  1057.7    .016       0
  1096.4     .06       0    1209     .05       0  1454.3    .016       0
  1467.4     .08       0
#XS Ineff= 3 ,-1
  102.76  483.15 2872.71  483.15     747 2867.06     938  1584.7 2868.34
Permanent Ineff=
       F       F       F
#Block Obstruct= 2 ,-1
  957.81 1019.09 2892.28 1103.27 1149.18  2892.5
Bank Sta=784.01,899.5
XS Rating Curve= 0 ,0
Exp/Cntr(USF)=0,0
Exp/Cntr=0.5,0.3

Type RM Length L Ch R = 3 ,34801   ,,,
BEGIN DESCRIPTION:
Bridge 54075EFG050
JV notes: road deck updated per surveyed XS data points
channel burned per surveyed cross section points
structure opening and piers based on survey data, photos, and aerial imagery
surveyed inverts are approximately 1-1.5' below inverts from lidar:
 surveyed invert US is 2856.78
 surveyed invert DS is 2856.89
END DESCRIPTION:
Bridge Culvert--1,0,-1,-1, 0
Deck Dist Width WeirC Skew NumUp NumDn MinLoCord MaxHiCord MaxSubmerge Is_Ogee
35,18,2.6,0, 60, 60, , , 0.98, 0, 0,0,,
     -84 -72.813 -49.347 -38.177 -30.083  -24.78   6.833  26.739  38.063  63.783
 128.914 152.889 182.964  213.04 243.773 301.055 339.298 377.265 381.775 392.085
 422.867 448.705  548.17 586.884 632.311 716.485 729.384 735.527     738  763.39
  784.28  784.28  809.71  863.73  900.57  900.57  901.59  943.45 943.8651012.023
1018.4171037.8121129.9691160.2661193.0391266.7091326.492 1355.281376.7961384.684
  1431.11455.1641526.809  1559.41591.4451620.9821671.6171692.7151739.4441779.455
2893.3342894.1722895.211 2895.292895.0192894.6732889.7832886.9042885.426 2882.62
2876.5672874.5322872.3452870.6032869.288 2867.552867.2192867.7172867.6032867.638
2867.4042867.0452867.4662867.4122867.5972868.2792868.3132868.208 2868.54 2868.31
 2868.11 2870.51 2870.74 2870.73 2870.62 2868.32 2868.34 2869.582869.3032870.849
2871.2192871.9872877.239 2878.782880.0172882.2652884.5012885.2052885.0332884.852
2883.1562882.527 2879.312877.5862876.0672874.8752873.1412872.694 2872.362871.826
                                                                                
                                                                                
                                                                                
 2865.65 2865.65 2865.71 2865.85 2865.85 2865.85
                                                                                
                                                                                
     -72 -60.813 -37.347 -26.177 -18.083  -12.78  18.833  38.739  50.063  75.783
 140.914 164.889 194.964  225.04 255.773 313.055 351.298 389.265 393.775 404.085
 434.867 460.705  560.17 598.884 644.311 728.485 741.384 747.527     750  775.39
  796.28  796.28  821.71  875.73  912.57  912.57  913.59  955.45 955.8651024.023
1030.4171049.8121141.9691172.2661205.0391278.7091338.492 1367.281388.7961396.684
  1443.11467.1641538.809  1571.41603.4451632.9821683.6171704.7151751.4441791.455
2893.3342894.1722895.211 2895.292895.0192894.6732889.7832886.9042885.426 2882.62
2876.5672874.5322872.3452870.6032869.288 2867.552867.2192867.7172867.6032867.638
2867.4042867.0452867.4662867.4122867.5972868.2792868.3132868.208 2868.54 2868.31
 2868.11 2870.51 2870.74 2870.73 2870.62 2868.32 2868.34 2869.582869.3032870.849
2871.2192871.9872877.239 2878.782880.0172882.2652884.5012885.2052885.0332884.852
2883.1562882.527 2879.312877.5862876.0672874.8752873.1412872.694 2872.362871.826
                                                                                
                                                                                
                                                                                
 2865.65 2865.65 2865.71 2865.85 2865.85 2865.85
                                                                                
                                                                                
Pier Skew, UpSta & Num, DnSta & Num=  ,823.04, 2 ,835.04, 2 , 0 , 0 , 0 ,,
       2       2
       0  2865.9
       2       2
       0  2865.9
Pier Skew, UpSta & Num, DnSta & Num=  ,863.23, 2 ,875.23, 2 , 0 , 0 , 0 ,,
       2       2
       0  2865.9
       2       2
       0  2865.9
BR Coef=-1 ,-1 , 0 ,, 0 ,,,0.8,0,1.2,0,
WSPro=,,,, 1 ,,,, 0 ,,,, 0 ,,,,-1 ,-1 ,-1 , 0 , 0 , 0 , 0 , 0
BR U #Sta/Elev= 30
       0 2897.18    75.9 2888.33   101.3 2882.82   125.2 2883.36   141.5 2877.01
   241.6 2869.91   283.5 2864.22   312.7 2866.47   481.3 2866.39   767.2 2860.67
   783.5 2860.48  784.01 2858.29  784.14 2856.12  832.92 2856.05  861.64 2858.11
   899.5 2858.32   917.1 2867.74   925.4 2869.68   986.1 2872.47  1057.7 2871.23
  1096.4 2871.76    1209 2873.55  1249.5 2876.25  1423.3 2874.68  1454.3 2876.85
  1467.4 2881.28  1475.4 2883.78  1498.6 2884.78  1556.5 2908.31  1584.7 2922.33
BR U #Mann= 10
       0     .07   141.5     .05   767.2     .08  784.01     .03  861.64     .06
  1057.7    .016  1096.4     .06    1209     .05  1454.3    .016  1467.4     .08
BR D #Sta/Elev= 30
       0 2892.35    27.1 2893.54    54.2 2891.13    81.8 2886.94   115.6 2867.91
   173.8 2867.24   253.6 2866.89   267.9 2869.67     283 2869.54   348.9 2863.71
   619.7 2865.93   713.2 2860.65   793.4 2858.65  824.32 2856.89  874.93 2857.65
  912.26 2857.25   913.2 2860.23   922.6 2862.33   987.4 2860.46  1022.9 2863.54
  1125.5 2869.88  1138.6 2870.23  1201.6 2873.19  1398.1 2874.24  1455.9 2871.64
  1495.6 2873.35  1509.2 2874.14    1521 2874.44  1566.4 2885.08  1590.7 2893.21
BR D #Mann= 11
       0    .016    54.2     .08   173.8     .05   793.4     .03  874.93     .07
  1022.9     .06  1125.5    .016  1138.6     .05  1495.6    .016  1509.2     .08
  1566.4      .1
BC Design=,, 0 ,, 0 ,,,,,,
BC Use User HTab Curves=0
BC User HTab FreeFlow(D)= 0

Type RM Length L Ch R = 1 ,34760   ,448.1,375.7,316.6
BEGIN DESCRIPTION:
structure xs 2
channel burned per surveyed cross section data
END DESCRIPTION:
XS GIS Cut Line= 6
2330598.03446484569439.3040496772330504.92711811569507.817002933
2330373.17143877569762.5446496552330318.71242464569767.814876829
2329756.55485946 569576.329956192329356.01759427 569931.19191921
#Sta/Elev= 30
       0 2892.35    27.1 2893.54    54.2 2891.13    81.8 2886.94   115.6 2867.91
   173.8 2867.24   253.6 2866.89   267.9 2869.67     283 2869.54   348.9 2863.71
   619.7 2865.93   713.2 2860.65   793.4 2858.65  824.32 2856.89  874.93 2857.65
  912.26 2857.25   913.2 2860.23   922.6 2862.33   987.4 2860.46  1022.9 2863.54
  1125.5 2869.88  1138.6 2870.23  1201.6 2873.19  1398.1 2874.24  1455.9 2871.64
  1495.6 2873.35  1509.2 2874.14    1521 2874.44  1566.4 2885.08  1590.7 2893.21
#Mann= 11 ,-1,0
       0    .016       0    54.2     .08       0   173.8     .05       0
   793.4    .035       0  874.93     .07       0  1022.9     .06       0
  1125.5    .016       0  1138.6     .05       0  1495.6    .016       0
  1509.2     .08       0  1566.4      .1       0
#XS Ineff= 3 ,-1
   92.53  596.24 2870.58  596.24     785  2864.5     924  1590.7  2865.8
Permanent Ineff=
       F       F       F
#Block Obstruct= 2 ,-1
 1148.05 1189.34 2892.63 1277.63 1304.81 2893.22
Bank Sta=793.4,874.93
XS Rating Curve= 0 ,0
Exp/Cntr(USF)=0,0
Exp/Cntr=0.5,0.3

Type RM Length L Ch R = 1 ,34384   ,540.4,507.6,428.6
BEGIN DESCRIPTION:
xs 1 - channel from lidar
END DESCRIPTION:
XS GIS Cut Line= 3
2330065.74152031569179.3061757812329542.23228774569453.357988806
2329343.72039753569920.651464863
#Sta/Elev= 30
       0 2884.16    35.1 2879.95    55.9 2875.09    64.8 2871.94    81.7  2862.4
    97.4 2858.54   144.8 2856.34   173.3 2856.64  180.81 2855.01   263.6 2853.72
  270.84    2855     280 2857.15   340.4 2860.03   367.5 2855.83   430.7 2855.82
   447.1 2861.96     453 2862.81   547.4 2862.92   629.8 2860.69   651.6 2861.85
   705.2 2864.57   715.1 2864.72   770.1 2868.05     972 2868.99  1004.1 2869.07
  1025.8 2871.79  1034.6 2872.73  1068.8 2877.17  1085.4  2883.5  1098.6 2890.66
#Mann= 9 ,-1,0
       0      .1       0  180.81    .035       0  270.84     .05       0
   651.6     .06       0   705.2    .016       0   715.1     .05       0
     972     .06       0  1025.8    .016       0  1034.6      .1       0
#XS Ineff= 2 , 0
                             453         2867.13
Permanent Ineff=
       F       F
#Block Obstruct= 1 ,-1
  792.27  825.04 2888.77
Bank Sta=180.81,270.84
XS Rating Curve= 0 ,0
Exp/Cntr(USF)=0,0
Exp/Cntr=0.3,0.1

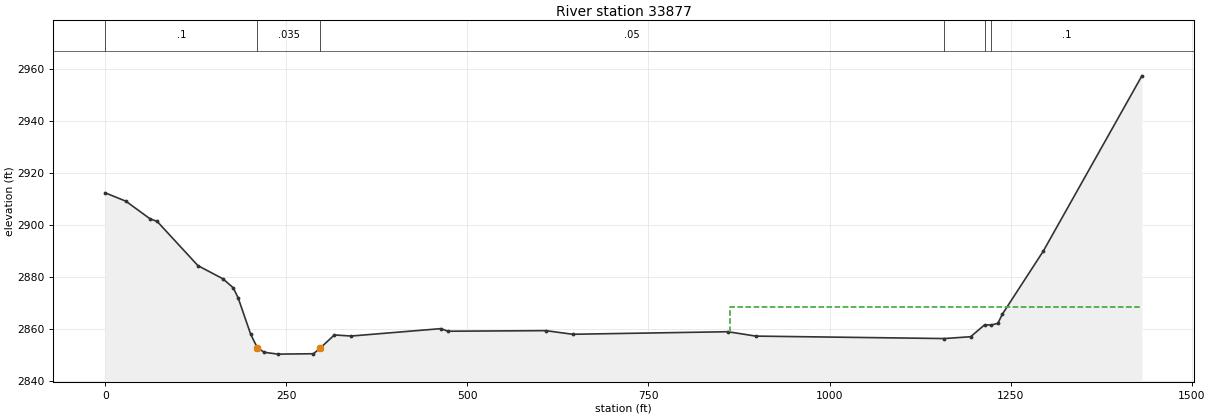
Type RM Length L Ch R = 1 ,33877   ,429,425.6,402.1
BEGIN DESCRIPTION:
channel from lidar
END DESCRIPTION:
XS GIS Cut Line= 5
 2329638.2876883568729.3076187232329334.58311083569193.380730289
2329108.49525925569539.3397796942328948.22251291569784.025729205
2328855.40541779569927.469700575
#Sta/Elev= 30
       0 2912.32    28.5  2909.1    62.1 2902.27    71.6 2901.34     128 2884.28
   162.4 2879.23   176.7 2875.75   183.5 2871.87   200.8 2857.85   210.2 2852.56
   219.7  2850.9   238.4  2850.2   287.5 2850.35   296.2 2852.39   316.4 2857.59
   339.5 2857.17   463.5 2860.02   473.1 2859.02   608.2 2859.25   645.2 2857.85
   859.6 2858.83   898.4 2857.14  1158.3  2856.2  1194.8  2856.9    1214 2861.45
  1223.5 2861.45  1232.4 2862.05  1238.6 2865.58  1295.1 2889.86  1431.3 2957.39
#Mann= 6 ,-1,0
       0      .1       0   210.2    .035       0   296.2     .05       0
  1158.3     .06       0    1214    .016       0  1223.5      .1       0
#XS Ineff= 2 , 0
                          862.65         2868.34
Permanent Ineff=
       F       F
Bank Sta=210.2,296.2
XS Rating Curve= 0 ,0
Exp/Cntr(USF)=0,0
Exp/Cntr=0.3,0.1