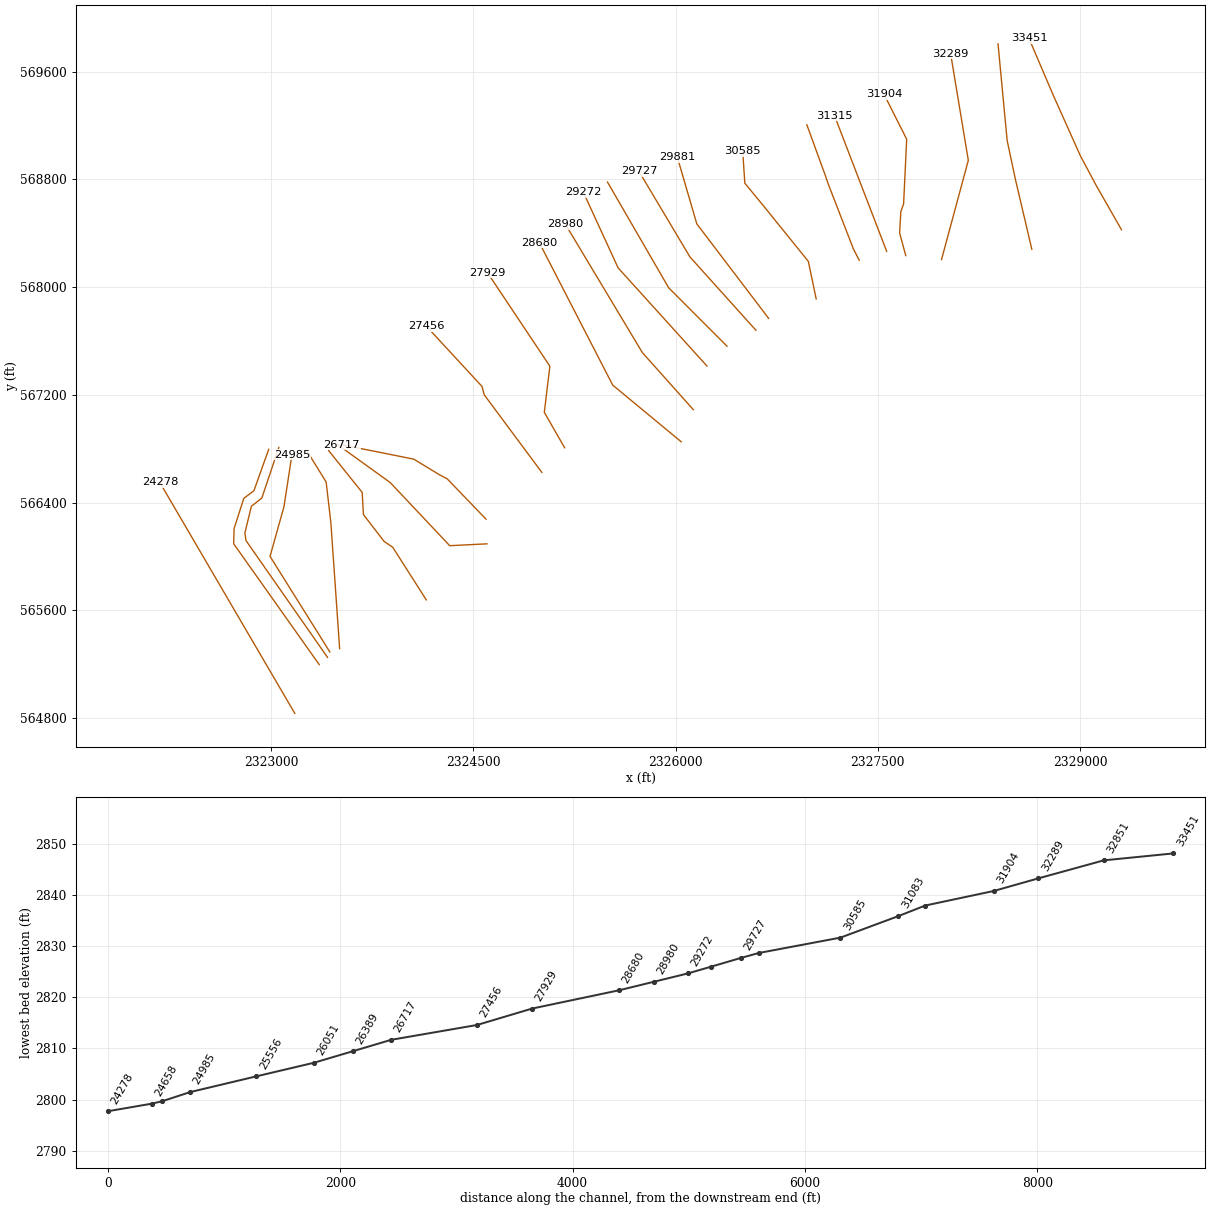
HEC-RAS study EFGRNBRRRV.prj: EFGRNBRRRV

--- EFGRNBRRRV.g01 (geometry) --- (continued)

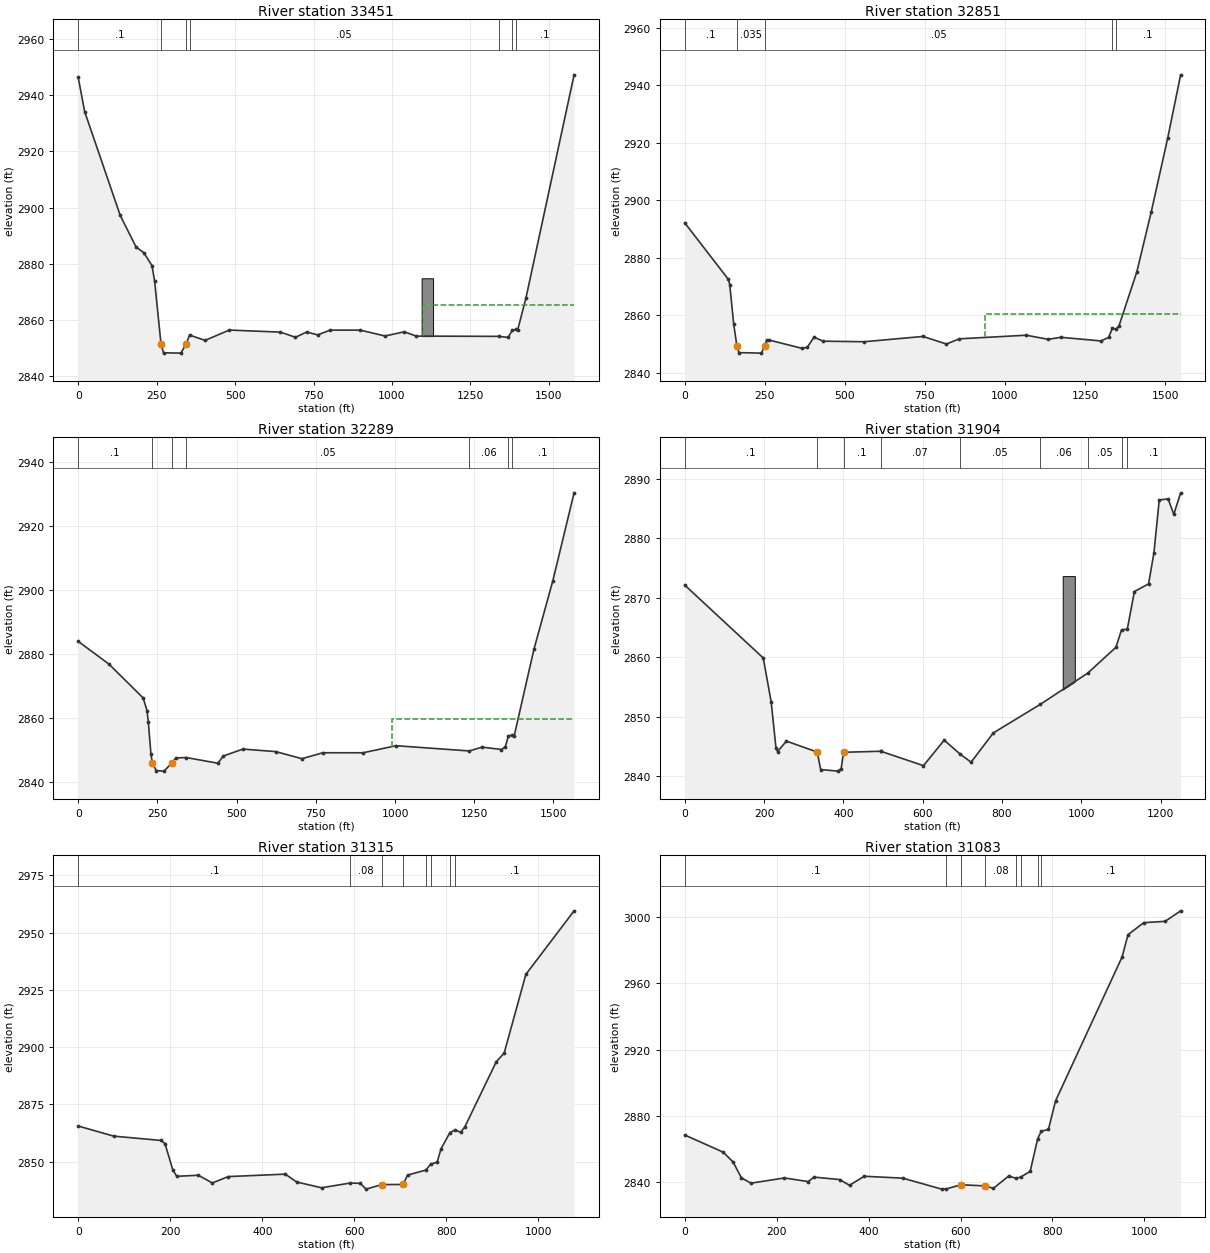
Type RM Length L Ch R = 1 ,33451   ,612.7,599.9,463.3
BEGIN DESCRIPTION:
channel from lidar
END DESCRIPTION:
Node Name=Q
XS GIS Cut Line= 5
2329307.93760982568424.9832281112329119.00570361568756.212747192
2329003.02983343568973.7561639752328797.66067333569432.989444842
 2328621.2627116569846.312737731
#Sta/Elev= 30
       0 2946.41    20.5 2934.24   133.8 2897.26   184.4 2885.97   209.4 2883.93
   235.1 2879.34   243.4 2873.94   263.9 2851.39   271.9  2848.3   327.2 2848.18
  343.82 2851.38   354.7 2854.62   404.3 2852.72   481.7  2856.4   644.6 2855.66
   692.4 2853.82     728  2855.7   763.1 2854.68   803.4 2856.38     899 2856.37
   977.7 2854.28  1039.1 2855.77  1077.7 2854.24  1339.5 2854.15  1370.3 2853.78
  1383.4 2856.38  1396.4  2856.6  1400.8 2856.58  1426.9 2867.81  1580.3 2947.31
#Mann= 7 ,-1,0
       0      .1       0   263.9    .035       0  343.82      .1       0
   354.7     .05       0  1339.5     .06       0  1383.4    .016       0
  1396.4      .1       0
#XS Ineff= 2 , 0
                         1099.72         2865.18
Permanent Ineff=
       F       F
#Block Obstruct= 1 ,-1
 1094.38 1130.91 2874.84
Bank Sta=263.9,343.82
XS Rating Curve= 0 ,0
Exp/Cntr(USF)=0,0
Exp/Cntr=0.3,0.1

Type RM Length L Ch R = 1 ,32851   ,581.4,562.5,309.8
BEGIN DESCRIPTION:
channel from lidar
END DESCRIPTION:
XS GIS Cut Line= 4
2328642.67774385568280.3197986442328522.69844166568791.129638965
2328459.64182166569087.5429234042328391.90697096569805.194445282
#Sta/Elev= 30
       0 2892.12   136.5 2872.43   140.6  2870.6   152.9 2856.94  163.02 2849.18
   169.3    2847   239.2 2846.82  249.42 2849.21   255.6 2851.25   263.8 2851.36
   366.6 2848.47     383 2848.87   403.6 2852.37   432.3 2850.97   560.5 2850.78
   744.4 2852.62   817.2 2849.98   857.5 2851.79  1066.4 2853.05  1134.8 2851.62
  1174.9 2852.32  1299.5 2851.06  1323.6 2852.28  1335.4 2855.45  1346.4 2855.18
  1355.7 2856.17    1412 2875.14  1456.6  2895.8  1508.4 2921.64  1548.6 2943.58
#Mann= 5 ,-1,0
       0      .1       0  163.02    .035       0  249.42     .05       0
  1335.4    .016       0  1346.4      .1       0
#XS Ineff= 2 , 0
                          937.46         2860.35
Permanent Ineff=
       F       F
Bank Sta=163.02,249.42
XS Rating Curve= 0 ,0
Exp/Cntr(USF)=0,0
Exp/Cntr=0.3,0.1

Type RM Length L Ch R = 1 ,32289   ,374.5,384.2,443.8
BEGIN DESCRIPTION:
channel burned 0.26':
lidar invert = 2843.56
effective invert = 2843.30
END DESCRIPTION:
XS GIS Cut Line= 3
2327972.58224565568203.4660339782328171.53082082568940.575366747
2328040.45499088569731.409129416
#Sta/Elev= 30
       0 2883.88    97.1 2876.76   204.8  2866.2   217.2 2862.25   221.4 2858.51
   229.4  2848.8   233.8 2845.92   246.2 2843.47   271.1  2843.3  296.432845.993
   308.4 2847.41   340.4 2847.56   440.9 2845.77   457.8 2848.02   519.8 2850.19
   623.2 2849.41   706.1 2847.19   772.2 2849.05   899.1 2849.04  1003.1 2851.25
  1234.4 2849.61  1274.7 2850.81  1335.8 2850.06    1348 2850.92  1357.9 2854.34
  1368.2 2854.51  1376.3 2854.43  1438.2 2881.34    1498 2902.83  1565.1 2930.33
#Mann= 7 ,-1,0
       0      .1       0   233.8    .035       0  296.43      .1       0
   340.4     .05       0  1234.4     .06       0  1357.9    .016       0
  1368.2      .1       0
#XS Ineff= 2 , 0
                          988.85         2859.71
Permanent Ineff=
       F       F
Bank Sta=233.8,296.43
XS Rating Curve= 0 ,0
Exp/Cntr(USF)=0,0
Exp/Cntr=0.3,0.1

Type RM Length L Ch R = 1 ,31904   ,187.7,589.7,413.4
BEGIN DESCRIPTION:
channel burned 1.62':
lidar invert = 2842.45
interpolated invert = 2840.83
END DESCRIPTION:
Node Name=P
XS GIS Cut Line= 6
2327707.49527698568233.2567554252327661.77948248568402.405195075
2327670.92264138568560.124686101 2327691.4947489568617.269429226
2327714.35264615569097.285271477 2327545.2042065569433.296361053
#Sta/Elev= 30
       0  2872.1     198 2859.85   218.1 2852.43   230.1 2844.75   234.1 2844.11
   256.4 2845.88   334.3 2844.03   342.8  2841.1     386 2840.83   394.5 2841.24
  400.59    2844     494 2844.17     494 2844.18   602.1 2841.75   654.4 2846.03
   694.2 2843.72   722.2 2842.33   778.3 2847.25   896.4 2852.04    1016 2857.28
  1087.5 2861.64  1101.7 2864.58  1116.2 2864.68  1134.1 2871.02  1169.9 2872.31
  1183.4 2877.53  1196.8 2886.42  1219.2 2886.59  1233.5 2883.99  1250.7 2887.61
#Mann= 9 ,-1,0
       0      .1       0   334.3    .035       0  400.59      .1       0
     494     .07       0   694.2     .05       0   896.4     .06       0
    1016     .05       0  1101.7    .016       0  1116.2      .1       0
#Block Obstruct= 1 ,-1
  953.29  983.81 2873.61
Bank Sta=334.3,400.59
XS Rating Curve= 0 ,0
Exp/Cntr(USF)=0,0
Exp/Cntr=0.3,0.1

Type RM Length L Ch R = 1 ,31315   ,225.3,231.9,222.3
BEGIN DESCRIPTION:
channel burned 0.06':
lidar invert = 2838.66
interpolated invert = 2838.60
END DESCRIPTION:
XS GIS Cut Line= 2
2327565.77631403568265.257811575 2327179.4778505569271.005290578
#Sta/Elev= 30
       0 2865.54      77 2861.12   179.9 2859.24   188.5 2857.89   205.6 2846.32
   214.2 2843.58   261.1 2844.04   291.3 2840.68   326.2 2843.46   449.8 2844.52
   474.8 2841.08   528.8 2838.57   591.2 2840.65   612.7  2840.5   625.5 2837.98
   659.8 2839.97  705.79 2840.01   715.5 2844.08   755.4 2846.33   765.8 2848.91
   779.8 2849.73   788.3 2855.57   807.7 2862.69     818 2863.74   830.9 2862.88
   839.8 2865.08   908.3 2893.59   925.5  2897.4   972.6 2931.75  1077.4 2959.51
#Mann= 8 ,-1,0
       0      .1       0   591.2     .08       0   659.8    .035       0
  705.79     .08       0   755.4    .016       0   765.8     .08       0
   807.7    .016       0     818      .1       0
Bank Sta=659.8,705.79
XS Rating Curve= 0 ,0
Exp/Cntr(USF)=0,0
Exp/Cntr=0.3,0.1

Type RM Length L Ch R = 1 ,31083   ,375.3,498,513.5
BEGIN DESCRIPTION:
channel from lidar
END DESCRIPTION:
XS GIS Cut Line= 5
 2327362.3410285 568198.969909552327318.91102372568283.544129375
  2327133.762056568761.2741819012327108.61836902568834.419453101
2326973.75677525569204.717388553
#Sta/Elev= 30
       0 2868.54    83.6 2858.21   105.4 2852.21   123.2 2842.73     144  2839.5
   216.9 2842.65   268.4 2840.47   281.3 2843.15   337.1 2841.67   358.5  2838.2
   390.4 2843.67   474.3 2842.53   559.1 2835.91   568.4 2835.97   600.8 2838.54
   653.9 2837.86   671.6 2836.41   704.7 2843.81   721.6 2842.38     731 2843.24
   751.6  2846.6   767.9 2866.33   775.7 2870.81   791.3  2871.9   806.9  2889.2
   951.6 2975.93   964.4  2989.3   998.5 2996.58  1045.3  2997.4  1078.9 3003.73
#Mann= 8 ,-1,0
       0      .1       0   568.4     .08       0   600.8    .035       0
   653.9     .08       0   721.6    .016       0     731     .08       0
   767.9    .016       0   775.7      .1       0
Bank Sta=600.8,653.9
XS Rating Curve= 0 ,0
Exp/Cntr(USF)=0,0
Exp/Cntr=0.3,0.1

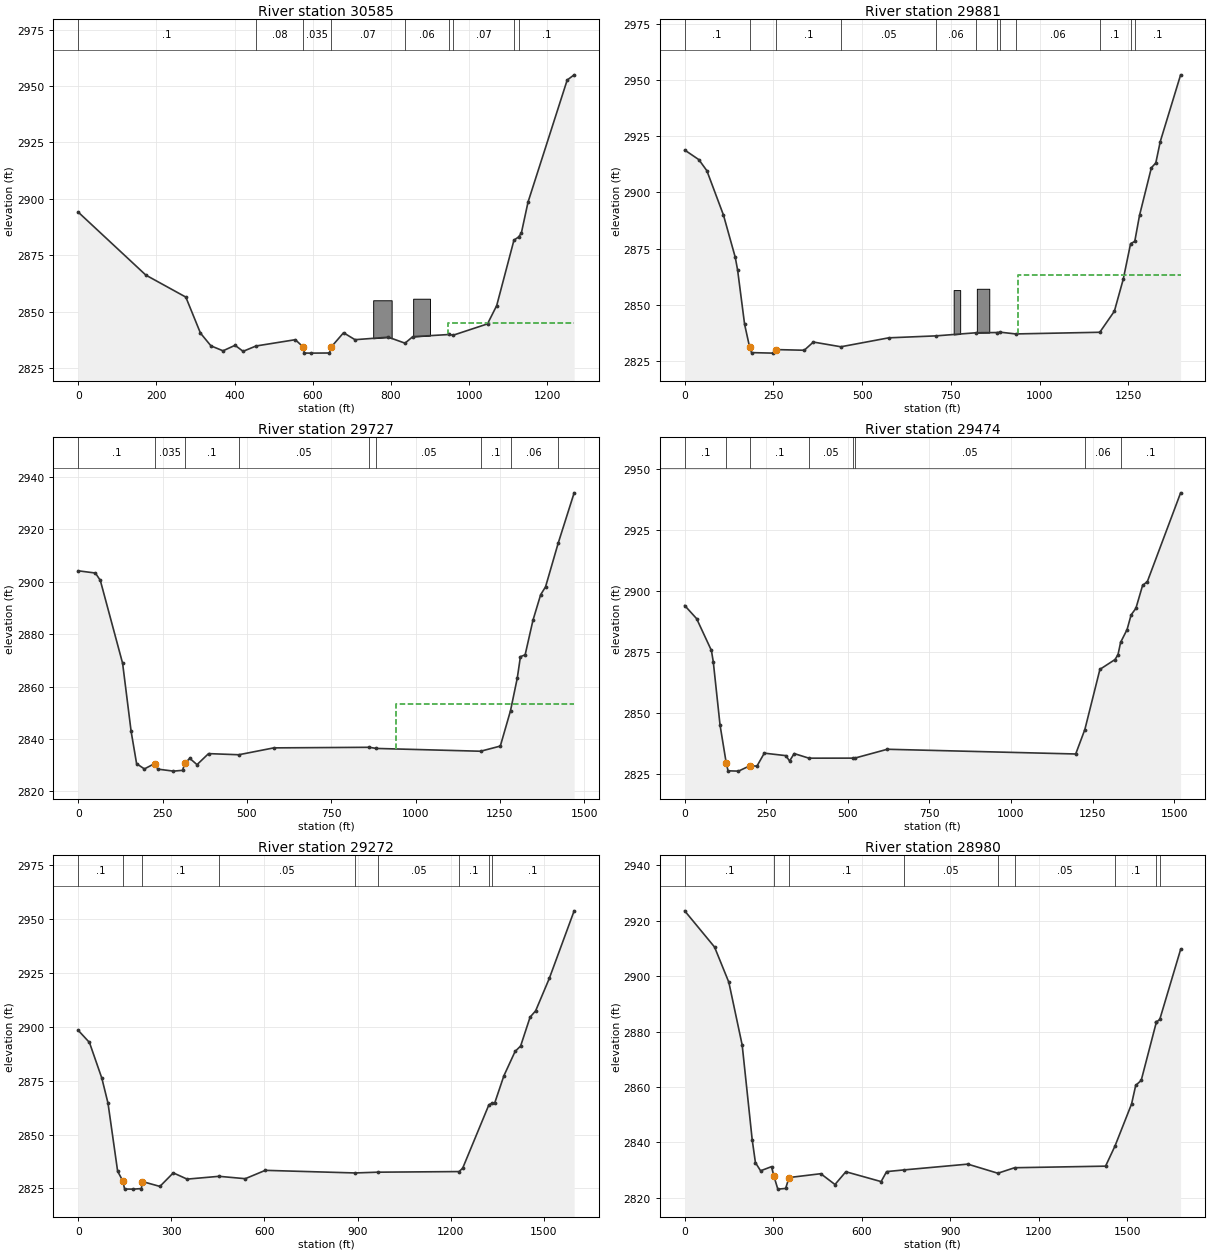
Type RM Length L Ch R = 1 ,30585   ,499.4,703.5,477.2
BEGIN DESCRIPTION:
channel burned 3.21':
lidar invert = 2834.91
effective invert = 2831.70
END DESCRIPTION:
XS GIS Cut Line= 5
2327043.09208632567911.7276649062326984.82985134568190.496905208
2326651.80367573568603.1797770992326513.73688423568770.846375796
2326498.24487081569006.923860771
#Sta/Elev= 30
       0 2894.15   173.1 2866.25   275.3 2856.52   312.8 2840.56   339.6 2834.92
   370.5 2832.73   401.3 2835.16   421.9  2832.5     455 2834.86   555.5 2837.65
  575.05  2834.5   578.8 2831.73   594.4  2831.7   642.7 2831.76  647.86 2834.52
   678.9 2840.72   708.2 2837.65   793.5 2838.76   836.1 2836.11     856 2838.99
   949.8 2839.95   959.2 2839.63  1047.2 2844.65  1070.7 2852.74  1114.9 2881.74
  1126.8 2883.15  1133.8 2884.87  1150.9 2898.59  1251.1 2952.65  1268.9 2954.95
#Mann= 9 ,-1,0
       0      .1       0     455     .08       0  575.05    .035       0
  647.86     .07       0   836.1     .06       0   949.8    .016       0
   959.2     .07       0  1114.9    .016       0  1126.8      .1       0
#XS Ineff= 2 , 0
                           947.2            2845
Permanent Ineff=
       F       F
#Block Obstruct= 2 ,-1
   754.7  801.93 2855.11     857  899.98  2855.8
Bank Sta=575.05,647.86
XS Rating Curve= 0 ,0
Exp/Cntr(USF)=0,0
Exp/Cntr=0.3,0.1

Type RM Length L Ch R = 1 ,29881   ,144,154.1,180
BEGIN DESCRIPTION:
channel burned 0.5':
lidar invert = 2829.19
interpolated invert = 2828.69
END DESCRIPTION:
XS GIS Cut Line= 3
2326690.29904349567767.4435630232326157.46603656568468.962396267
2326012.87818543568964.309664016
#Sta/Elev= 30
       0 2918.85    39.9 2914.58    62.5 2909.67   109.3 2889.95   142.4 2871.26
     149 2865.66   168.8 2841.47     183 2831.27   188.3 2828.92   248.3 2828.69
   258.4 2830.26   336.8 2829.97   362.4 2833.61     440 2831.51   574.8 2835.48
   707.9 2836.35   820.9 2837.73   879.2 2837.83   888.6 2837.99   932.3 2837.21
  1169.2 2837.95  1210.3  2847.3  1235.3  2861.5    1256  2877.3  1267.7 2878.26
  1281.2 2889.88  1314.5 2910.96    1327 2913.12  1339.5 2922.56  1396.9 2952.23
#Mann= 12 ,-1,0
       0      .1       0     183    .035       0   258.4      .1       0
     440     .05       0   707.9     .06       0   820.9     .05       0
   879.2    .016       0   888.6     .07       0   932.3     .06       0
  1169.2      .1       0    1256    .016       0  1267.7      .1       0
#XS Ineff= 2 , 0
                          939.76         2863.37
Permanent Ineff=
       F       F
#Block Obstruct= 2 ,-1
  757.65  775.99 2856.67  822.91  857.95 2857.26
Bank Sta=183,258.4
XS Rating Curve= 0 ,0
Exp/Cntr(USF)=0,0
Exp/Cntr=0.3,0.1

Type RM Length L Ch R = 1 ,29727   ,244.9,253.6,274.6
BEGIN DESCRIPTION:
channel burned 0.54':
lidar invert = 2828.26
interpolated invert = 2827.72
END DESCRIPTION:
XS GIS Cut Line= 3
2326595.95278799567679.3303278822326106.91247946 568222.92493378
2325728.92913342568858.092824543
#Sta/Elev= 30
       0 2904.15    50.9  2903.3    65.5  2900.5   131.6 2868.87   156.9 2842.86
   173.1 2830.56   196.2 2828.56   226.82830.615   236.2 2828.48   282.3 2827.72
   309.2 2828.02   316.32830.725   330.7 2832.61   352.2 2830.19   386.4  2834.4
     476 2833.97   579.8 2836.59   863.2 2836.81   883.7 2836.38    1193 2835.31
  1251.4 2837.28  1281.6 2850.77  1301.7 2863.23    1311 2871.38    1325  2872.1
  1348.2 2885.29    1371 2895.03  1385.5 2898.04  1422.7 2914.58  1470.3  2933.9
#Mann= 9 ,-1,0
       0      .1       0   226.8    .035       0   316.3      .1       0
     476     .05       0   863.2     .06       0   883.7     .05       0
    1193      .1       0  1281.6     .06       0  1422.7      .1       0
#XS Ineff= 2 , 0
       0                  941.82       0  2853.4
Permanent Ineff=
       F       F
Bank Sta=226.8,316.3
XS Rating Curve= 0 ,0
Exp/Cntr(USF)=0,0
Exp/Cntr=0.3,0.1

Type RM Length L Ch R = 1 ,29474   ,203.5,201.1,184.3
BEGIN DESCRIPTION:
channel burned 1.59':
lidar invert = 2827.62
interoplated invert = 2826.03
END DESCRIPTION:
Node Name=O
XS GIS Cut Line= 3
2326382.05194137 567560.471876362325948.53075979567994.840290569
  2325494.975333568779.254755578
#Sta/Elev= 30
       0 2894.06    36.6 2888.66    81.9  2875.6    87.6 2870.99   108.4 2844.93
   127.2 2829.48   132.9 2826.16   164.9 2826.03   199.8 2828.24   221.4 2828.08
     244 2833.41   310.1 2832.39   321.4 2830.18   335.6 2833.24   380.8 2831.35
   516.6 2831.37   520.9 2831.36     621 2835.01  1198.3 2833.07  1226.3 2843.11
  1272.5 2867.84  1318.7 2871.85    1328 2873.91  1335.9 2878.92  1355.7 2884.17
  1368.1 2890.21  1382.7 2892.89  1403.2 2902.29  1417.9  2903.9  1519.8 2940.34
#Mann= 8 ,-1,0
       0      .1       0   127.2    .035       0   199.8      .1       0
   380.8     .05       0   516.6      .1       0   520.9     .05       0
  1226.3     .06       0  1335.9      .1       0
Bank Sta=127.2,199.8
XS Rating Curve= 0 ,0
Exp/Cntr(USF)=0,0
Exp/Cntr=0.3,0.1

Type RM Length L Ch R = 1 ,29272   ,291.3,292.4,230.5
BEGIN DESCRIPTION:
channel burned 2.90':
lidar invert = 2827.6
effective invert = 2824.70
END DESCRIPTION:
XS GIS Cut Line= 3
2326232.43751492567414.0065936022325573.75952645568142.300954833
2325316.71445778568701.909489749
#Sta/Elev= 30
       0 2898.34    36.2  2892.7    76.1 2876.15      96 2864.54     127    2833
  143.52 2828.53   149.5 2824.74     178  2824.7   203.5 2824.95  206.75 2828.21
   263.2 2825.96   306.3 2832.24   350.8 2829.34   453.6 2830.64   538.2 2829.54
   602.7 2833.41   891.7  2832.2   965.3 2832.56  1227.2 2832.84  1238.7 2834.43
  1323.2 2863.83  1332.2 2864.46  1341.3 2864.41  1371.4 2877.25  1407.6 2888.56
  1425.3 2891.05  1455.9 2904.47  1473.7 2907.38  1517.8 2922.44  1597.8 2953.75
#Mann= 9 ,-1,0
       0      .1       0  143.52    .035       0  206.75      .1       0
   453.6     .05       0   891.7     .12       0   965.3     .05       0
  1227.2      .1       0  1323.2    .016       0  1332.2      .1       0
Bank Sta=143.52,206.75
XS Rating Curve= 0 ,0
Exp/Cntr(USF)=0,0
Exp/Cntr=0.3,0.1

Type RM Length L Ch R = 1 ,28980   ,284.6,299.8,285.7
BEGIN DESCRIPTION:
channel burned 3.18':
lidar invert = 2826.25
interpolated invert = 2823.07
END DESCRIPTION:
XS GIS Cut Line= 3
2326131.75402243567089.6747292262325753.54248916567513.532482019
2325181.87793027568467.755833178
#Sta/Elev= 30
       0  2923.6   101.2 2910.52   149.6  2897.8   194.8 2875.14   228.8 2840.89
   239.7 2832.66   257.2 2829.69   294.2 2831.19   302.5 2827.71   315.6 2823.07
   342.1 2823.32   353.5 2827.25   461.1 2828.64   509.3 2824.74   546.1 2829.35
   665.6 2825.79   684.2  2829.4     742    2830   959.3  2832.1  1061.1 2828.81
  1117.9  2830.8  1426.1 2831.37  1458.3 2838.71  1514.2 2853.83  1528.2 2860.54
  1546.9 2862.36  1598.1 2883.36  1598.1 2883.37  1609.8  2884.4  1680.4 2909.66
#Mann= 9 ,-1,0
       0      .1       0   302.5    .035       0   353.5      .1       0
     742     .05       0  1061.1     .12       0  1117.9     .05       0
  1458.3      .1       0  1598.1    .016       0  1609.8      .1       0
Bank Sta=302.5,353.5
XS Rating Curve= 0 ,0
Exp/Cntr(USF)=0,0
Exp/Cntr=0.3,0.1

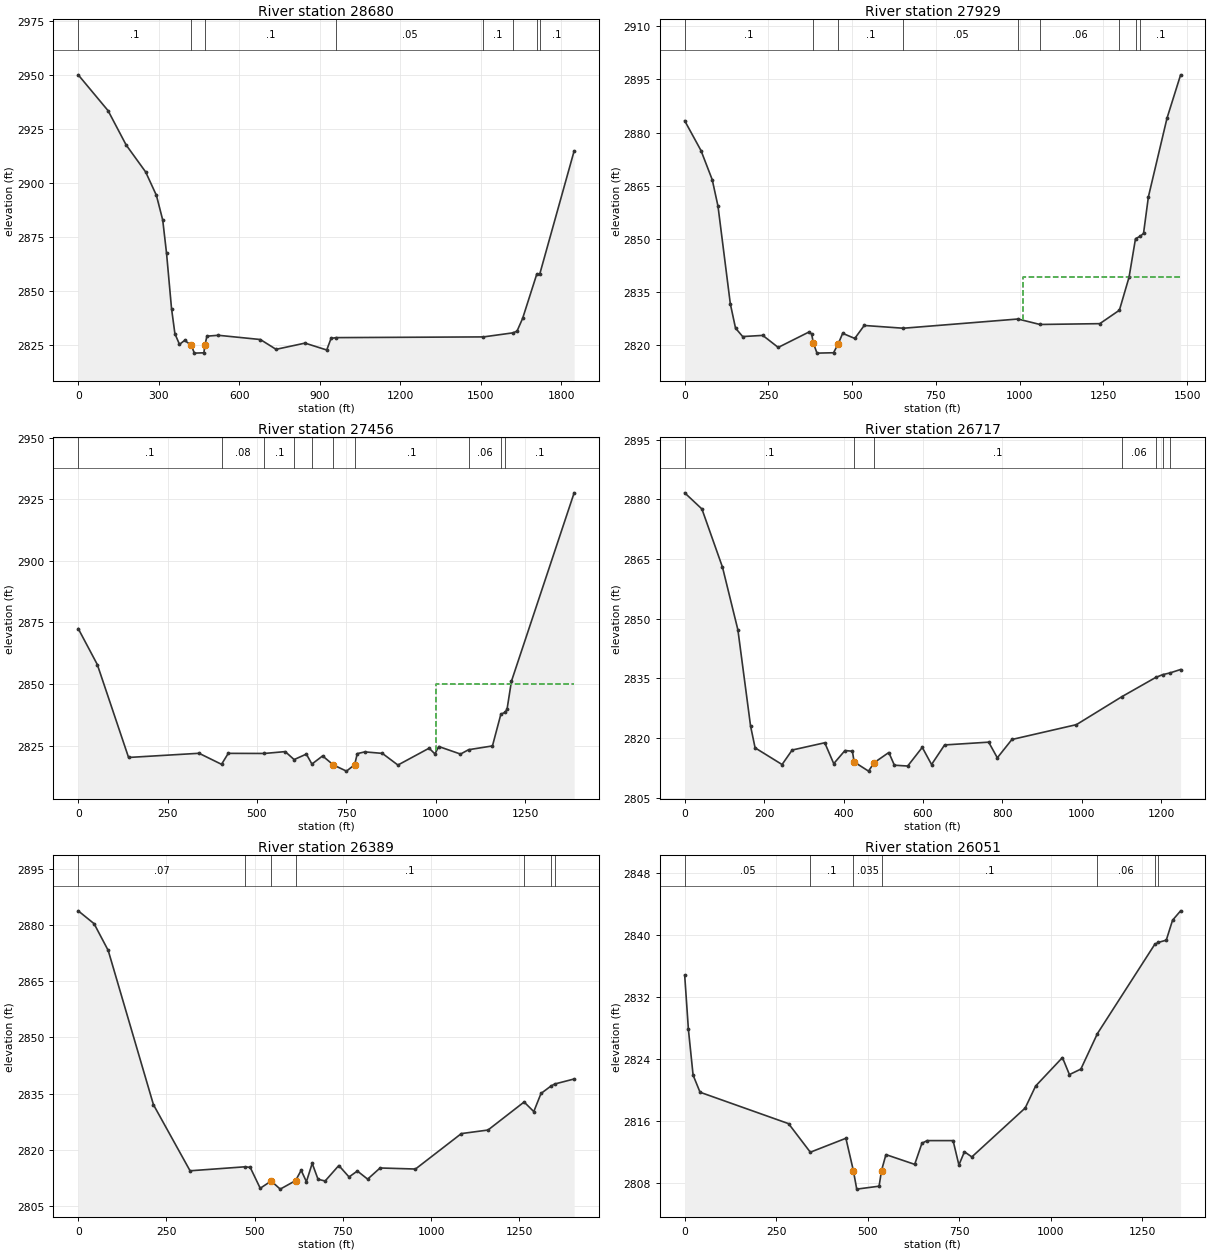
Type RM Length L Ch R = 1 ,28680   ,744.3,751,360.3
BEGIN DESCRIPTION:
channel burned 2.49':
lidar invert = 2823.89
effective invert = 2821.40
END DESCRIPTION:
XS GIS Cut Line= 3
     2326041.915      566851.3362325533.59623447567272.096295274
2324989.36752106568329.261914029
#Sta/Elev= 30
       0 2950.07   111.3  2933.5   178.5 2917.68   251.5 2905.15   291.5 2894.35
   315.1 2882.91   329.3 2867.56   347.9 2842.02   360.5 2830.38   377.6 2825.43
   396.9 2827.31  421.28 2825.01   433.2  2821.4   468.5 2821.55  472.23 2824.98
   479.8 2829.24   522.4 2829.65   679.1 2827.69   737.6 2823.15   845.5 2826.03
   926.5 2822.85   942.6 2828.21   961.7 2828.57  1510.7  2828.9    1621 2830.78
  1635.9 2831.57  1656.7 2837.43  1709.3 2857.82  1720.4 2857.85  1848.9 2914.89
#Mann= 8 ,-1,0
       0      .1       0  421.28    .035       0  472.23      .1       0
   961.7     .05       0  1510.7      .1       0    1621     .06       0
  1709.3    .016       0  1720.4      .1       0
Bank Sta=421.28,472.23
XS Rating Curve= 0 ,0
Exp/Cntr=0.3,0.1

Type RM Length L Ch R = 1 ,27929   ,268.6,473.3,574
BEGIN DESCRIPTION:
channel from lidar
END DESCRIPTION:
XS GIS Cut Line= 4
2325177.12605139566806.9239670212325026.26392954567069.789785396
2325067.40814459567412.6582441472324605.67862014568105.252530824
#Sta/Elev= 30
       0 2883.34    48.7 2874.93    82.3  2866.7    99.5 2859.23   136.3 2831.71
   151.8 2824.86   173.2 2822.48   233.2 2822.81   279.3 2819.42     371 2823.76
     379 2823.24  384.47 2820.54   395.1 2817.81   444.5 2817.92   458.9 2820.51
   471.7 2823.39   507.9 2821.95   536.1 2825.61   653.1 2824.83   995.2 2827.43
  1060.7 2825.89  1239.5 2826.12    1298 2829.91  1326.9 2839.24  1346.1 2850.09
  1360.7 2850.78  1370.1 2851.59  1384.6 2861.88  1440.2 2884.07  1480.8 2896.28
#Mann= 9 ,-1,0
       0      .1       0  384.47    .035       0   458.9      .1       0
   653.1     .05       0   995.2      .1       0  1060.7     .06       0
    1298      .1       0  1346.1    .016       0  1360.7      .1       0
#XS Ineff= 2 , 0
                         1010.67         2839.27
Permanent Ineff=
       F       F
Bank Sta=384.47,458.9
XS Rating Curve= 0 ,0
Exp/Cntr(USF)=0,0
Exp/Cntr=0.3,0.1

Type RM Length L Ch R = 1 ,27456   ,568.6,738.7,809.1
BEGIN DESCRIPTION:
channel burned 0.74':
lidar invert = 2815.34
effective invert = 2814.60
END DESCRIPTION:
Node Name=N
XS GIS Cut Line= 4
2325007.97761174 566624.060789022324580.53493317567200.079799722
2324564.53440509567261.7961222972324153.09225459567707.525118673
#Sta/Elev= 30
       0 2872.52    53.4 2857.92   140.9 2820.15   338.1 2821.85     401 2817.37
   419.8 2821.82     521 2821.78   579.2 2822.53   604.1 2819.29   638.3 2821.52
   653.9 2817.47   683.8 2820.78   713.7 2817.13   750.6  2814.6  773.41 2817.21
   780.8 2821.71     802 2822.42     851 2821.81   894.5 2817.07   981.8 2823.92
     998  2821.6  1008.8  2824.6  1069.6 2821.53  1092.2  2823.3    1159 2824.84
  1182.6 2837.75  1193.9 2838.45  1199.8  2839.7  1212.1  2851.1  1387.6 2927.67
#Mann= 10 ,-1,0
       0      .1       0     401     .08       0     521      .1       0
   604.1     .08       0   653.9      .1       0   713.7    .035       0
  773.41      .1       0  1092.2     .06       0  1182.6    .016       0
  1193.9      .1       0
#XS Ineff= 2 , 0
                         1002.41         2849.85
Permanent Ineff=
       F       F
Bank Sta=713.7,773.41
XS Rating Curve= 0 ,0
Exp/Cntr(USF)=0,0
Exp/Cntr=0.3,0.1

Type RM Length L Ch R = 1 ,26717   ,328.8,328.6,217.3
BEGIN DESCRIPTION:
channel burned 0.63':
lidar invert = 2812.33
effective invert = 2811.70
END DESCRIPTION:
XS GIS Cut Line= 5
2324594.24967152566276.6207508192324306.24016617566576.059204795
2324253.66700249566603.4886814952324058.05795395566722.436543357
2323523.61800857566829.443572839
#Sta/Elev= 30
       0 2881.64    43.4 2877.58    95.2 2862.95     134  2847.2   165.9 2823.03
   177.3 2817.55   245.2 2813.36   270.6    2817   352.7 2818.83   375.3 2813.58
   403.6 2816.88   422.3  2816.7   426.7 2814.01   462.9  2811.7   477.12813.826
     514 2816.38     528 2813.19   561.5 2812.98   598.2 2817.67   621.6 2813.36
   654.4 2818.28   765.4 2818.98   787.2 2815.05   823.9 2819.65   986.3 2823.38
  1101.3 2830.44  1186.3 2835.26  1203.9 2835.96  1220.9 2836.35  1248.7 2837.24
#Mann= 7 ,-1,0
       0      .1       0   426.7    .035       0   477.1      .1       0
  1101.3     .06       0  1186.3    .016       0  1203.9      .1       0
  1220.9     .06       0
Bank Sta=426.7,477.1
XS Rating Curve= 0 ,0
Exp/Cntr(USF)=0,0
Exp/Cntr=0.3,0.1

Type RM Length L Ch R = 1 ,26389   ,335,338.1,306.2
BEGIN DESCRIPTION:
channel burned 0.43':
lidar invert = 2809.91
interpolated invert = 2809.48
END DESCRIPTION:
XS GIS Cut Line= 4
2324601.10704069566093.7575728182324324.52648397566080.042834468
2323883.36906704566548.6297280952323490.21323434566832.067653996
#Sta/Elev= 30
       0 2883.84      45  2880.4      85 2873.25   213.2 2832.03   316.9 2814.38
   473.2 2815.45   487.4 2815.28   515.7 2809.71   546.8 2811.65   572.3 2809.48
   615.9 2811.75   631.7 2814.52   646.6 2811.46     663 2816.36   679.5 2812.12
   699.6 2811.65   738.4 2815.79   767.4 2812.73   790.9 2814.32   820.1 2812.15
   855.3 2815.13   955.6 2814.85  1085.6 2824.32  1161.1 2825.27  1263.4 2832.76
  1290.8  2830.2  1311.3 2835.04  1338.7 2836.97  1350.1 2837.57  1405.2 2838.91
#Mann= 7 ,-1,0
       0     .07       0   473.2      .1       0   546.8    .035       0
   615.9      .1       0  1263.4     .06       0  1338.7    .016       0
  1350.1      .1       0
Bank Sta=546.8,615.9
XS Rating Curve= 0 ,0
Exp/Cntr(USF)=0,0
Exp/Cntr=0.3,0.1

Type RM Length L Ch R = 1 ,26051   ,574.3,494.3,250
BEGIN DESCRIPTION:
channel burned 0.57':
lidar invert = 2807.77
effective invert = 2807.20
END DESCRIPTION:
XS GIS Cut Line= 6
2324150.80646487565677.7438428672323901.65538484566068.613885843
2323837.65327254566112.0438906192323684.50536096566310.907596694
2323675.36220206566475.4844568952323426.21112204566786.351859496
#Sta/Elev= 30
       0 2834.85    10.2 2827.83      23 2821.93      42 2819.72   283.9 2815.66
   343.3 2811.97   440.5 2813.77  460.92  2809.6   470.1  2807.2   531.2 2807.58
  537.85  2809.6   549.9 2811.66   628.5  2810.4   648.3 2813.13   662.5 2813.47
   733.4 2813.47   749.3 2810.32   764.4 2812.03   784.6 2811.36   930.4 2817.68
   958.9 2820.52  1032.2  2824.2  1051.3    2822  1082.5 2822.71  1127.8  2827.3
  1284.6 2838.84  1294.4 2839.08  1315.9 2839.37  1333.1 2841.95  1355.1 2843.16
#Mann= 7 ,-1,0
       0     .05       0   343.3      .1       0  460.92    .035       0
  537.85      .1       0  1127.8     .06       0  1284.6    .016       0
  1294.4      .1       0
Bank Sta=460.92,537.85
XS Rating Curve= 0 ,0
Exp/Cntr(USF)=0,0
Exp/Cntr=0.3,0.1

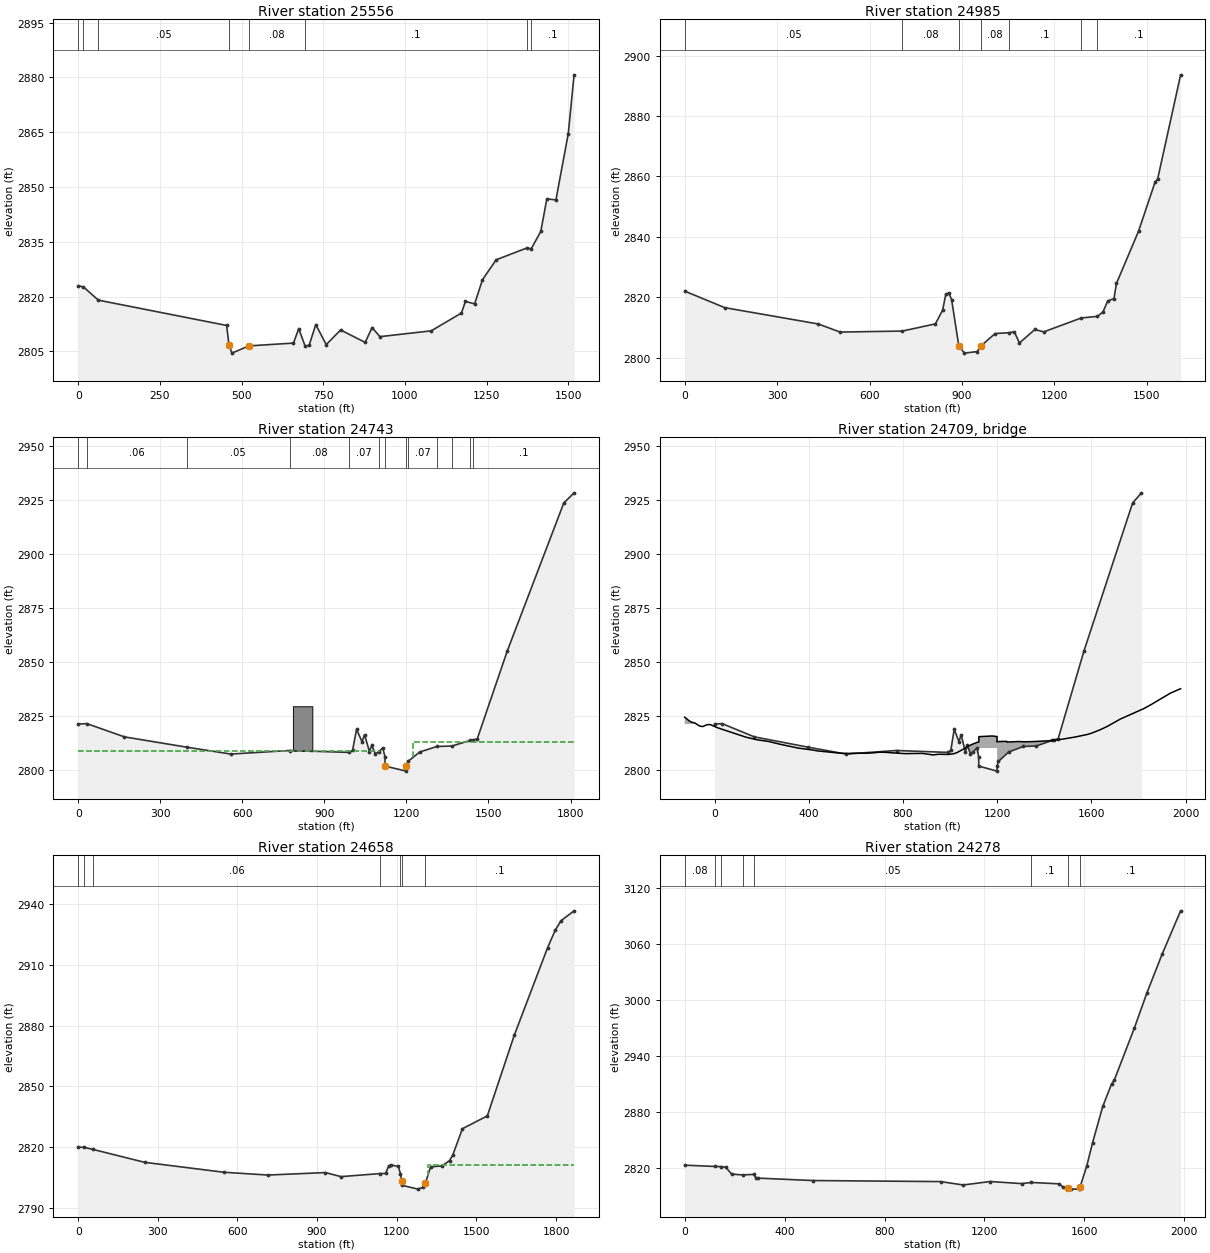
Type RM Length L Ch R = 1 ,25556   ,299.5,571.2,380.2
BEGIN DESCRIPTION:
channel burned 0.62':
lidar invert = 2805.17
interpolated invert = 2804.55
END DESCRIPTION:
Node Name=M
XS GIS Cut Line= 4
 2323508.0275423565315.8762205862323442.96300929566250.877657872
2323407.86307031566552.991245313 2323262.6215857566788.094343742
#Sta/Elev= 30
       0 2822.98    16.1 2822.66    61.5 2819.05   454.4 2812.12  461.332806.835
   470.4 2804.55   522.6 2806.53   658.9  2807.3   674.9 2811.23     695 2806.37
     707 2806.76   727.1 2812.35   759.1 2806.89   803.2 2810.88   878.3 2807.49
   899.5 2811.54   923.5 2809.06  1080.5 2810.65  1173.1 2815.53  1185.2  2818.7
  1213.4 2818.03  1237.4 2824.63  1279.2 2830.09  1373.3 2833.32  1386.6 2833.11
  1415.9 2837.85  1434.4 2846.77  1462.2 2846.47    1500 2864.63  1517.8  2880.7
#Mann= 8 ,-1,0
       0    .016       0    16.1     .06       0    61.5     .05       0
  461.33    .035       0   522.6     .08       0     695      .1       0
  1373.3    .016       0  1386.6      .1       0
Bank Sta=461.33,522.6
XS Rating Curve= 0 ,0
Exp/Cntr(USF)=0,0
Exp/Cntr=0.3,0.1

Type RM Length L Ch R = 1 ,24985   ,71.8,242.2,236.1
BEGIN DESCRIPTION:
structure xs 4 - channel burned 0.12':
lidar invert = 2801.58
interpolated invert = 2801.46
END DESCRIPTION:
XS GIS Cut Line= 4
2323435.43265832565291.0371094472322991.69683221566000.832072593
2323094.64987591566367.5114865582323154.14666139566755.018985083
#Sta/Elev= 30
       0    2822   129.9 2816.53   433.5 2811.12   504.2 2808.44   706.4 2808.77
   813.9 2811.16   837.1 2815.66   847.5  2820.9   857.2 2821.41   866.5 2819.19
   889.7 2803.92   908.1 2801.46   949.6 2801.98   962.1 2803.89  1007.8 2807.95
  1053.5 2808.23  1070.1 2808.54  1086.7 2804.82  1136.6 2809.29  1165.7 2808.51
  1287.4 2813.11    1340 2813.65  1357.6 2815.08  1373.4 2818.74  1393.6 2819.54
  1401.7 2824.55  1473.3 2841.84  1527.2 2858.18  1535.3  2859.1    1610 2893.68
#Mann= 7 ,-1,0
       0     .05       0   706.4     .08       0   889.7    .035       0
   962.1     .08       0  1053.5      .1       0  1287.4    .016       0
    1340      .1       0
Bank Sta=889.7,962.1
XS Rating Curve= 0 ,0
Exp/Cntr(USF)=0,0
Exp/Cntr=0.5,0.3

Type RM Length L Ch R = 1 ,24743   ,94.5,85.2,80.2
BEGIN DESCRIPTION:
structure xs 3
channel burned per surveyed cross section data
END DESCRIPTION:
XS GIS Cut Line= 6
2323418.32952355565250.5439322992322813.20259105566118.071039059
2322805.16993266566174.2996478312322853.36588303 566372.43855493
2322931.01491419566434.0222692992323056.85989573566808.879661109
#Sta/Elev= 30
       0 2821.42    31.7 2821.61     169 2815.48     397 2810.73   557.9 2807.55
   772.9 2809.19   991.7 2808.31    1003  2809.2  1017.6 2818.97  1037.7 2813.28
  1046.9 2816.46  1064.9 2808.66    1073 2811.59  1086.1 2807.79  1097.9 2808.42
  1113.4 2810.42  1121.6 2806.34 1121.72    2802 1199.25 2799.66 1199.53 2802.02
  1205.5 2804.13  1248.5 2808.48  1311.4 2811.05  1366.5 2811.27  1433.4 2813.84
  1443.1 2814.06  1458.9 2814.57  1568.6 2855.14  1775.3 2923.56    1813 2928.26
#Mann= 13 ,-1,0
       0    .016       0    31.7     .06       0     397     .05       0
   772.9     .08       0   991.7     .07       0  1097.9      .1       0
 1121.72    .035       0 1199.53      .1       0  1205.5     .07       0
  1311.4      .1       0  1366.5     .06       0  1433.4    .016       0
  1443.1      .1       0
#XS Ineff= 2 , 0
       0    1098 2809.11    1224       0 2813.12
Permanent Ineff=
       F       F
#Block Obstruct= 1 ,-1
  784.98  855.97 2829.64
Bank Sta=1121.72,1199.53
XS Rating Curve= 0 ,0
Exp/Cntr(USF)=0,0
Exp/Cntr=0.5,0.3

Type RM Length L Ch R = 3 ,24709   ,,,
BEGIN DESCRIPTION:
Bridge 54075EFG040
JV notes: road deck updated per surveyed XS data points
channel burned per surveyed cross sections
structure opening based on survey data, photos, and aerial imagery
surveyed inverts are approximately 1' below inverts from lidar:
 surveyed invert US is 2799.78
 surveyed invert DS is 2799.21
END DESCRIPTION:
Bridge Culvert--1,0,-1,-1, 0
Deck Dist Width WeirC Skew NumUp NumDn MinLoCord MaxHiCord MaxSubmerge Is_Ogee
24,20,2.6,0, 60, 60, , , 0.98, 0, 0,0,,
    -127-107.322 -97.982  -83.65 -68.277 -59.977 -50.508 -34.206 -26.836 -17.367
  12.175 133.124 179.017  230.24 276.539 353.989  414.23 437.178 534.652 566.005
 600.707 640.114 674.395 695.896 720.131 808.695 882.261 927.087 951.094 993.489
1016.754 1029.171062.152    1066 1093.38 1119.69 1122.18 1122.18 1180.05 1199.69
 1199.69 1200.62 1239.641239.9781244.6581290.8181314.7831351.9311418.821 1479.63
1533.5191583.5051600.7241635.1871667.7941723.1291823.2291849.6781935.8221979.247
2824.5672822.8232822.3112821.886 2820.792820.3782820.2622821.0382821.1712821.112
2819.7062815.344 2814.172813.3442812.1142810.3142809.4542808.9972807.9442807.827
2807.958 2807.922808.1122808.3752808.3772807.7422807.864 2807.152807.4592807.369
2807.7472808.218 2810.13 2810.55 2812.04 2813.15 2813.09 2815.59 2815.91 2815.62
 2813.12  2813.3 2813.432813.172 2813.132813.3312813.2262813.2962813.6812814.469
2815.4742816.6182817.1932818.6582820.3322823.7222828.5722830.1362835.6932837.749
                                                                                
                                                                                
                                                                                
                                                 2810.33 2810.33 2810.34 2810.35
 2810.35
                                                                                
     -29  -9.322    .018   14.35  29.723  38.023  47.492  63.794  71.164  80.633
 110.175 231.124 277.017  328.24 374.539 451.989  512.23 535.178 632.652 664.005
 698.707 738.114 772.395 793.896 818.131 906.695 980.2611025.0871049.0941091.489
1114.754 1127.171160.152    1164 1191.38 1217.69 1220.18 1220.18 1278.05 1297.69
 1297.69 1298.62 1337.641337.9781342.6581388.8181412.7831449.9311516.821 1577.63
1631.5191681.5051698.7241733.1871765.7941821.1291921.2291947.6782033.8222077.247
2824.5672822.8232822.3112821.886 2820.792820.3782820.2622821.0382821.1712821.112
2819.7062815.344 2814.172813.3442812.1142810.3142809.4542808.9972807.9442807.827
2807.958 2807.922808.1122808.3752808.3772807.7422807.864 2807.152807.4592807.369
2807.7472808.218 2810.13 2810.55 2812.04 2813.15 2813.09 2815.59 2815.91 2815.62
 2813.12  2813.3 2813.432813.172 2813.132813.3312813.2262813.2962813.6812814.469
2815.4742816.6182817.1932818.6582820.3322823.7222828.5722830.1362835.6932837.749
                                                                                
                                                                                
                                                                                
                                                 2810.33 2810.33 2810.34 2810.35
 2810.35
                                                                                
BR Coef=-1 ,-1 , 0 ,, 0 ,,,0.8,0,0.2,0,
WSPro=,,,, 1 ,,,, 0 ,,,, 0 ,,,,-1 ,-1 ,-1 , 0 , 0 , 0 , 0 , 0
BC Design=,, 0 ,, 0 ,,,,,,
BC Use User HTab Curves=0
BC User HTab FreeFlow(D)= 0

Type RM Length L Ch R = 1 ,24658   ,305.8,379.6,404.9
BEGIN DESCRIPTION:
structure xs 2
channel burned per surveyed cross section data
END DESCRIPTION:
XS GIS Cut Line= 6
2323356.74580918565196.992876326 2322722.1657959566093.973063871
 2322724.8433487566206.4302814142322797.13727426  566431.3447165
2322872.10875262566487.5733252722322981.88841737566795.491897116
#Sta/Elev= 30
       0 2819.93    20.6 2819.91    55.1 2818.86   250.2 2812.47   548.1 2807.56
   715.1 2806.17   931.2  2807.4     990 2805.39    1138 2806.91    1158 2806.95
    1170 2810.81  1178.1 2811.15    1206 2810.42  1214.1 2806.78  1218.3 2803.42
 1219.08 2801.14 1279.63 2799.21  1298.2 2800.06 1308.06 2802.25  1327.6 2810.25
  1369.6 2810.65    1399 2813.31  1411.6 2816.27  1447.5 2829.09  1541.2 2835.41
  1642.7 2875.27  1768.1 2918.51  1797.7 2927.38  1818.9 2931.92  1868.1  2936.8
#Mann= 7 ,-1,0
       0     .06       0    20.6    .016       0    55.1     .06       0
    1138      .1       0  1214.1     .05       0  1218.3    .035       0
 1308.06      .1       0
#XS Ineff= 2 , 0
            1207  2806.3    1316          2811.1
Permanent Ineff=
       F       F
Bank Sta=1218.3,1308.06
XS Rating Curve= 0 ,0
Exp/Cntr(USF)=0,0
Exp/Cntr=0.5,0.3

Type RM Length L Ch R = 1 ,24278   ,220,224.2,224.4
BEGIN DESCRIPTION:
channel burned 1.09':
lidar invert = 2798.81
interpolated invert = 2797.72
END DESCRIPTION:
XS GIS Cut Line= 2
2323175.30273009564835.1999228072322174.12683054566549.542216562
#Sta/Elev= 30
       0 2823.32   122.7 2821.95     147 2821.76   164.6 2821.04   187.6 2813.78
   231.8 2812.92   275.6 2813.44   284.9 2810.03   294.1 2809.48   511.8 2806.91
  1024.3 2805.77    1115 2802.17  1223.2 2805.86  1348.9 2803.62  1386.9 2804.84
  1498.5 2803.39  1512.4 2800.33  1535.5 2799.42    1545 2797.78    1577 2797.72
  1582.9 2800.07  1609.7 2822.67  1632.8  2847.3  1673.5 2886.09  1708.6 2909.92
  1720.3 2914.64  1799.6 2969.56  1850.5 3007.53  1910.7 3048.48  1985.3 3095.15
#Mann= 8 ,-1,0
       0     .08       0   122.7     .05       0     147     .07       0
   231.8    .016       0   275.6     .05       0  1386.9      .1       0
  1535.5    .035       0  1582.9      .1       0
Bank Sta=1535.5,1582.9
XS Rating Curve= 0 ,0
Exp/Cntr(USF)=0,0
Exp/Cntr=0.3,0.1