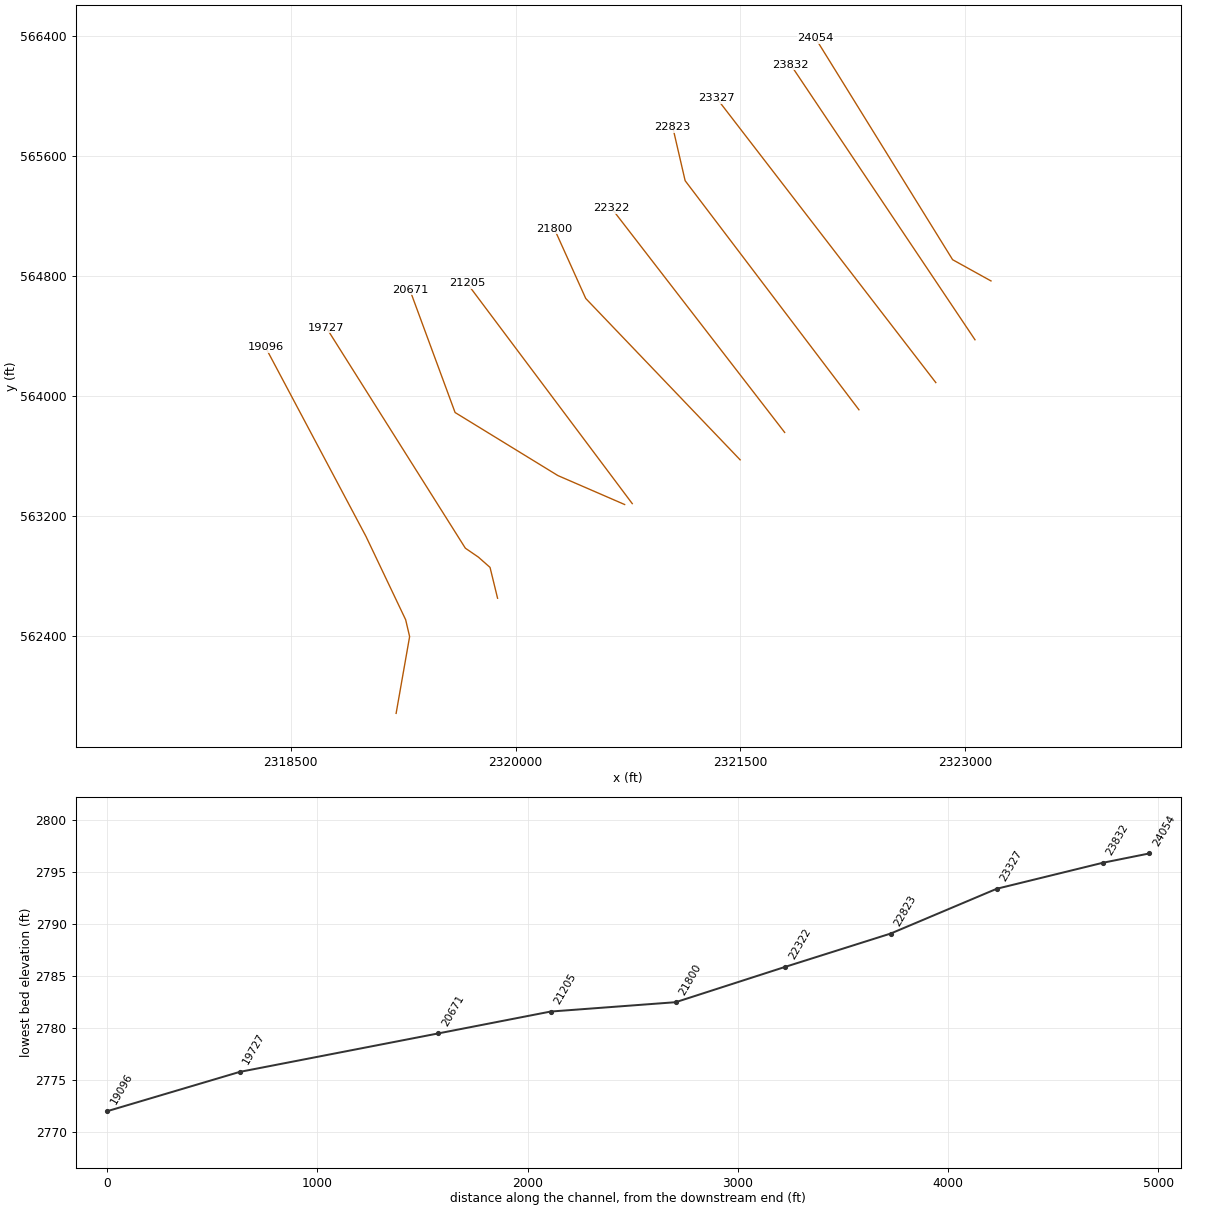
HEC-RAS study EFGRNBRRRV.prj: EFGRNBRRRV

--- EFGRNBRRRV.g01 (geometry) --- (continued)

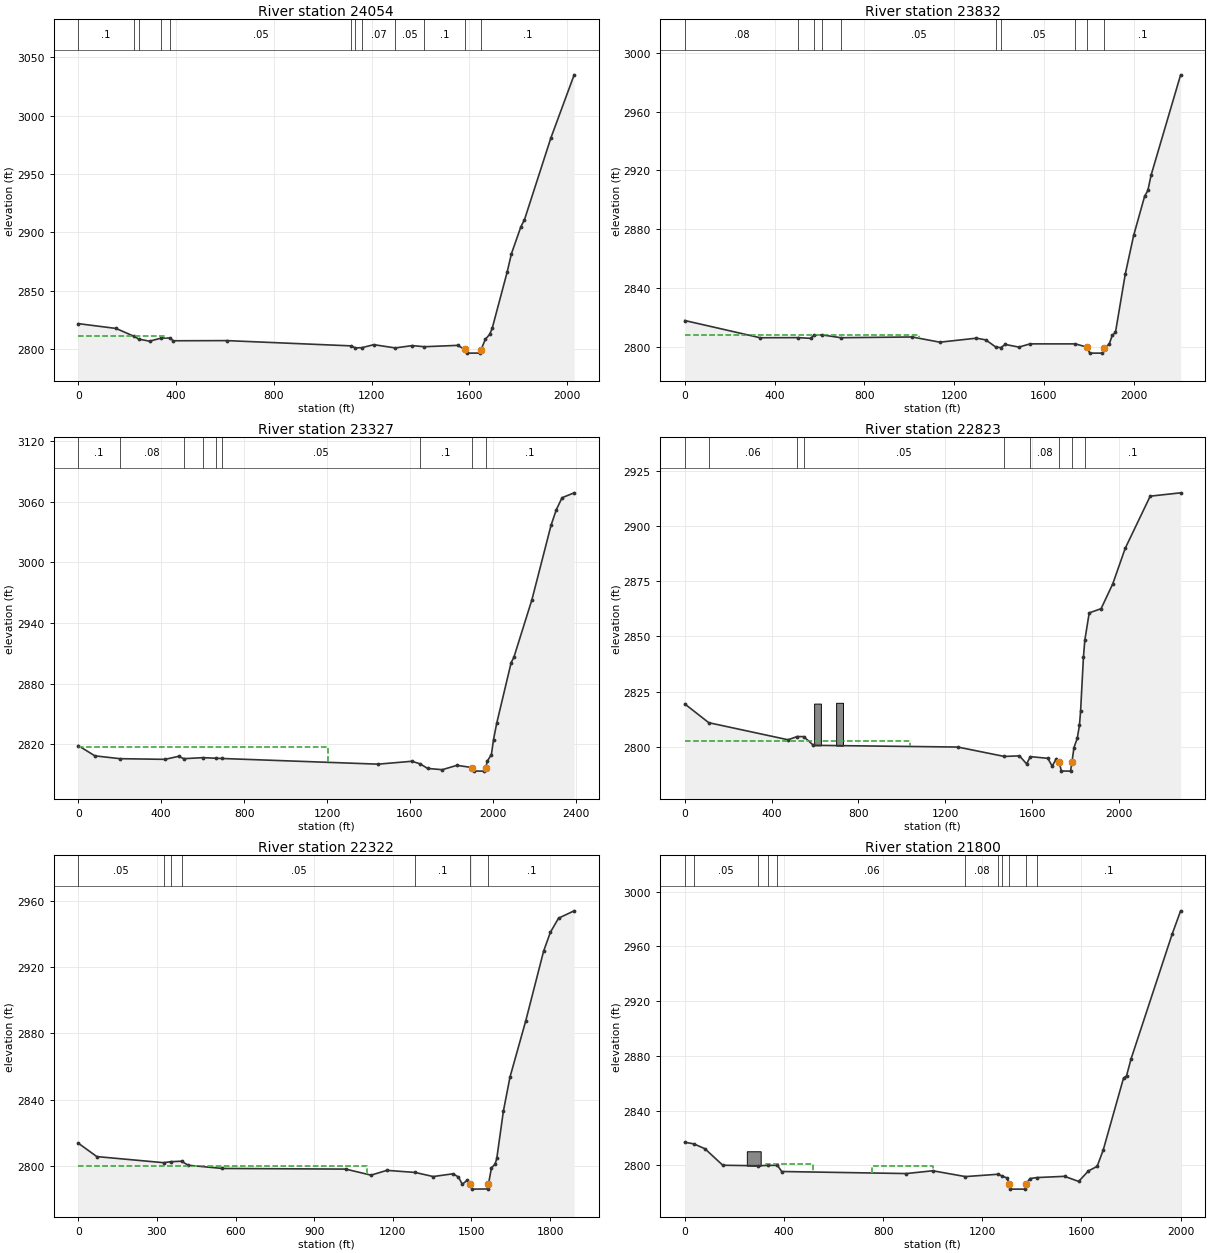
Type RM Length L Ch R = 1 ,24054   ,220,222,223.2
BEGIN DESCRIPTION:
channel burned 1.33':
lidar invert = 2798.13
interpolated invert = 2796.80
END DESCRIPTION:
XS GIS Cut Line= 3
 2323171.3455677564767.999532315 2322915.3371185564909.718495265
 2322001.0212285 566386.33865762
#Sta/Elev= 30
       0 2822.03   154.5 2817.91   227.7 2811.21   247.5 2808.82   291.6    2807
     339 2809.66   376.7  2809.7   387.5 2807.37   607.2 2807.51  1116.8    2803
  1134.2 2801.27  1160.4 2801.46  1209.4 2804.03    1297 2801.24  1366.7 2803.23
  1416.1 2802.28  1552.8 2803.44  1581.7 2799.95  1590.3  2796.8  1642.7 2796.84
  1648.62799.845  1665.8 2808.64  1683.4 2812.78    1694 2818.09  1755.2 2866.16
  1772.7 2881.86  1811.6 2905.04  1825.8 2910.77  1933.9 2980.72  2029.4 3034.83
#Mann= 12 ,-1,0
       0      .1       0   227.7     .05       0   247.5     .07       0
     339    .016       0   376.7     .05       0  1116.8     .07       0
  1134.2     .04       0  1160.4     .07       0    1297     .05       0
  1416.1      .1       0  1581.7    .035       0  1648.6      .1       0
#XS Ineff= 2 , 0
          360.06 2811.84
Permanent Ineff=
       F       F
Bank Sta=1581.7,1648.6
XS Rating Curve= 0 ,0
Exp/Cntr(USF)=0,0
Exp/Cntr=0.3,0.1

Type RM Length L Ch R = 1 ,23832   ,518.9,504.7,506.8
BEGIN DESCRIPTION:
channel burned 1.68':
lidar invert = 2797.58
effective invert = 2795.90
END DESCRIPTION:
Node Name=L
XS GIS Cut Line= 2
2323064.60663464564375.5769032822321835.10340921566210.259414535
#Sta/Elev= 30
       0 2818.05   335.9 2806.35     506 2806.44   560.5 2805.94   575.6 2808.06
   611.5 2808.28   695.3 2806.38  1013.4 2806.87    1136 2803.33  1298.8 2806.06
  1340.5 2804.91  1385.3 2800.05  1407.9 2799.67  1427.2 2801.81  1488.1 2799.99
    1538 2802.19    1740 2802.181793.043 2799.91  1803.4  2795.9  1860.6  2795.9
 1866.842799.649  1889.9 2801.79  1903.9 2807.92  1918.4 2810.03  1961.9 2849.49
  1999.4 2875.89  2048.4 2902.58  2062.6 2906.43  2077.1 2916.85  2208.6 2985.01
#Mann= 10 ,-1,0
       0     .08       0     506     .06       0   575.6    .016       0
   611.5     .06       0   695.3     .05       0  1385.3     .04       0
  1407.9     .05       0    1740      .1       01793.043    .035       0
 1866.84      .1       0
#XS Ineff= 2 , 0
            1045 2808.32
Permanent Ineff=
       F       F
Bank Sta=1793.043,1866.84
XS Rating Curve= 0 ,0
Exp/Cntr(USF)=0,0
Exp/Cntr=0.3,0.1

Type RM Length L Ch R = 1 ,23327   ,508.5,503.8,503.6
BEGIN DESCRIPTION:
channel burned 0.44':
lidar invert = 2793.84
effective invert = 2793.40
END DESCRIPTION:
XS GIS Cut Line= 2
2322803.17354002564089.9249698812321342.56591908565985.477204278
#Sta/Elev= 30
       0 2818.62    79.9 2808.51   201.5 2805.71   418.2 2805.06   483.8 2808.03
   509.1 2805.72   601.3 2806.73   666.1 2806.13   694.7  2805.9  1446.7  2800.3
  1610.2 2803.16  1649.8 2800.59  1685.7 2796.08  1756.4 2794.81  1827.1 2799.13
1900.4052796.947    1912  2793.5  1958.4  2793.41966.8052796.941  1973.5 2803.22
  1993.7 2809.84  2003.8 2824.59    2019 2840.56  2088.9 2900.79    2102 2905.98
  2189.2 2963.07  2281.5 3036.71  2306.8 3052.02  2334.6 3063.91    2393 3068.76
#Mann= 9 ,-1,0
       0      .1       0   201.5     .08       0   509.1     .04       0
   601.3     .08       0   666.1    .016       0   694.7     .05       0
  1649.8      .1       01900.405    .035       01966.805      .1       0
#XS Ineff= 2 , 0
         1207.04 2816.83
Permanent Ineff=
       F       F
Bank Sta=1900.405,1966.805
XS Rating Curve= 0 ,0
Exp/Cntr(USF)=0,0
Exp/Cntr=0.3,0.1

Type RM Length L Ch R = 1 ,22823   ,498.2,501.1,501.1
BEGIN DESCRIPTION:
channel burn 1.11':
lidar invert = 2790.21
effective invert = 2789.10
END DESCRIPTION:
XS GIS Cut Line= 3
2322290.40231107563908.6459846182321131.00619178565436.744161593
2321048.36567331565793.751201412
#Sta/Elev= 30
       0 2819.49   110.5 2811.01   475.9 2803.28   517.8 2804.75     548  2804.7
   592.7 2800.78  1258.1 2799.99  1472.3 2795.74  1542.1 2796.01    1575 2792.36
  1591.9 2795.66  1672.7  2794.9  1692.7 2791.34  1712.1 2794.77  1725.2 2793.19
  1734.9 2789.16  1777.2  2789.1  1783.9 2793.21  1793.2 2799.78  1808.2 2803.89
  1818.3 2809.76  1823.6 2816.12  1836.8 2840.64  1843.2 2848.35  1863.4 2860.69
  1918.1 2862.58    1972 2873.84  2029.4 2889.92  2144.4 2913.48  2284.6 2914.99
#Mann= 9 ,-1,0
       0    .016       0   110.5     .06       0   517.8    .016       0
     548     .05       0  1472.3      .1       0  1591.9     .08       0
  1725.2    .035       0  1783.9     .08       0  1843.2      .1       0
#XS Ineff= 2 , 0
         1037.98  2802.6
Permanent Ineff=
       F       F
#Block Obstruct= 2 ,-1
  595.91  627.02 2819.65  697.24  729.06 2820.01
Bank Sta=1725.2,1783.9
XS Rating Curve= 0 ,0
Exp/Cntr(USF)=0,0
Exp/Cntr=0.3,0.1

Type RM Length L Ch R = 1 ,22322   ,490.5,521.8,483.8
BEGIN DESCRIPTION:
channel burned 2.02':
lidar invert = 2787.92
effective invert = 2785.90
END DESCRIPTION:
XS GIS Cut Line= 2
2321794.98798886563757.3970508252320638.46870166565254.935020945
#Sta/Elev= 30
       0 2813.63    70.5 2805.55   325.3 2801.87   352.6 2802.46   393.9 2802.75
   419.2 2800.31   549.4 2798.38  1019.9    2798  1117.1 2794.34  1177.3 2797.23
  1285.1 2795.98  1354.2  2793.5    1430 2795.16  1450.2 2793.23  1465.4 2788.82
  1484.7 2791.39 1493.49 2788.95  1501.8  2785.9  1561.7 2786.01 1565.22 2788.99
  1576.6 2798.82  1590.2 2800.87  1596.8 2804.41  1622.1 2833.06  1647.3 2853.59
  1707.2 2887.41  1775.6 2929.62  1801.3 2940.95  1832.6 2949.51  1892.1 2953.93
#Mann= 7 ,-1,0
       0     .05       0   325.3     .06       0   352.6    .016       0
   393.9     .05       0  1285.1      .1       0 1493.49    .035       0
 1565.22      .1       0
#XS Ineff= 2 , 0
         1101.55    2800
Permanent Ineff=
       F       F
Bank Sta=1493.49,1565.22
XS Rating Curve= 0 ,0
Exp/Cntr(USF)=0,0
Exp/Cntr=0.3,0.1

Type RM Length L Ch R = 1 ,21800   ,621.1,594.9,594.2
BEGIN DESCRIPTION:
channel burned to maintain the upstream and downstream section' There seems to be 9.59 feet burn based on effective which doesnt make sense:
lidar invert = 2785.29
effective invert = 2775.70 (effective xs AM)
c/e of 0.3/0.5 to correct drawdown in 101
END DESCRIPTION:
Node Name=K
XS GIS Cut Line= 3
2321498.03146056563574.4796423192320468.07511406 564650.85441157
2320258.32231667565116.098949904
#Sta/Elev= 30
       0 2816.81      37 2815.58    81.2 2812.04   153.2 2799.97   297.2 2799.58
   335.9 2799.89   373.8 2799.88   390.8 2795.39   893.7 2793.89  1000.3 2795.93
    1132 2791.67    1264 2793.39  1281.3 2791.99    1299 2790.72 1309.02 2786.54
 1312.38  2782.5 1372.69  2782.5 1375.84 2786.06  1392.3 2790.24  1420.2 2790.96
  1531.8 2791.86  1588.8 2788.13  1628.3 2795.84  1663.4 2799.15    1688  2811.2
  1769.7 2863.68  1781.9 2865.39  1799.9  2877.6    1966 2969.09  2000.1 2986.07
#Mann= 11 ,-1,0
       0     .06       0      37     .05       0   297.2     .07       0
   335.9    .016       0   373.8     .06       0    1132     .08       0
    1264      .1       0  1281.3     .08       0 1309.02    .035       0
 1375.84     .08       0  1420.2      .1       0
#XS Ineff= 2 ,-1
  326.98  519.07 2800.59  756.02 1002.352799.176
Permanent Ineff=
       F       F
#Block Obstruct= 1 ,-1
  250.16  306.15 2810.19
Bank Sta=1309.02,1375.84
XS Rating Curve= 0 ,0
Exp/Cntr(USF)=0,0
Exp/Cntr=0.5,0.3

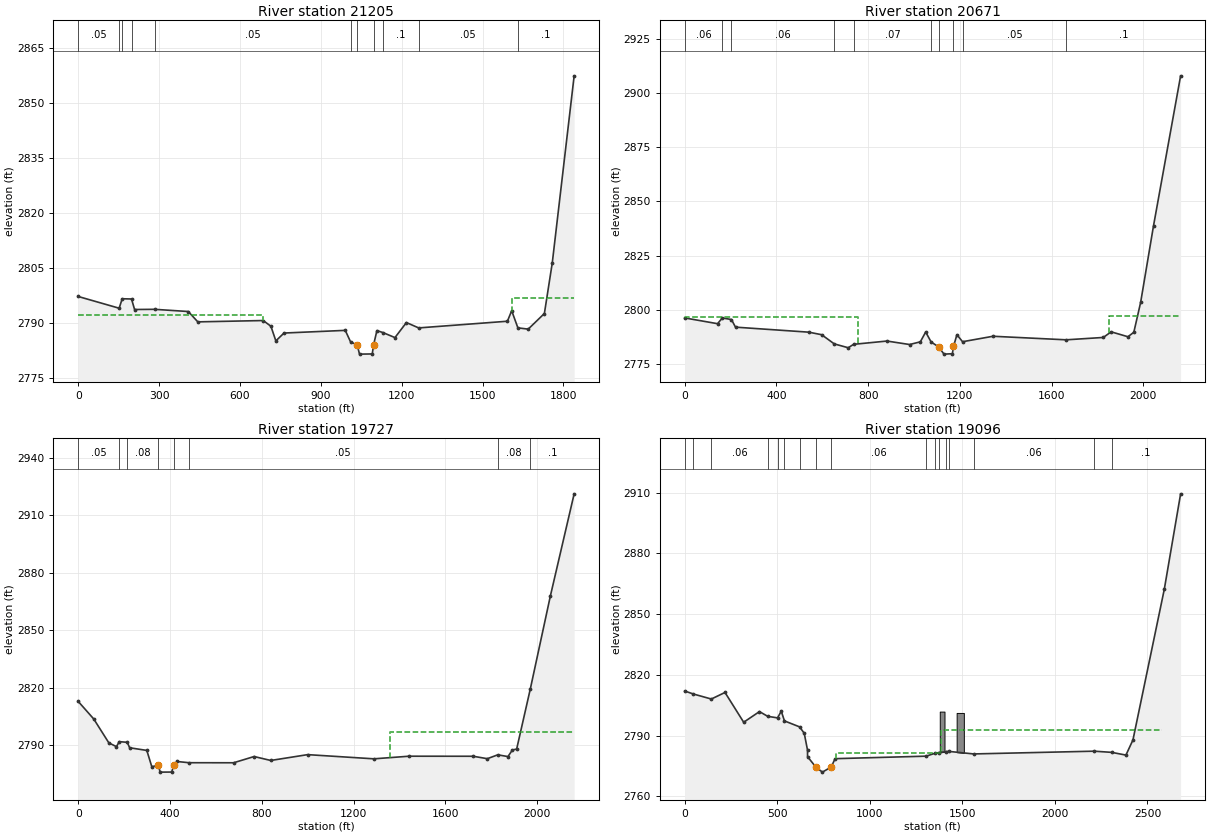
Type RM Length L Ch R = 1 ,21205   ,443.6,533.9,518.2
BEGIN DESCRIPTION:
channel burned 1.34':
lidar invert = 2782.94
effective invert = 2781.60
END DESCRIPTION:
XS GIS Cut Line= 2
 2320778.2689015563282.5565367932319675.03741192564754.600107994
#Sta/Elev= 30
       0 2797.32   151.9 2794.12   163.2  2796.7   197.7 2796.64   209.1 2793.77
   283.2 2793.82   408.2 2793.22   443.7  2790.4   686.3 2790.76   714.8  2789.2
   733.1 2785.21   763.4 2787.35   990.6 2788.08  1010.6 2784.89  1034.8 2784.13
  1043.4  2781.6  1090.7 2781.651095.8442784.201    1108 2788.02  1130.7 2787.47
  1174.9 2786.11  1217.4 2790.21  1262.9 2788.75    1592 2790.57  1607.9 2793.44
  1630.9 2788.76  1669.2 2788.42  1729.2 2792.68  1758.4 2806.45  1839.6  2857.5
#Mann= 11 ,-1,0
       0     .05       0   151.9     .06       0   163.2    .016       0
   197.7     .06       0   283.2     .05       0  1010.6     .08       0
  1034.8    .035       01095.844     .08       0  1130.7      .1       0
  1262.9     .05       0  1630.9      .1       0
#XS Ineff= 2 , 0
          684.01 2792.28 1609.01         2796.85
Permanent Ineff=
       F       F
Bank Sta=1034.8,1095.844
XS Rating Curve= 0 ,0
Exp/Cntr=0.3,0.1

Type RM Length L Ch R = 1 ,20671   ,751.5,944.5,555.4
BEGIN DESCRIPTION:
channel burned 1.34':
lidar invert = 2780.84
effective invert = 2779.50
END DESCRIPTION:
XS GIS Cut Line= 4
2320727.50570009563276.5022289682320282.10735529563469.670968511
2319596.37043779563890.2562779122319294.64619409564708.568999465
#Sta/Elev= 30
       0 2796.22   143.2 2793.56   164.2 2796.19   203.8 2795.49   221.6 2791.96
   541.4 2789.64   597.1 2788.47   652.3 2784.22     713 2782.45   736.4 2784.03
   881.9 2785.54   980.5 2783.94  1027.4 2785.18  1050.7 2789.72  1074.3 2785.12
1107.1722782.832  1130.6  2779.5  1167.1 2779.691171.8622783.027  1186.9 2788.47
  1211.4 2785.23  1344.2 2787.75    1663 2786.11    1825  2787.2  1859.2  2789.8
  1932.5 2787.53  1958.1  2789.6  1987.9 2803.44  2044.1 2838.87  2162.1 2908.04
#Mann= 10 ,-1,0
       0     .06       0   164.2    .016       0   203.8     .06       0
   652.3     .04       0   736.4     .07       0  1074.3     .08       0
1107.172    .035       01171.862     .08       0  1211.4     .05       0
    1663      .1       0
#XS Ineff= 2 , 0
          753.76 2796.63  1850.7          2797.3
Permanent Ineff=
       F       F
Bank Sta=1107.172,1171.862
XS Rating Curve= 0 ,0
Exp/Cntr(USF)=0,0
Exp/Cntr=0.3,0.1

Type RM Length L Ch R = 1 ,19727   ,647.9,630.7,571.2
BEGIN DESCRIPTION:
structure xs 4 - channel burned 0.98':
lidar invert = 2776.78
effective invert = 2775.80
END DESCRIPTION:
Node Name=J
XS GIS Cut Line= 5
2319879.80836369562651.3582469592319829.52098974562857.079322209
2319751.80413909562925.6530139592319664.94412954 562985.08354681
2318736.91350119564457.132129714
#Sta/Elev= 30
       0 2812.74    67.8 2803.55   133.6 2791.06   166.6 2789.12   178.9 2791.72
   213.6 2791.38   224.1 2788.53   298.9 2787.14   320.6 2778.63   348.9 2779.33
   357.1  2775.8   406.9 2775.84   416.8 2779.38     430 2781.37   482.1 2780.72
   677.1 2780.69   766.4 2783.95   838.9 2781.89   999.6 2784.94  1288.4 2782.75
  1442.1 2784.12  1721.1 2784.09  1782.6 2782.82  1827.9 2784.84  1872.4 2783.93
  1891.7 2787.35  1910.3 2787.87    1970 2819.37  2057.2 2867.84  2160.8  2921.2
#Mann= 8 ,-1,0
       0     .05       0   178.9    .016       0   213.6     .08       0
   348.9    .035       0   416.8     .07       0   482.1     .05       0
  1827.9     .08       0    1970      .1       0
#XS Ineff= 2 , 0
                          1357.8          2796.6
Permanent Ineff=
       F       F
Bank Sta=348.9,416.8
XS Rating Curve= 0 ,0
Exp/Cntr(USF)=0,0
Exp/Cntr=0.5,0.3

Type RM Length L Ch R = 1 ,19096   ,142.1,142.4,136.5
BEGIN DESCRIPTION:
structure xs 3
channel burned per surveyed cross section data
END DESCRIPTION:
XS GIS Cut Line= 5
2319203.03575566561883.2505127452319293.08106086562395.573081654
2319266.63609495562507.9641867822319002.18643583563063.308470945
2318332.14116041564324.539363801
#Sta/Elev= 30
       0 2812.07    47.6 2810.57   143.9 2808.11   217.8 2811.35   318.7 2796.64
     404 2801.91   448.2 2799.57   501.5  2798.8   521.8  2802.1   538.9 2797.31
   620.4 2794.37   645.8 2791.21   663.6 2782.88  663.68 2779.64   708.9 2774.47
  744.06 2772.02   791.5 2774.55   812.5 2778.66  1303.9  2779.9  1351.2 2781.29
  1374.4  2781.7  1411.4 2782.11  1425.2 2782.27  1560.9    2781    2212 2782.36
  2306.6 2781.78  2383.5 2780.43  2421.4  2787.9  2590.6 2862.22  2678.9 2909.41
#Mann= 17 ,-1,0
       0     .07       0    47.6     .08       0   143.9     .06       0
   448.2    .016       0   501.5     .06       0   538.9    .016       0
   620.4     .07       0   708.9    .035       0   791.5     .06       0
  1303.9     .07       0  1351.2    .016       0  1374.4     .05       0
  1411.4    .016       0  1425.2     .05       0  1560.9     .06       0
    2212     .05       0  2306.6      .1       0
#XS Ineff= 4 ,-1
       0   635.8 2791.88     816 1384.62 2781.43 1384.62 2579.44  2792.9
 2579.44  2678.9 2781.43
Permanent Ineff=
       F       F       F       F
#Block Obstruct= 2 ,-1
 1377.83 1403.49 2801.91 1469.01 1507.93 2801.25
Bank Sta=708.9,791.5
XS Rating Curve= 0 ,0
Exp/Cntr=0.5,0.3