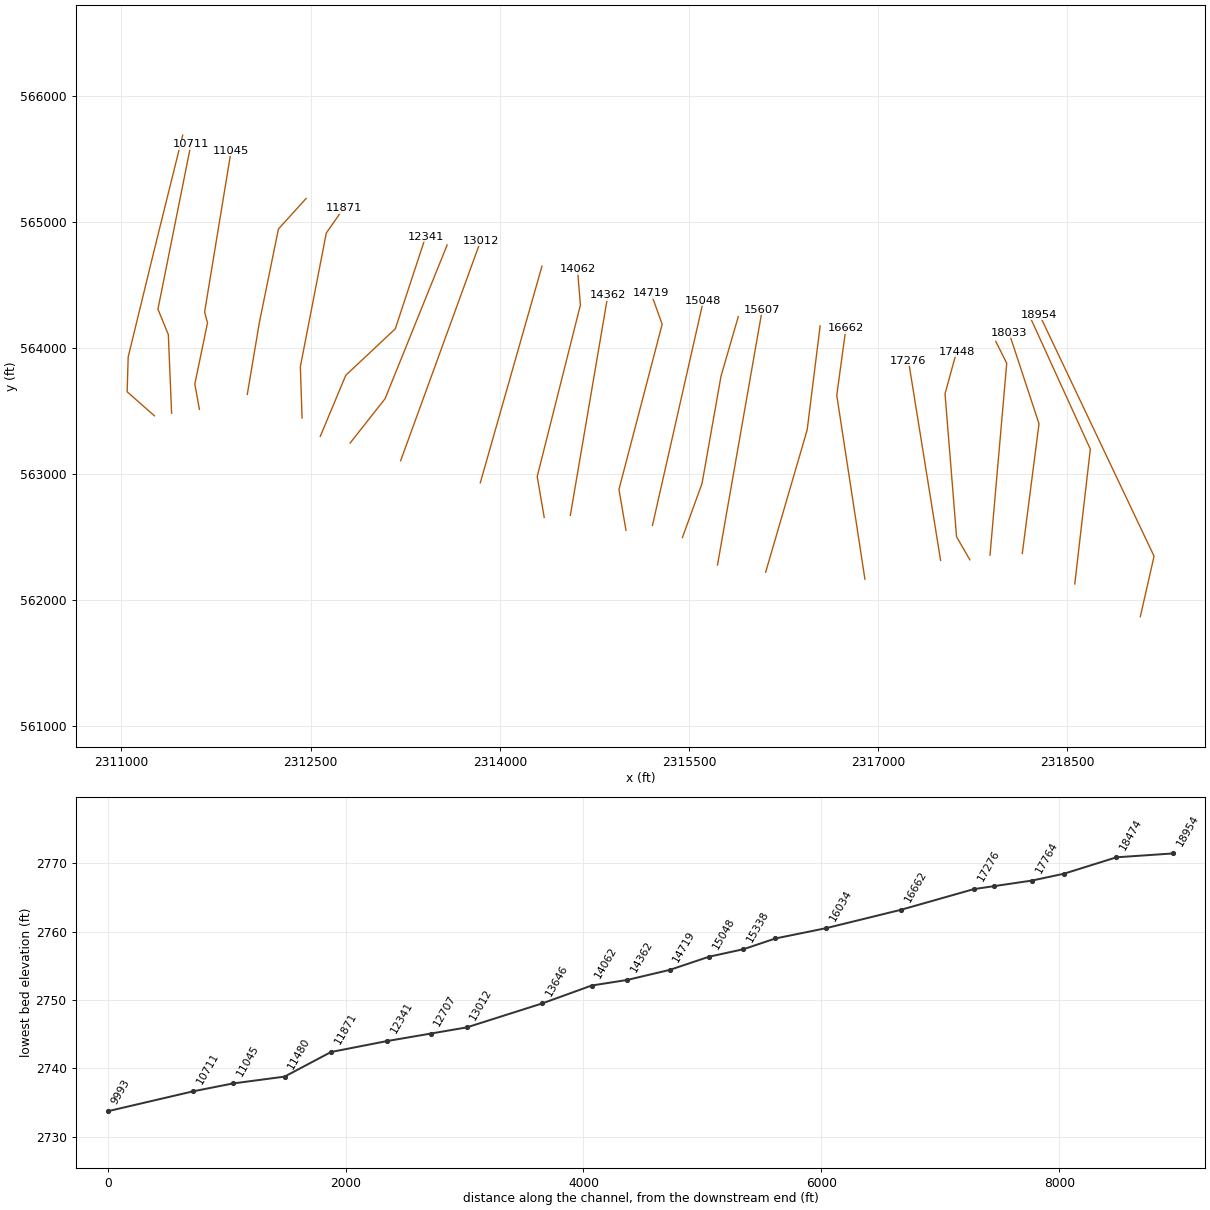
HEC-RAS study EFGRNBRRRV.prj: EFGRNBRRRV

--- EFGRNBRRRV.g01 (geometry) --- (continued)

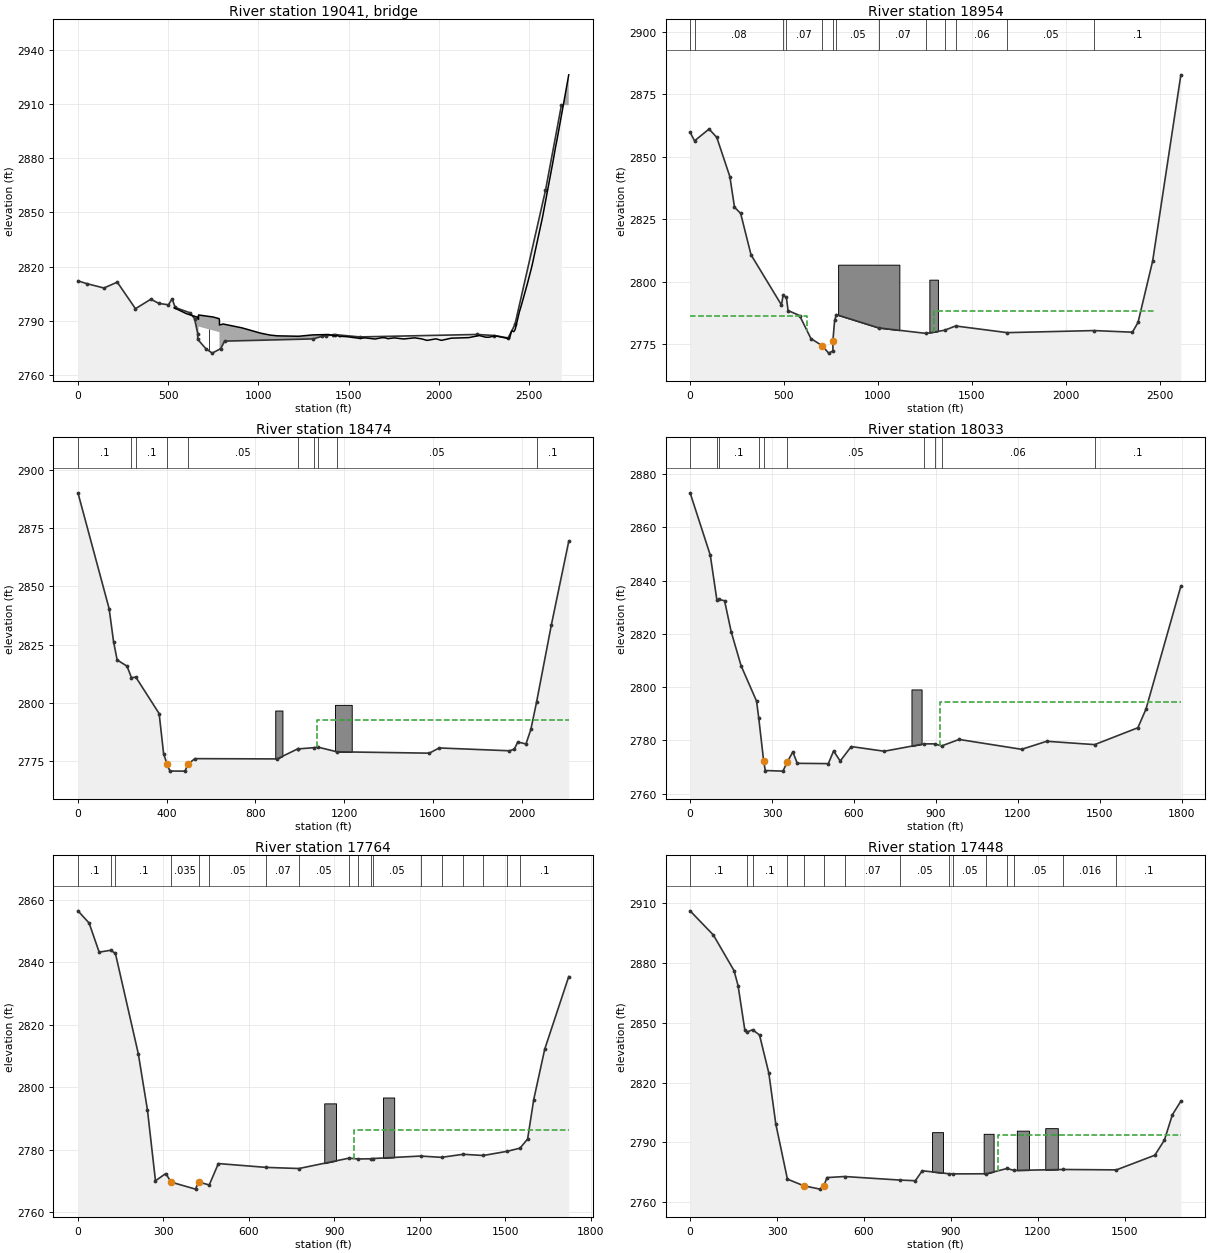
Type RM Length L Ch R = 3 ,19041   ,,,
BEGIN DESCRIPTION:
Bridge 54075EFG030
JV notes: road deck updated per surveyed XS data points
channel burned per surveyed cross sections
structure opening based on survey data, photos, and aerial imagery
surveyed inverts are approximately 1' below inverts from lidar:
 surveyed invert US is 2772.02
 surveyed invert DS is 2771.44
END DESCRIPTION:
Bridge Culvert--1,0,-1,-1, 0
Deck Dist Width WeirC Skew NumUp NumDn MinLoCord MaxHiCord MaxSubmerge Is_Ogee
34,46,2.6,0, 60, 60, , , 0.98, 0, 0,0,,
 533.732     601  663.43  667.88  667.88  748.44  782.19  784.02  784.02  804.47
  908.081013.1051065.2961104.0421222.4361299.5261388.2411424.3091437.2311451.918
1459.9861492.9391561.5921589.9651645.9791685.9521703.7181717.0431752.5741804.493
1866.0571902.8691934.674 1983.53 2014.622068.524 2165.632223.368  2258.92276.666
2307.7112325.5222387.7022392.1442401.0272405.4682414.3512418.7932423.2342445.441
2457.5572489.8562512.0632517.4712574.6942631.9822645.307 2654.192689.7212719.401
2797.108 2793.89 2791.88 2790.76 2793.16 2792.05 2791.13 2790.01 2787.61 2788.16
 2786.042783.0632782.0132781.6092781.3722782.1132782.3452781.591  2781.82781.094
2781.3192781.106 2780.192780.4812779.8442780.5942780.4862780.0182780.4792779.858
  2780.52779.943 2779.08 2779.932779.0982780.3082780.6192781.7812780.8542780.825
2781.5322781.346 2780.042780.4212783.7832784.4132783.911 2784.462785.3992794.715
2798.7512810.3192818.8872821.1512847.5992878.0472885.6492890.191 2909.642926.248
                         2786.77 2786.772784.5922783.679 2783.63 2783.63
                                                                                
                                                                                
                                                                                
                                                                                
                                                                                
    -243 -94.753  45.513 133.023 231.837 338.462 428.706 517.978     577  639.43
  643.88  643.88  724.44  758.19  760.02  760.02  780.47  884.08 989.1051080.042
1198.4361275.5261364.2411400.3091413.2311427.9181468.9391537.5921565.9651621.979
1661.9521693.0431728.5741780.4931842.0571910.674 1959.53 1990.622044.524 2141.63
2199.368  2234.92252.6662283.7112301.5222363.7022368.1442377.0272381.4682390.351
2394.7932399.2342421.4412465.8562488.0632550.6942607.9822621.3072665.7212695.401
2852.8472840.4232830.4552823.6432816.5372808.0812801.9122796.567 2793.89 2791.88
 2790.76 2793.16 2792.05 2791.13 2790.01 2787.61 2788.16 2786.042783.0632781.609
2781.3722782.1132782.3452781.591  2781.82781.0942781.106 2780.192780.4812779.844
2780.5942780.0182780.4792779.858  2780.5 2779.08 2779.932779.0982780.3082780.619
2781.7812780.8542780.8252781.5322781.346 2780.042780.4212783.7832784.4132783.911
 2784.462785.3992794.7152810.3192818.8872847.5992878.0472885.649 2909.642926.248
                                                                                
 2786.77 2786.772784.5922783.679 2783.63 2783.63
                                                                                
                                                                                
                                                                                
                                                                                
Pier Skew, UpSta & Num, DnSta & Num=  ,725.89, 2 ,700.89, 2 , 0 , 0 , 0 ,,
       3       3
       0    2787
       3       3
       0    2787
BR Coef=-1 ,-1 , 0 ,, 0 ,,,0.8,0,1.33,0,
WSPro=,,,, 1 ,,,, 0 ,,,, 0 ,,,,-1 ,-1 ,-1 , 0 , 0 , 0 , 0 , 0
BR U #Sta/Elev= 30
       0 2812.07    47.6 2810.57   143.9 2808.11   217.8 2811.35   318.7 2796.64
     404 2801.91   448.2 2799.57   501.5  2798.8   521.8  2802.1   538.9 2797.31
   620.4 2794.37   645.8 2791.21   663.6 2782.88  663.68 2779.64   708.9 2774.47
  744.06 2772.02   791.5 2774.55   812.5 2778.66  1303.9  2779.9  1351.2 2781.29
  1374.4  2781.7  1411.4 2782.11  1425.2 2782.27  1560.9    2781    2212 2782.36
  2306.6 2781.78  2383.5 2780.43  2421.4  2787.9  2590.6 2862.22  2678.9 2909.41
BR U #Mann= 17
       0     .07    47.6     .08   143.9     .06   448.2    .016   501.5     .06
   538.9    .016   620.4     .06   708.9     .03   791.5     .06  1303.9     .07
  1351.2    .016  1374.4     .05  1411.4    .016  1425.2     .05  1560.9     .06
    2212     .05  2306.6      .1
BR D #Sta/Elev= 30
       0 2859.84    23.8 2856.42     101 2861.15     142 2857.82   211.8 2842.08
   236.4 2829.88   269.2 2827.36   324.5 2810.79   486.6 2790.71   495.1 2794.56
   512.8 2793.75   521.7 2788.48   582.9 2786.49   643.5 2777.26  702.58 2774.46
  738.07 2771.44  760.51 2772.32  760.53 2776.49   769.6 2784.53     779 2786.85
  1004.2 2781.54  1256.5 2779.34  1355.2  2780.6  1413.9 2782.31  1688.5 2779.64
  2150.7 2780.47  2355.2 2779.82  2385.2 2783.72  2463.3 2808.38  2613.4 2882.85
BR D #Mann= 13
       0     .07    23.8     .08   495.1    .016   512.8     .07  702.58     .03
  760.53     .08     779     .05  1004.2     .07  1256.5     .06  1355.2    .016
  1413.9     .06  1688.5     .05  2150.7      .1
BC Design=,, 0 ,, 0 ,,,,,,
BC Use User HTab Curves=0
BC User HTab FreeFlow(D)= 0

Type RM Length L Ch R = 1 ,18954   ,515.6,479.6,178.3
BEGIN DESCRIPTION:
structure xs 2
channel burned per surveyed cross section data
END DESCRIPTION:
XS GIS Cut Line= 3
2319078.21571282561866.6737634032319187.30119721562345.988770568
2318278.26407076564263.230709994
#Sta/Elev= 30
       0 2859.84    23.8 2856.42     101 2861.15     142 2857.82   211.8 2842.08
   236.4 2829.88   269.2 2827.36   324.5 2810.79   486.6 2790.71   495.1 2794.56
   512.8 2793.75   521.7 2788.48   582.9 2786.49   643.5 2777.26  702.58 2774.46
  738.07 2771.44  760.51 2772.32  760.53 2776.49   769.6 2784.53     779 2786.85
  1004.2 2781.54  1256.5 2779.34  1355.2  2780.6  1413.9 2782.31  1688.5 2779.64
  2150.7 2780.47  2355.2 2779.82  2385.2 2783.72  2463.3 2808.38  2613.4 2882.85
#Mann= 13 ,-1,0
       0     .07       0    23.8     .08       0   495.1    .016       0
   512.8     .07       0  702.58    .035       0  760.53     .08       0
     779     .05       0  1004.2     .07       0  1256.5     .06       0
  1355.2    .016       0  1413.9     .06       0  1688.5     .05       0
  2150.7      .1       0
#XS Ineff= 4 ,-1
       0   622.9 2786.35  781.12  1300.5    2779  1300.5  2471.6 2788.17
  2471.6  2613.4    2779
Permanent Ineff=
       F       F       F       F
#Block Obstruct= 2 ,-1
  788.18 1114.32 2806.85 1274.05 1319.67 2800.85
Bank Sta=702.58,760.53
XS Rating Curve= 0 ,0
Exp/Cntr(USF)=0,0
Exp/Cntr=0.5,0.3

Type RM Length L Ch R = 1 ,18474   ,443.7,440.9,440.8
BEGIN DESCRIPTION:
channel from lidar
END DESCRIPTION:
XS GIS Cut Line= 3
2318558.62190264562125.6266102072318682.05454779 563195.37620151
2318211.18186444564228.553157213
#Sta/Elev= 30
       0 2890.12   140.5 2840.49   160.6 2826.29   176.7 2818.51     221 2815.86
   241.1 2810.95   260.9 2811.14     366 2795.53   386.1 2778.32   401.7  2773.9
   414.3 2770.91   482.7 2770.87   494.8 2773.77     527 2776.22   897.5  2776.1
   990.1 2780.38   990.1 2780.37  1062.6 2780.91  1083.2 2781.12  1167.2 2779.16
  1583.9 2778.57  1628.3  2780.8  1944.8 2779.59  1966.8 2780.24  1982.5 2783.37
  2019.5 2782.51  2041.5 2788.73    2067  2800.3  2133.8 2833.44  2212.3  2869.3
#Mann= 10 ,-1,0
       0      .1       0   241.1    .016       0   260.9      .1       0
   401.7    .035       0   494.8     .05       0   990.1     .07       0
  1062.6    .016       0  1083.2     .06       0  1167.2     .05       0
    2067      .1       0
#XS Ineff= 2 , 0
                         1076.06         2792.71
Permanent Ineff=
       F       F
#Block Obstruct= 2 ,-1
  889.28  921.72 2796.84 1158.61 1234.06 2799.26
Bank Sta=401.7,494.8
XS Rating Curve= 0 ,0
Exp/Cntr(USF)=0,0
Exp/Cntr=0.3,0.1

Type RM Length L Ch R = 1 ,18033   ,266.4,269,284.7
BEGIN DESCRIPTION:
channel from lidar
END DESCRIPTION:
XS GIS Cut Line= 3
2318142.60817269562367.9203210582318275.18397674563396.525697311
2318037.46184534564118.835250413
#Sta/Elev= 30
       0 2872.98    73.9 2849.58    98.1 2832.76   106.1 2832.94   126.3 2832.44
   150.5 2820.81   186.8 2808.03   243.3 2794.78   251.3 2788.52  269.65  2772.1
   275.5  2768.7     340 2768.47   356.2 2771.94   376.3 2775.71   392.5  2771.4
   506.3 2771.29   525.6 2776.03   549.8 2772.26   590.1  2777.7   711.1 2775.94
   856.4 2778.71   895.7  2778.7     921 2777.93   985.3 2780.37  1214.3 2776.66
  1306.2 2779.68  1481.8 2778.43    1640 2784.76  1669.5 2791.71  1797.5 2837.97
#Mann= 10 ,-1,0
       0      .1       0    98.1    .016       0   106.1      .1       0
   251.3     .12       0  269.65    .035       0   356.2     .05       0
   856.4     .06       0   895.7    .016       0     921     .06       0
  1481.8      .1       0
#XS Ineff= 2 , 0
                          915.66         2794.54
Permanent Ineff=
       F       F
#Block Obstruct= 1 ,-1
  810.76  847.88 2799.15
Bank Sta=269.65,356.2
XS Rating Curve= 0 ,0
Exp/Cntr(USF)=0,0
Exp/Cntr=0.3,0.1

Type RM Length L Ch R = 1 ,17764   ,301.1,316.5,358
BEGIN DESCRIPTION:
channel from lidar
END DESCRIPTION:
Node Name=I
XS GIS Cut Line= 3
2317886.59972348562354.2055827082318019.17552753563876.541539562
2317932.31551798564050.261558663
#Sta/Elev= 30
       0 2856.43    39.1 2852.53    74.4 2843.23   115.4 2843.83   131.5 2842.79
   211.8 2810.74   243.9 2792.76     272 2770.14   308.1 2772.44     327 2769.71
   412.5 2767.47  423.33 2769.74   460.7 2768.81   492.8 2775.64   661.5 2774.41
   775.6 2774.06   950.6 2777.36     983 2777.12  1027.3 2777.16  1034.7 2777.25
  1202.2 2778.04  1275.8 2777.63  1351.8 2778.61  1422.1 2778.22  1505.7 2779.55
  1551.2 2780.57    1578 2783.48  1599.4 2796.08  1638.1 2812.23  1722.3 2835.41
#Mann= 18 ,-1,0
       0      .1       0   115.4    .016       0   131.5      .1       0
     327    .035       0  423.33      .1       0   460.7     .05       0
   661.5     .07       0   775.6     .05       0   950.6    .016       0
     983     .05       0  1027.3    .016       0  1034.7     .05       0
  1202.2    .016       0  1275.8     .05       0  1351.8     .07       0
  1422.1    .016       0  1505.7     .05       0  1551.2      .1       0
#XS Ineff= 2 , 0
                          967.44         2786.38
Permanent Ineff=
       F       F
#Block Obstruct= 2 ,-1
  864.27  905.73 2794.88 1070.36 1109.73 2796.76
Bank Sta=327,423.33
XS Rating Curve= 0 ,0
Exp/Cntr(USF)=0,0
Exp/Cntr=0.3,0.1

Type RM Length L Ch R = 1 ,17448   ,166.6,172,190.6
BEGIN DESCRIPTION:
channel from lidar
END DESCRIPTION:
XS GIS Cut Line= 4
2317726.59444273562317.6329471082317621.44811538562500.496125108
2317530.01652638563634.2478287122317621.44811538563967.973128563
#Sta/Elev= 30
       0 2905.94    80.5  2893.8   151.7 2876.01   165.6 2868.54   188.7 2846.53
   197.4 2845.31   215.6 2846.44   239.7 2843.79   271.8 2824.75   295.9 2799.25
     336 2771.67   392.2 2768.35   448.4 2766.66   461.6 2768.23   472.5 2772.44
   533.3 2772.97   725.2 2771.19   777.7 2770.87   801.5 2775.86   893.8 2774.36
   907.2 2774.28  1022.2 2774.34  1094.5 2776.99  1118.8 2776.02  1288.4 2776.49
  1471.7 2776.29  1604.4 2783.62  1637.6 2791.21    1665 2803.88  1694.4 2810.68
#Mann= 15 ,-1,0
       0      .1       0   197.4    .016       0   215.6      .1       0
     336     .12       0   392.2    .035       0   461.6     .12       0
   533.3     .07       0   725.2     .05       0   893.8    .016       0
   907.2     .05       0  1022.2     .07       0  1094.5    .016       0
  1118.8     .05       0  1288.4    .016       0  1471.7      .1       0
#XS Ineff= 2 , 0
                         1062.65         2793.56
Permanent Ineff=
       F       F
#Block Obstruct= 4 ,-1
  835.15  873.23 2795.17 1013.56  1047.8 2794.34  1128.1 1169.98 2795.92
 1226.18 1269.49 2797.17
Bank Sta=392.2,461.6
XS Rating Curve= 0 ,0
Exp/Cntr(USF)=0,0
Exp/Cntr=0.3,0.1

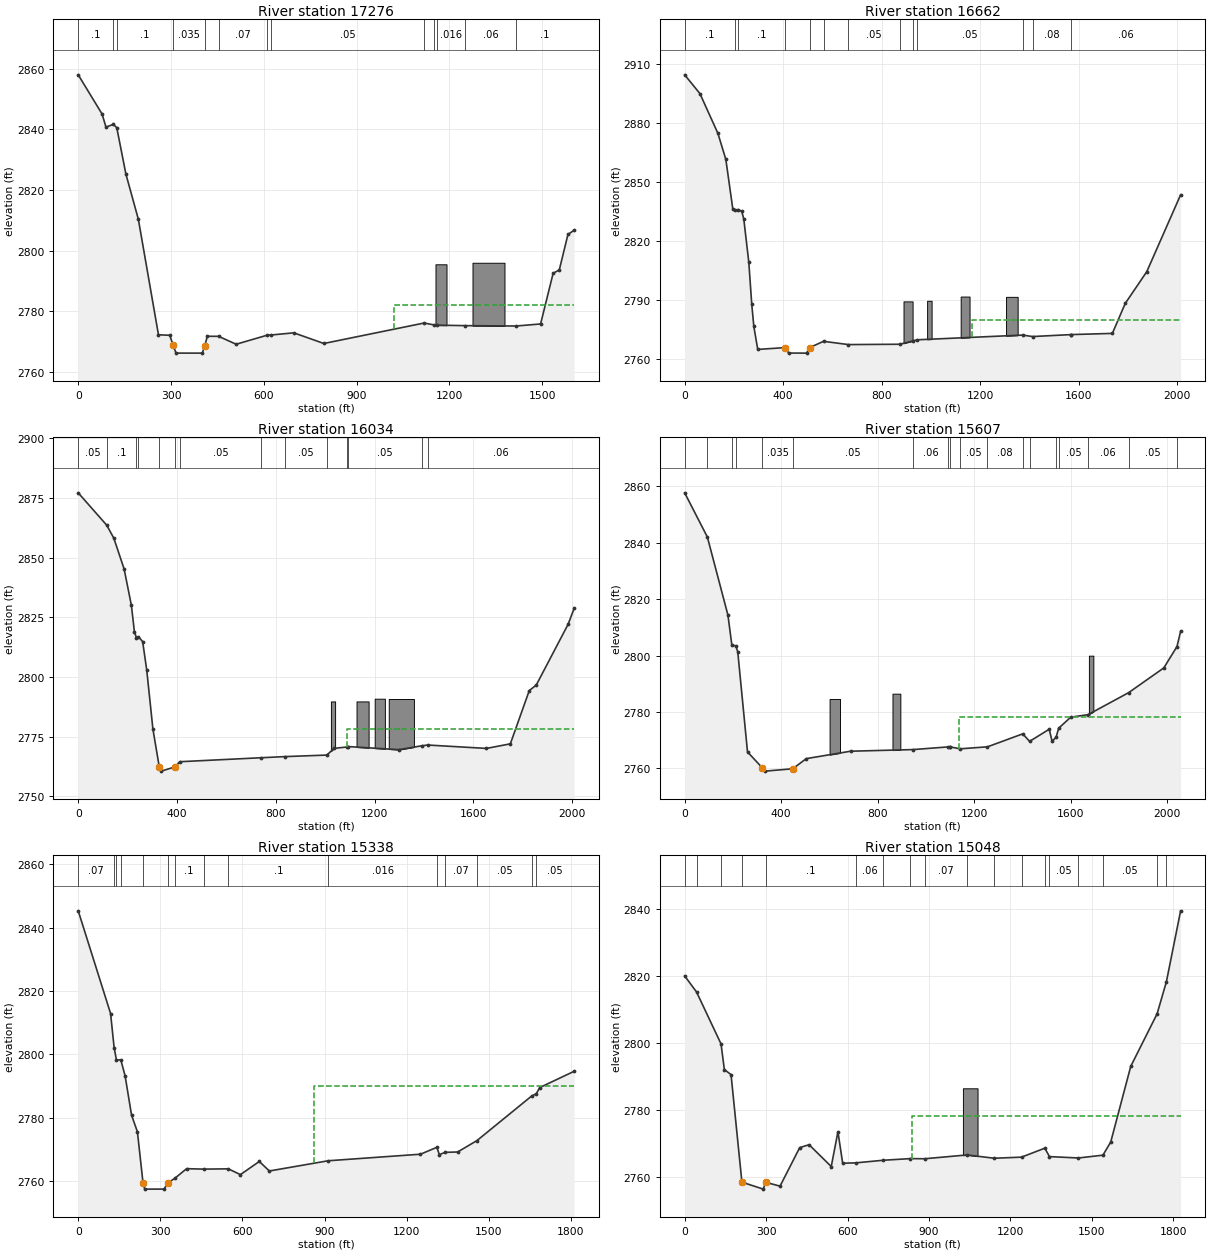
Type RM Length L Ch R = 1 ,17276   ,615.2,614.2,611.7
BEGIN DESCRIPTION:
channel from lidar
END DESCRIPTION:
XS GIS Cut Line= 2
2317494.82337881562312.932563177 2317240.2905819563896.324897189
#Sta/Elev= 30
       0 2857.97    77.2 2845.05    89.8 2840.72   113.7 2841.65   124.7 2840.54
   154.2 2825.26   194.5 2810.34   259.5 2772.27     296  2772.1  307.24 2768.74
   316.3 2766.23   401.3 2766.22  409.23 2768.64   417.5 2771.78     454 2771.76
   510.7 2769.15     612 2772.16   624.2  2772.2   697.1 2772.91   794.3  2769.4
  1118.4 2776.14  1150.8 2775.53  1158.9 2775.44    1252 2775.28  1416.3 2775.16
  1495.2 2775.84  1535.7 2792.53  1555.7 2793.68  1583.6 2805.33  1603.7 2806.76
#Mann= 13 ,-1,0
       0      .1       0   113.7    .016       0   124.7      .1       0
  307.24    .035       0  409.23      .1       0     454     .07       0
     612    .016       0   624.2     .05       0  1118.4    .016       0
  1150.8     .05       0  1158.9    .016       0    1252     .06       0
  1416.3      .1       0
#XS Ineff= 2 , 0
                         1020.17         2781.98
Permanent Ineff=
       F       F
#Block Obstruct= 2 ,-1
 1155.31 1190.96 2795.51 1274.98 1378.46 2796.02
Bank Sta=307.24,409.23
XS Rating Curve= 0 ,0
Exp/Cntr(USF)=0,0
Exp/Cntr=0.3,0.1

Type RM Length L Ch R = 1 ,16662   ,647.6,628.2,494.3
BEGIN DESCRIPTION:
channel from lidar
END DESCRIPTION:
XS GIS Cut Line= 3
2316894.91827557      562163.8662316671.72381479563621.958375847
2316744.25437926 564155.84108537
#Sta/Elev= 30
       0 2904.54      62 2894.98   134.9 2874.82   167.2 2861.54   195.6 2836.24
   203.6 2835.68   217.6  2836.1     232 2835.14   240.1 2831.21   260.3 2809.45
   272.4 2787.92   280.8 2776.75   296.7 2765.07  408.362766.001   422.2 2763.23
     495 2763.19   507.2 2765.98   563.8 2769.19     665 2767.53   873.9  2767.7
     928 2769.43   944.3 2769.96  1372.2 2772.36  1412.6 2771.61  1567.1 2772.59
  1567.1  2772.6  1736.7 2773.21  1789.2 2788.47  1876.4 2804.55  2013.9 2843.59
#Mann= 13 ,-1,0
       0      .1       0   203.6    .016       0   217.6      .1       0
  408.36    .035       0   507.2     .08       0   563.8     .07       0
     665     .05       0   873.9     .07       0     928    .016       0
   944.3     .05       0  1372.2    .016       0  1412.6     .08       0
  1567.1     .06       0
#XS Ineff= 2 , 0
                         1164.79          2780.1
Permanent Ineff=
       F       F
#Block Obstruct= 4 ,-1
  888.61  925.52 2789.47  984.51 1002.69 2789.79 1120.75 1156.83 2791.93
 1305.02  1352.1 2791.78
Bank Sta=408.36,507.2
XS Rating Curve= 0 ,0
Exp/Cntr=0.3,0.1

Type RM Length L Ch R = 1 ,16034   ,423.2,426.5,461.6
BEGIN DESCRIPTION:
channel from lidar
END DESCRIPTION:
XS GIS Cut Line= 3
2316107.82272157562218.7468295632316437.02474231563347.591854504
2316539.93065769564173.426603846
#Sta/Elev= 30
       0 2877.16   115.6 2863.58   144.2 2858.13   185.9 2845.23   215.2 2830.07
   227.5 2818.99   235.9 2816.36   244.1 2816.81   260.9 2814.83   277.5 2802.83
   302.5 2778.11   328.1 2762.34   335.9 2760.51   392.6  2762.3   410.9 2764.45
     740 2766.12   835.9 2766.59  1006.7 2767.24  1035.9 2770.05  1087.1 2770.61
  1094.2  2770.8  1298.4  2769.5  1390.5 2771.12  1415.3 2771.45  1653.1 2770.03
  1749.7 2771.95  1826.4 2794.28  1854.7 2796.59  1983.7 2822.07  2008.1 2828.74
#Mann= 14 ,-1,0
       0     .05       0   115.6      .1       0   235.9    .016       0
   244.1      .1       0   328.1    .035       0   392.6     .07       0
   410.9     .05       0     740     .06       0   835.9     .05       0
  1006.7     .07       0  1087.1    .016       0  1094.2     .05       0
  1390.5    .016       0  1415.3     .06       0
#XS Ineff= 2 , 0
                         1090.14         2778.09
Permanent Ineff=
       F       F
#Block Obstruct= 4 ,-1
 1023.19 1040.21 2789.72 1126.91 1175.87 2789.73 1200.49  1241.7 2790.87
 1257.26 1359.26 2790.75
Bank Sta=328.1,392.6
XS Rating Curve= 0 ,0
Exp/Cntr=0.3,0.1

Type RM Length L Ch R = 1 ,15607   ,289.9,269.1,232.3
BEGIN DESCRIPTION:
channel burned 0.25':
lidar invert = 2759.25
effective invert = 2759
END DESCRIPTION:
XS GIS Cut Line= 2
2315726.29027557562276.5564147812316080.80196735564301.868569759
#Sta/Elev= 30
       0 2857.69      94 2842.03   179.3 2814.34   195.6 2803.68   211.8 2803.44
     220 2801.34   260.5 2765.81   321.4 2760.21   333.6    2759     448 2759.84
   504.2 2763.43   687.6 2766.06   946.8 2766.64  1091.2 2767.58  1101.1  2767.6
  1101.1 2767.59  1141.7 2766.91  1255.4 2767.62  1401.6 2772.22    1430 2769.56
  1511.3 2773.85  1523.4 2769.56    1540 2771.05  1550.4 2774.21  1600.6 2778.14
  1672.1 2779.02  1840.2 2786.81  1986.4  2795.6  2041.1 2803.19  2056.1 2808.57
#Mann= 18 ,-1,0
       0     .05       0      94      .1       0   195.6    .016       0
   211.8      .1       0   321.4    .035       0     448     .05       0
   946.8     .06       0  1091.2    .016       0  1101.1     .06       0
  1141.7     .05       0  1255.4     .08       0  1401.6    .016       0
    1430     .05       0    1540     .06       0  1550.4     .05       0
  1672.1     .06       0  1840.2     .05       0  2041.1      .1       0
#XS Ineff= 2 , 0
                         1135.97         2778.05
Permanent Ineff=
       F       F
#Block Obstruct= 3 ,-1
  600.73  643.88  2784.6  861.47  894.16 2786.47 1675.79 1694.31 2799.95
Bank Sta=321.4,448
XS Rating Curve= 0 ,0
Exp/Cntr=0.3,0.1

Type RM Length L Ch R = 1 ,15338   ,283.6,289.5,310.9
BEGIN DESCRIPTION:
channel from lidar
END DESCRIPTION:
Node Name=H
XS GIS Cut Line= 4
2315448.01504627 562493.848066842315603.65765255562923.206980715
 2315753.9332724563773.874328832 2315890.7914262564246.169134096
#Sta/Elev= 30
       0 2845.33   118.3  2812.9   131.2 2802.15   139.7 2798.21   155.7 2798.26
   171.4 2793.19     195 2780.76   216.3 2775.55   236.9 2759.34   243.2 2757.43
   314.1 2757.44   326.9 2759.38   352.5 2760.81   396.2 2763.89   458.8 2763.75
   548.6 2763.84   592.7 2762.01   661.8 2766.17   698.4 2763.16   913.6 2766.39
  1250.8 2768.46  1310.4 2770.63  1319.8 2768.33  1341.2 2769.05  1386.6 2769.16
  1457.4 2772.78  1657.1 2786.85  1673.9 2787.55  1686.3  2789.5  1812.3 2794.65
#Mann= 15 ,-1,0
       0     .07       0   131.2     .06       0   139.7    .016       0
   155.7      .1       0   236.9    .035       0   326.9     .07       0
   352.5      .1       0   458.8     .05       0   548.6      .1       0
   913.6    .016       0  1310.4     .08       0  1341.2     .07       0
  1457.4     .05       0  1657.1    .016       0  1673.9     .05       0
#XS Ineff= 2 , 0
                          860.59         2790.05
Permanent Ineff=
       F       F
Bank Sta=236.9,326.9
XS Rating Curve= 0 ,0
Exp/Cntr(USF)=0,0
Exp/Cntr=0.3,0.1

Type RM Length L Ch R = 1 ,15048   ,330.5,329.2,317.9
BEGIN DESCRIPTION:
channel from lidar
END DESCRIPTION:
XS GIS Cut Line= 2
2315210.63944812562590.6047052592315613.92517829564372.334283615
#Sta/Elev= 30
       0 2820.12    43.7 2815.32   133.9 2799.78   146.2 2792.11   170.8 2790.59
  210.79 2758.42   289.7 2756.33   297.9 2758.39   351.2 2757.22   423.7 2768.75
   458.3 2769.62   539.9 2763.09   564.5 2773.51     582 2764.08   630.1 2764.19
   731.7 2764.97   831.1 2765.46   884.4 2765.42  1040.1 2766.56  1140.5 2765.57
  1240.8  2765.9  1326.6 2768.58  1343.7 2766.06  1450.4 2765.65  1540.6 2766.49
  1569.3 2770.41  1643.1 2793.07  1740.1 2808.77  1774.4 2818.37  1826.8  2839.6
#Mann= 18 ,-1,0
       0     .07       0    43.7      .1       0   133.9     .06       0
  210.79    .035       0   297.9      .1       0   630.1     .06       0
   731.7     .07       0   831.1     .08       0   884.4     .07       0
  1040.1     .06       0  1140.5     .07       0  1240.8     .08       0
  1326.6     .07       0  1343.7     .05       0  1450.4     .06       0
  1540.6     .05       0  1740.1      .1       0  1774.4     .05       0
#XS Ineff= 2 , 0
                          836.49         2778.29
Permanent Ineff=
       F       F
#Block Obstruct= 1 ,-1
 1024.88 1078.77  2786.5
Bank Sta=210.79,297.9
XS Rating Curve= 0 ,0
Exp/Cntr(USF)=0,0
Exp/Cntr=0.3,0.1

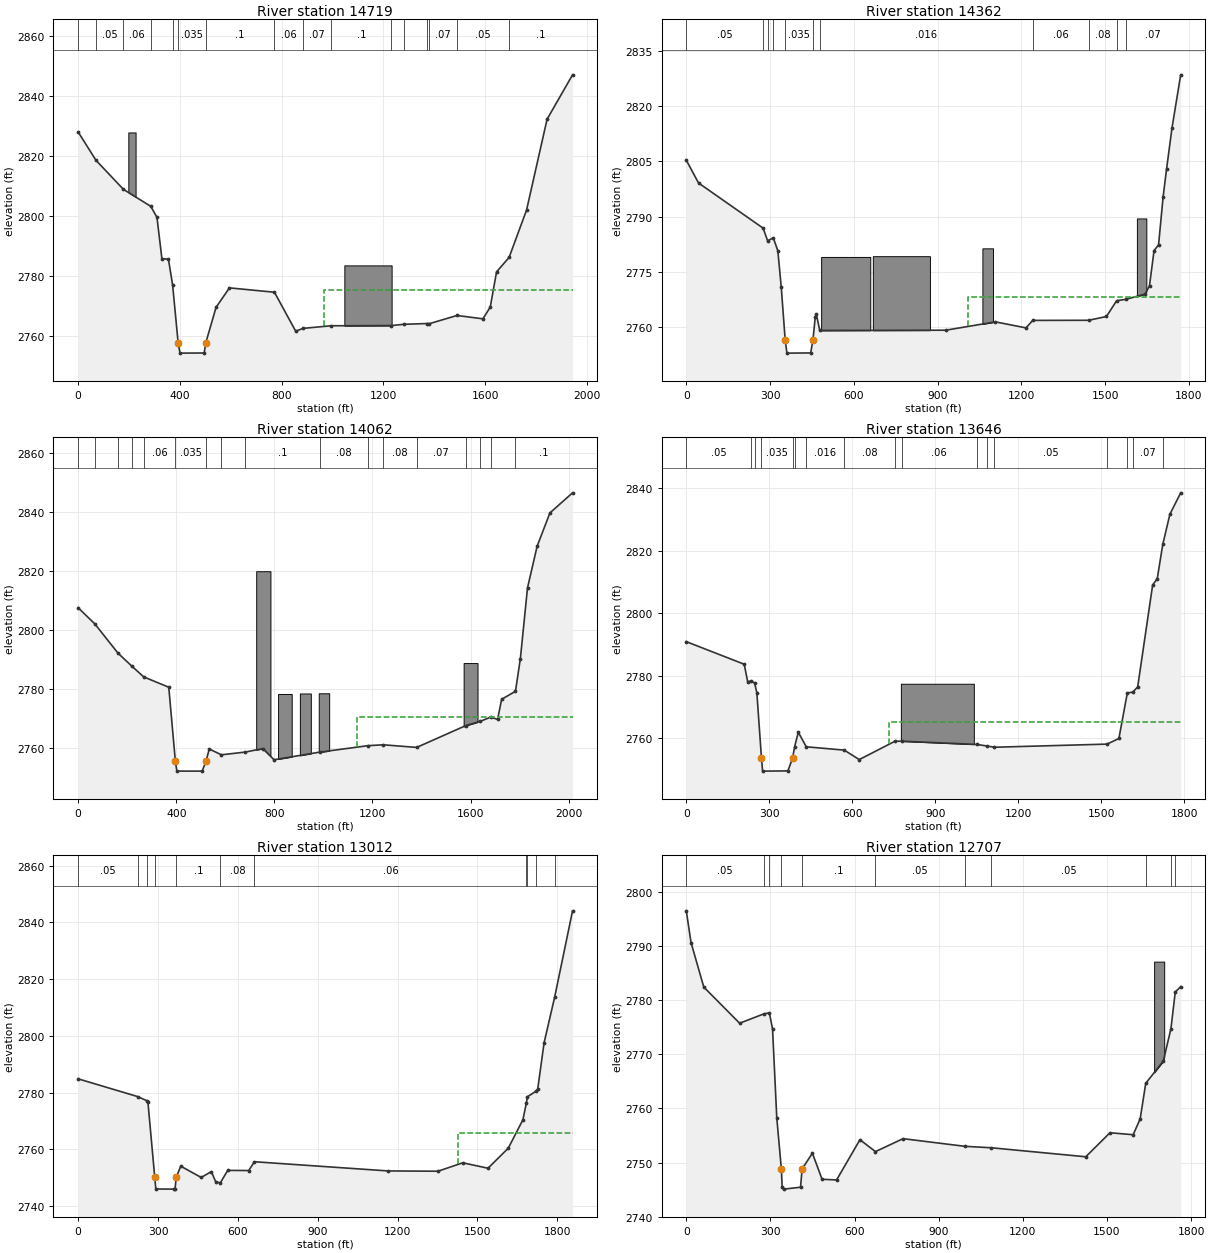
Type RM Length L Ch R = 1 ,14719   ,352.2,357.1,361.6
BEGIN DESCRIPTION:
channel from lidar
END DESCRIPTION:
XS GIS Cut Line= 4
2315000.46998427562551.7795238592314944.91559086562875.846818743
2315287.50101688564186.0045966312315199.53989398564431.369834186
#Sta/Elev= 30
       0 2828.13    70.4 2818.66   178.2 2808.99   285.6 2803.34   309.9 2799.66
   329.3  2785.9     355 2785.71   371.5  2777.1   393.3  2757.7   400.5 2754.41
   495.6 2754.46  501.67 2757.82   542.3 2769.69   594.8 2776.16   771.7 2774.71
   855.3 2761.72   884.2 2762.66   994.6 2763.53  1231.5  2763.6  1279.7 2764.01
  1372.1 2764.28  1380.3 2764.22  1489.5 2766.96  1591.2 2765.84  1620.1 2769.74
  1644.9 2781.49  1694.3 2786.33  1762.9 2802.11  1843.6  2832.4  1943.7 2847.18
#Mann= 16 ,-1,0
       0      .1       0    70.4     .05       0   178.2     .06       0
   285.6     .05       0   371.5     .06       0   393.3    .035       0
  501.67      .1       0   771.7     .06       0   884.2     .07       0
   994.6      .1       0  1231.5     .08       0  1279.7     .06       0
  1372.1     .08       0  1380.3     .07       0  1489.5     .05       0
  1694.3      .1       0
#XS Ineff= 2 , 0
                          968.46         2775.37
Permanent Ineff=
       F       F
#Block Obstruct= 2 ,-1
  197.29  225.87 2827.98 1046.54 1232.38 2783.66
Bank Sta=393.3,501.67
XS Rating Curve= 0 ,0
Exp/Cntr(USF)=0,0
Exp/Cntr=0.3,0.1

Type RM Length L Ch R = 1 ,14362   ,307.4,300.3,296.4
BEGIN DESCRIPTION:
channel from lidar
END DESCRIPTION:
XS GIS Cut Line= 2
2314559.43216252562669.9396029962314856.93802904564415.307353222
#Sta/Elev= 30
       0  2805.3    43.9  2799.1   275.2 2786.84   291.4 2783.41   311.7 2784.22
   327.9 2780.68   340.1 2770.86  354.232756.465   360.4 2752.94   445.6 2752.99
   453.7 2756.55   461.8 2762.62   465.9 2763.44     478 2759.09   929.1 2759.16
    1107 2761.42  1216.5 2759.79  1240.9 2761.82  1441.1 2761.85  1504.6 2762.88
  1541.2 2767.17  1573.9 2767.53  1643.2 2768.96  1658.8 2771.25  1675.1 2780.76
  1691.3 2782.33  1707.5 2795.29  1719.7 2802.77  1739.5 2814.09  1770.5 2828.44
#Mann= 11 ,-1,0
       0     .05       0   275.2     .08       0   291.4    .016       0
   311.7     .08       0  354.23    .035       0   453.7     .08       0
     478    .016       0  1240.9     .06       0  1441.1     .08       0
  1541.2    .016       0  1573.9     .07       0
#XS Ineff= 2 , 0
                         1010.36         2768.21
Permanent Ineff=
       F       F
#Block Obstruct= 4 ,-1
  483.01  658.89 2779.04  668.06  872.48 2779.24 1060.42 1098.54 2781.37
 1613.59 1647.52 2789.48
Bank Sta=354.23,453.7
XS Rating Curve= 0 ,0
Exp/Cntr(USF)=0,0
Exp/Cntr=0.3,0.1

Type RM Length L Ch R = 1 ,14062   ,420.1,416.3,453.6
BEGIN DESCRIPTION:
channel from lidar
END DESCRIPTION:
XS GIS Cut Line= 4
 2314352.3353945562653.6292451082314296.78100109562977.696539992
2314639.36642711564338.7791785052314616.21876319564621.180678333
#Sta/Elev= 30
       0 2807.61    68.5 2802.07   162.6 2792.17   218.7 2787.78   267.4 2784.11
   369.5 2780.61  396.35 2755.51   402.5 2752.13   505.6 2752.12   521.8 2755.61
   534.5 2759.64     584 2757.66   680.5 2758.58   753.1 2759.77   798.5 2755.98
   984.1 2758.56  1181.4 2760.76  1243.9 2761.06  1380.1 2760.17  1580.1 2767.57
  1639.4 2769.03  1681.2 2770.43  1710.1  2769.7  1726.6 2776.51  1782.9 2779.22
    1803 2790.36    1832 2814.34  1871.2 2828.47  1923.4  2839.8  2015.7 2846.62
#Mann= 17 ,-1,0
       0     .05       0    68.5     .06       0   162.6     .05       0
   218.7     .07       0   267.4     .06       0  396.35    .035       0
   521.8     .05       0     584     .08       0   680.5      .1       0
   984.1     .08       0  1181.4      .1       0  1243.9     .08       0
  1380.1     .07       0  1580.1     .06       0  1639.4      .1       0
  1681.2     .05       0  1782.9      .1       0
#XS Ineff= 2 , 0
                         1134.94         2770.58
Permanent Ineff=
       F       F
#Block Obstruct= 6 ,-1
   97.72  125.72    2778     726     784    2820  815.24  870.75 2778.33
  903.89  948.64 2778.49  980.83 1023.49 2778.55 1571.58 1628.23 2788.81
Bank Sta=396.35,521.8
XS Rating Curve= 0 ,0
Exp/Cntr(USF)=0,0
Exp/Cntr=0.3,0.1

Type RM Length L Ch R = 1 ,13646   ,636.3,633.2,664.1
BEGIN DESCRIPTION:
channel burned 1.59':
lidar invert = 2751.09
effective invert = 2749.50
END DESCRIPTION:
XS GIS Cut Line= 2
2313845.41808289562927.7780206432314334.64995227564646.700804957
#Sta/Elev= 30
       0 2790.91   209.4 2783.69   221.9 2778.13   234.4 2778.29   246.8 2777.73
   255.1  2774.6   271.8 2753.69   275.9  2749.5   367.4 2749.57   384.1 2753.59
   391.9 2757.36   404.9 2761.94   433.8 2757.28   571.2 2756.22   625.3 2753.19
   754.4 2759.06   779.2 2759.08  1049.5 2758.04  1087.9 2757.53  1113.8 2757.14
  1521.2 2758.14  1563.8 2759.94  1594.3 2774.51  1614.2 2774.78  1631.7 2776.43
  1685.8 2809.03  1702.4 2811.03  1722.4 2821.99  1748.2 2831.67  1787.2 2838.51
#Mann= 17 ,-1,0
       0     .05       0   234.4    .016       0   246.8     .05       0
   271.8    .035       0   384.1     .07       0   391.9     .08       0
   433.8    .016       0   571.2     .08       0   754.4    .016       0
   779.2     .06       0  1049.5    .016       0  1087.9     .06       0
  1113.8     .05       0  1521.2     .06       0  1594.3    .016       0
  1614.2     .07       0  1722.4      .1       0
#XS Ineff= 2 , 0
                          733.22         2765.36
Permanent Ineff=
       F       F
#Block Obstruct= 1 ,-1
  775.65 1039.43 2777.45
Bank Sta=271.8,384.1
XS Rating Curve= 0 ,0
Exp/Cntr(USF)=0,0
Exp/Cntr=0.3,0.1

Type RM Length L Ch R = 1 ,13012   ,326.5,305.1,285.1
BEGIN DESCRIPTION:
channel burned 2.44':
lidar invert = 2748.44
effective invert = 2746
END DESCRIPTION:
XS GIS Cut Line= 2
2313214.04452172563102.9759198142313848.72370362 564848.34367004
#Sta/Elev= 30
       0 2784.86   223.7  2778.6   257.7 2777.17     262 2776.82   287.7 2750.23
   291.8 2746.05   359.2    2746   364.1 2746.15   368.4 2750.17   385.4 2754.09
   462.2 2750.11   500.3 2752.17   517.4 2748.44   534.4 2748.27   561.9  2752.6
   640.8 2752.55   662.1 2755.65  1164.3 2752.41  1351.8 2752.31  1444.8 2755.28
  1539.5 2753.36  1615.5  2760.4  1670.8 2770.45  1683.6 2776.35  1687.8 2778.56
  1720.1  2780.5  1726.3 2781.25  1750.2 2797.53    1790 2813.66  1857.2 2844.05
#Mann= 11 ,-1,0
       0     .05       0   223.7    .016       0   257.7     .08       0
   287.7    .035       0   368.4      .1       0   534.4     .08       0
   662.1     .06       0  1683.6     .07       0  1687.8    .016       0
  1720.1     .08       0    1790      .1       0
#XS Ineff= 2 , 0
                         1427.61         2765.75
Permanent Ineff=
       F       F
Bank Sta=287.7,368.4
XS Rating Curve= 0 ,0
Exp/Cntr(USF)=0,0
Exp/Cntr=0.3,0.1

Type RM Length L Ch R = 1 ,12707   ,371.4,365.8,142.8
BEGIN DESCRIPTION:
channel burned 2.02':
lidar invert = 2747.11
interpolated invert = 2745.09
END DESCRIPTION:
Node Name=G
XS GIS Cut Line= 3
2312813.49305697 563243.735436832313090.78735551563595.571213479
  2313582.761111564815.069795254
#Sta/Elev= 30
       0 2796.44    17.1 2790.56    62.5 2782.37   190.3  2775.7   276.9 2777.43
   296.3 2777.61   307.7 2774.62   322.7 2758.25     339 2748.83   341.9 2745.56
   347.6 2745.09   407.4 2745.44   413.1 2748.82   449.7 2751.72   484.2 2746.91
     536 2746.78   619.3 2754.21   674.6 2752.01     773  2754.4   993.2 2752.99
  1088.1 2752.72  1424.5 2751.06  1510.8 2755.49  1593.6 2755.13  1618.6 2758.07
  1638.4 2764.62  1701.1 2768.73  1728.1 2774.66  1743.7 2781.48    1763 2782.44
#Mann= 11 ,-1,0
       0     .05       0   276.9    .016       0   296.3      .1       0
     339    .035       0   413.1      .1       0   674.6     .05       0
   993.2     .06       0  1088.1     .05       0  1638.4     .06       0
  1728.1     .07       0  1743.7    .016       0
#Block Obstruct= 1 ,-1
 1668.31 1704.21 2787.07
Bank Sta=339,413.1
XS Rating Curve= 0 ,0
Exp/Cntr(USF)=0,0
Exp/Cntr=0.3,0.1

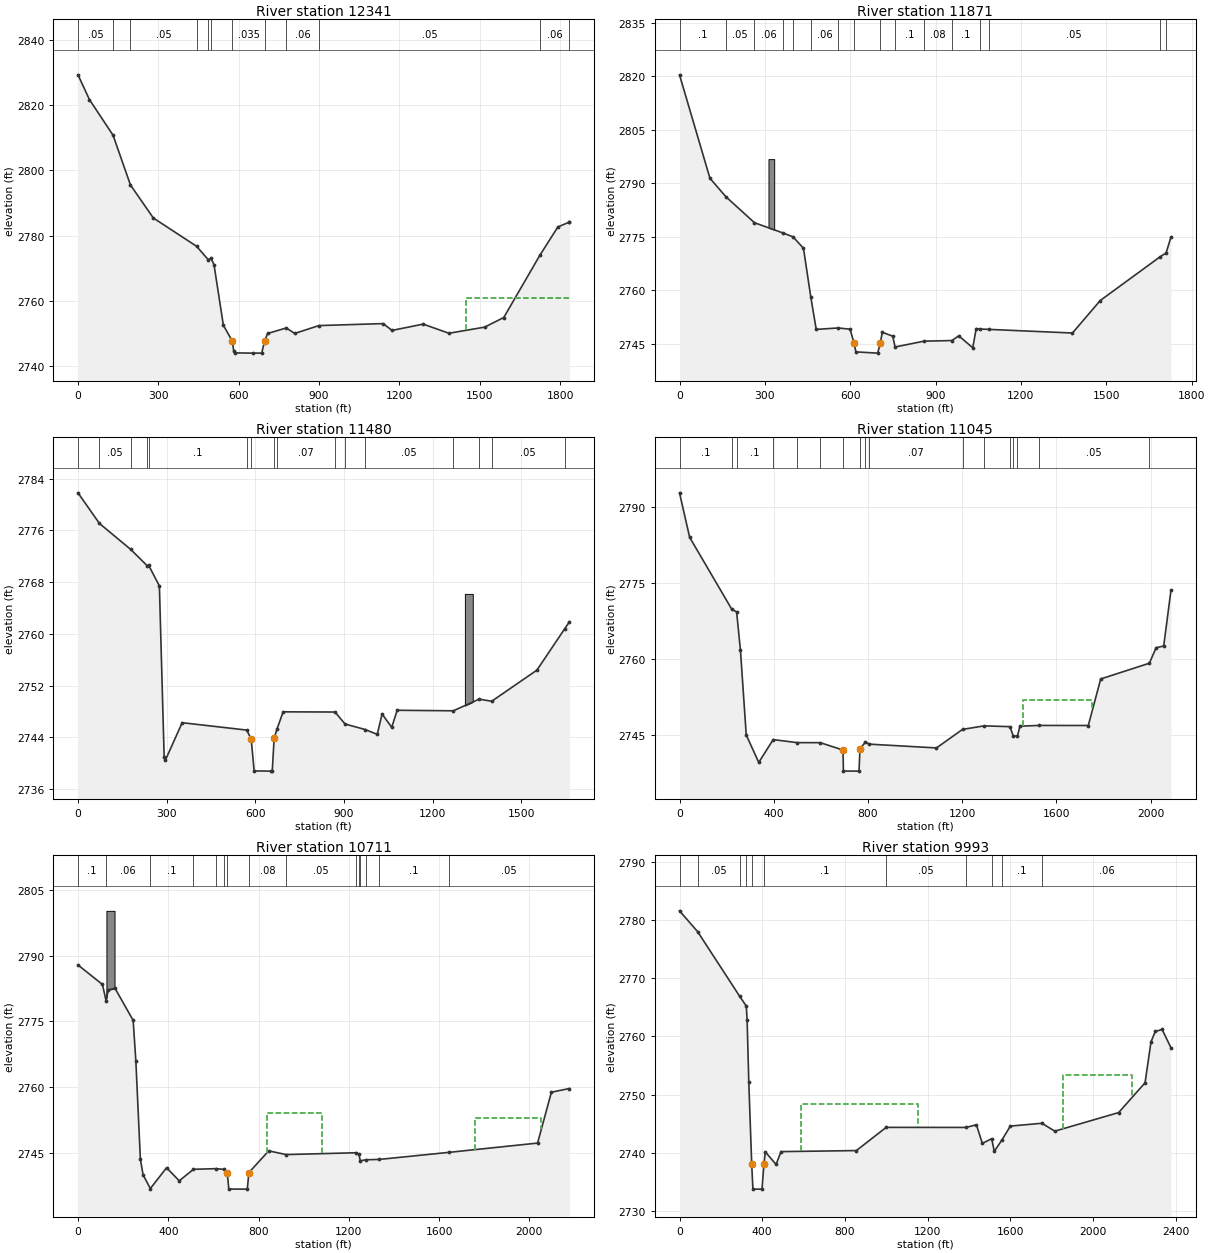
Type RM Length L Ch R = 1 ,12341   ,398.5,470.8,715
BEGIN DESCRIPTION:
channel burned 1.66':
lidar invert = 2745.66
effective invert = 2744
END DESCRIPTION:
XS GIS Cut Line= 4
 2312576.8751653563296.3695421112312779.17915453563781.304104533
2313171.88689833564150.2113790132313412.86665021564882.075810642
#Sta/Elev= 30
       0 2829.28    42.9 2821.67   130.9 2810.78   195.9 2795.52   281.4  2785.4
     443 2776.73   486.2 2772.63   496.9 2773.04   507.8 2771.12   542.8 2752.53
   576.2 2747.67   581.7 2744.52   587.2 2744.07   653.8    2744     686 2744.01
   696.9 2747.81   707.9 2750.02   777.9 2751.71     809 2750.03   899.6 2752.44
    1139 2753.05  1172.7 2750.96  1288.6 2752.89  1384.9 2750.09    1518 2751.96
  1589.6 2754.91  1724.3 2773.97  1791.7 2782.67  1834.4 2784.14  1834.8 2784.16
#Mann= 12 ,-1,0
       0     .05       0   130.9      .1       0   195.9     .05       0
     443     .06       0   486.2    .016       0   496.9      .1       0
   576.2    .035       0   696.9      .1       0   777.9     .06       0
   899.6     .05       0  1724.3     .06       0  1834.4     .07       0
#XS Ineff= 2 , 0
                         1447.89         2760.83
Permanent Ineff=
       F       F
Bank Sta=576.2,696.9
XS Rating Curve= 0 ,0
Exp/Cntr(USF)=0,0
Exp/Cntr=0.3,0.1

Type RM Length L Ch R = 1 ,11871   ,385.8,390.6,383.3
BEGIN DESCRIPTION:
channel burned 0.94':
lidar invert = 2743.34
effective invert = 2742.40
END DESCRIPTION:
XS GIS Cut Line= 4
2312432.70543962563442.2414918112312418.99070127563849.112062862
2312624.71177652564909.7184952652312761.85916002565106.296411616
#Sta/Elev= 30
       0 2820.46     107 2791.44     163 2786.27   263.4 2778.98   363.4 2776.11
   399.2 2775.01   435.7 2771.81   461.3 2758.19   480.5 2749.05   557.3 2749.46
   599.3 2749.12   613.52745.251   619.8 2742.75   696.5  2742.4  705.73 2745.26
   712.8 2748.25   749.4 2747.16   757.6 2744.12   859.4 2745.76   957.2 2745.93
   981.5 2747.24  1030.6 2743.91  1042.8 2749.28  1057.8 2749.16  1087.3 2749.06
    1381 2748.04  1478.8 2757.16  1687.8 2769.35  1710.2  2770.5  1727.2 2774.95
#Mann= 16 ,-1,0
       0      .1       0     163     .05       0   263.4     .06       0
   363.4      .1       0   399.2    .016       0   461.3     .06       0
   557.3      .1       0   613.5    .035       0  705.73     .08       0
   757.6      .1       0   859.4     .08       0   957.2      .1       0
  1057.8     .08       0  1087.3     .05       0  1687.8     .07       0
  1710.2     .06       0
#Block Obstruct= 1 ,-1
  312.66  332.82 2796.81
Bank Sta=613.5,705.73
XS Rating Curve= 0 ,0
Exp/Cntr(USF)=0,0
Exp/Cntr=0.3,0.1

Type RM Length L Ch R = 1 ,11480   ,438.3,434.5,481.3
BEGIN DESCRIPTION:
channel burned 3.42':
lidar invert = 2742.22
effective invert = 2738.8
END DESCRIPTION:
XS GIS Cut Line= 4
2311998.40539187563629.6762492612312094.40856032564201.123680513
2312245.27068217564941.7195514152312464.70649577565184.013262266
#Sta/Elev= 30
       0 2781.79    72.5 2777.06     178 2773.06   234.7  2770.5   238.8 2770.61
   275.3 2767.41   291.5 2740.92   295.6  2740.5   352.4 2746.28   570.6 2745.14
   585.92743.743   595.8 2738.83   652.2  2738.8   657.1 2738.81  663.44 2743.87
   673.4 2745.33   693.8 2747.96   869.5 2747.93   903.2 2746.08     971 2745.23
  1012.2 2744.48  1028.5 2747.62  1061.2 2745.57  1079.5  2748.2  1269.7 2748.12
  1356.8 2749.92  1399.2 2749.59  1552.2  2754.4  1645.6 2760.75  1662.2 2761.88
#Mann= 16 ,-1,0
       0      .1       0    72.5     .05       0     178     .06       0
   234.7    .016       0   238.8      .1       0   570.6     .08       0
   585.9    .035       0  663.44     .08       0   673.4     .07       0
   869.5     .05       0   903.2     .07       0     971     .05       0
  1269.7     .06       0  1356.8     .07       0  1399.2     .05       0
  1645.6     .07       0
#Block Obstruct= 1 ,-1
 1308.57 1335.26 2766.18
Bank Sta=585.9,663.44
XS Rating Curve= 0 ,0
Exp/Cntr(USF)=0,0
Exp/Cntr=0.3,0.1

Type RM Length L Ch R = 1 ,11045   ,253.5,334.6,409.5
BEGIN DESCRIPTION:
channel burned 3.51':
lidar invert = 2741.31
effective invert = 2737.80
END DESCRIPTION:
Node Name=F
XS GIS Cut Line= 5
2311618.96429752563510.8151835612311582.39166192563711.964679362
2311682.96640982564196.5521010632311660.10851257564283.412110613
2311870.40116727565563.454356617
#Sta/Elev= 30
       0 2792.88    43.1 2784.07     222 2769.83   242.5 2769.31   258.8 2761.68
   283.3 2744.96   336.4 2739.52   397.7 2744.04   499.8 2743.44   597.9 2743.43
   694.1 2741.97   695.9 2737.82   762.1  2737.8   766.2 2742.23   789.6 2743.56
   805.8 2743.14  1090.9 2742.39  1201.6 2746.06  1293.6 2746.76  1403.1  2746.6
    1417 2744.72  1434.9 2744.78  1445.3  2746.7  1524.7 2746.84  1735.5 2746.83
  1788.2 2756.04  1994.9 2759.16  2023.3 2762.22  2055.7 2762.57  2086.4 2773.55
#Mann= 17 ,-1,0
       0      .1       0     222    .016       0   242.5      .1       0
   397.7     .08       0   499.8      .1       0   597.9     .08       0
   694.1    .035       0   766.2     .07       0   789.6      .1       0
   805.8     .07       0  1201.6     .05       0  1293.6      .1       0
  1403.1     .05       0    1417     .04       0  1434.9     .07       0
  1524.7     .05       0  1994.9     .06       0
#XS Ineff= 1 ,-1
    1458 1751.812751.813
Permanent Ineff=
       F
Bank Sta=694.1,766.2
XS Rating Curve= 0 ,0
Exp/Cntr(USF)=0,0
Exp/Cntr=0.3,0.1

Type RM Length L Ch R = 1 ,10711   ,358,717.4,271.5
BEGIN DESCRIPTION:
channel burned 2.32':
lidar invert = 2738.97
interpolated invert = 2736.65
END DESCRIPTION:
XS GIS Cut Line= 4
2311398.35634047563481.0008420112311372.37810363564104.478526196
2311290.11368696564305.8098617142311552.06090844565615.545969116
#Sta/Elev= 30
       0 2787.91   108.3 2783.46   124.3 2779.76   132.3 2782.21   164.3 2782.54
   244.4 2775.25   256.4 2765.92   276.4 2743.47   288.4 2739.93   320.5 2736.78
   392.5 2741.54   448.6 2738.55   511.7 2741.19   612.7 2741.33   646.8 2741.17
   661.5 2740.45     668 2736.67   750.1 2736.65  757.12 2740.43   844.9  2745.4
   922.4 2744.55  1232.5 2744.97  1244.7 2744.57  1250.6 2743.13  1276.6 2743.37
  1334.5 2743.44  1643.7 2745.06  2036.1 2747.18  2097.3 2758.81  2177.2 2759.66
#Mann= 15 ,-1,0
       0      .1       0   124.3     .06       0   320.5      .1       0
   511.7     .08       0   612.7      .1       0   646.8     .07       0
   661.5    .035       0  757.12     .08       0   922.4     .05       0
  1232.5     .07       0  1244.7     .08       0  1250.6     .04       0
  1276.6     .05       0  1334.5      .1       0  1643.7     .05       0
#XS Ineff= 2 ,-1
  835.54 1079.652754.098  1759.9  2052.52752.829
Permanent Ineff=
       F       F
#Block Obstruct= 1 ,-1
  125.94   161.9 2800.29
Bank Sta=661.5,757.12
XS Rating Curve= 0 ,0
Exp/Cntr(USF)=0,0
Exp/Cntr=0.3,0.1

Type RM Length L Ch R = 1 ,9993    ,262.7,260.5,603.9
BEGIN DESCRIPTION:
channel burned 2.32':
lidar invert = 2736.06
interpolated invert = 2733.74
END DESCRIPTION:
XS GIS Cut Line= 5
2311262.12722038563459.8021896822311045.82375309563650.357286723
2311054.14470233563926.9605744492311257.64089091564762.593859502
2311486.38849347565686.887001767
#Sta/Elev= 30
       0  2781.6    87.4 2778.03   291.1  2766.9   323.1 2765.22   327.1 2762.74
   335.1 2752.21  349.22 2738.03   355.1 2733.74   399.1 2733.74  408.29 2737.99
   415.1 2740.14   467.2 2737.99   491.2 2740.19   855.5 2740.37   999.6 2744.36
  1386.2 2744.35  1436.1 2744.81  1464.8 2741.61  1510.1 2742.41  1522.5 2740.23
  1559.6 2742.19  1600.3 2744.58  1753.2 2745.07  1815.1 2743.71  2124.1  2746.9
    2252 2752.03  2280.7 2759.07  2301.4 2760.85  2334.4  2761.2  2377.2 2758.06
#Mann= 11 ,-1,0
       0     .07       0    87.4     .05       0   291.1    .016       0
   323.1      .1       0  349.22    .035       0  408.29      .1       0
   999.6     .05       0  1386.2      .1       0  1510.1     .04       0
  1559.6      .1       0  1753.2     .06       0
#XS Ineff= 2 ,-1
  589.67 1154.952748.362 1854.56 2190.19 2753.41
Permanent Ineff=
       F       F
Bank Sta=349.22,408.29
XS Rating Curve= 0 ,0
Exp/Cntr(USF)=0,0
Exp/Cntr=0.3,0.1