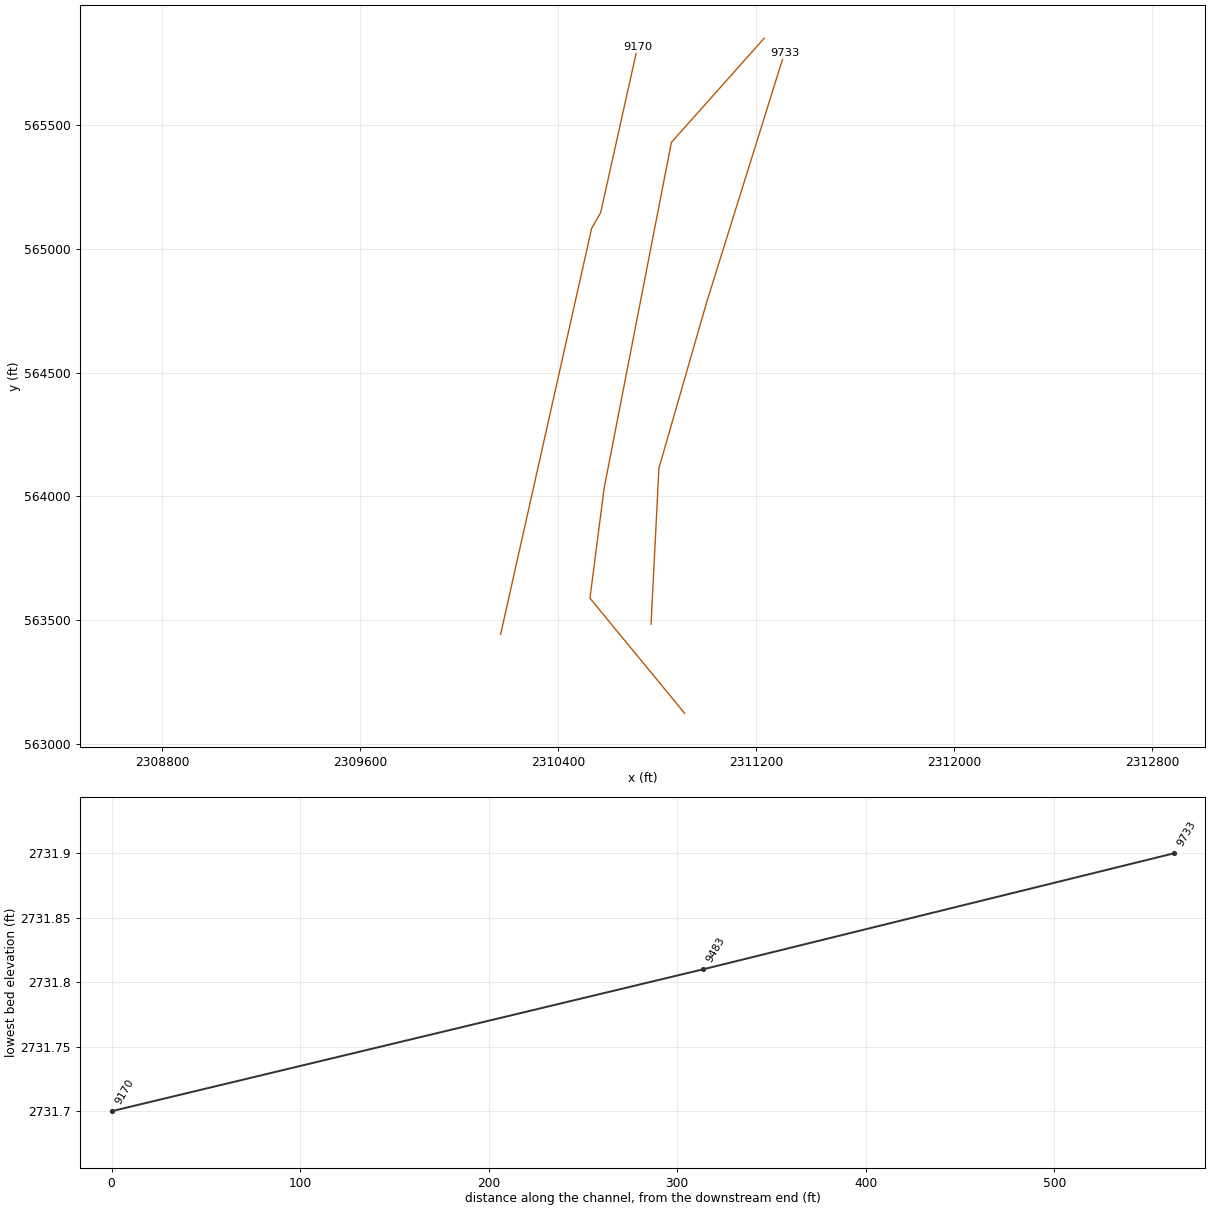
HEC-RAS study EFGRNBRRRV.prj: EFGRNBRRRV

--- EFGRNBRRRV.g01 (geometry) --- (continued)

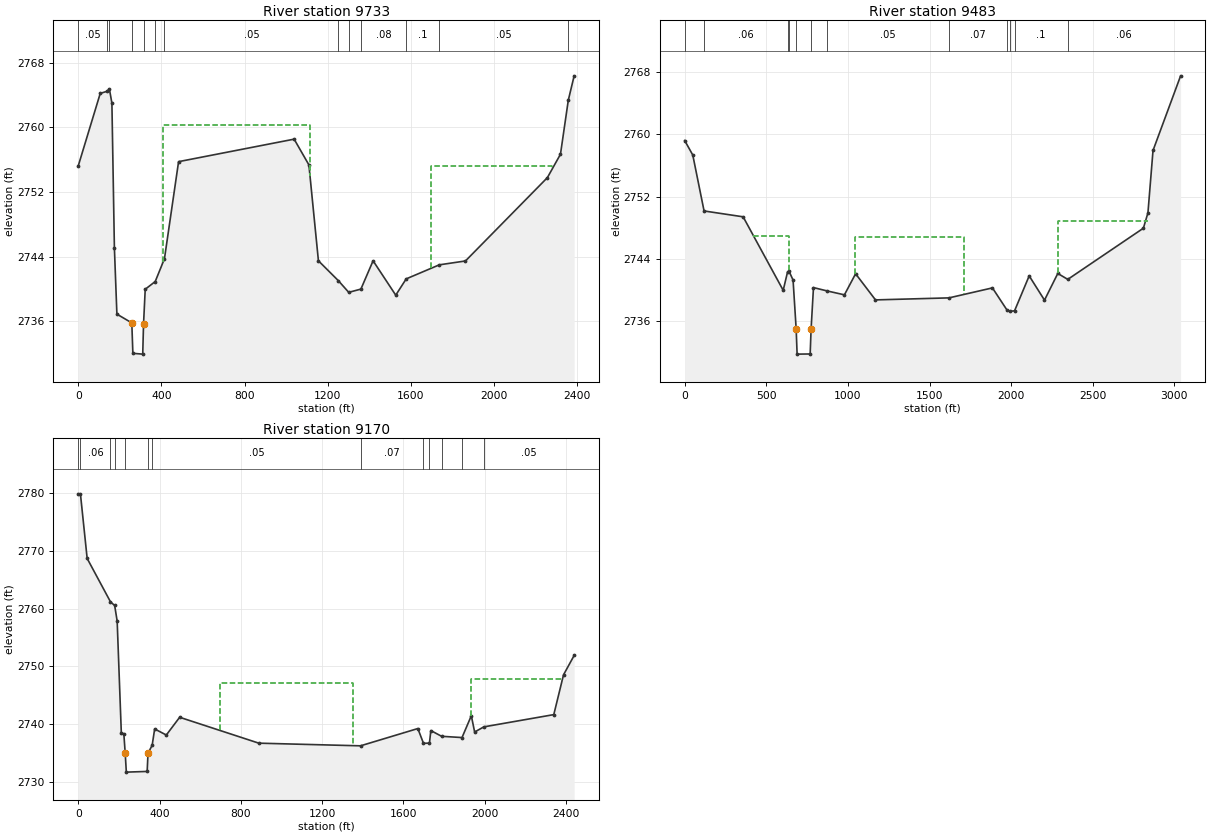
Type RM Length L Ch R = 1 ,9733    ,250,249.8,230.8
BEGIN DESCRIPTION:
channel burned 3.59':
lidar invert = 2735.49
effective invert = 2731.90
END DESCRIPTION:
XS GIS Cut Line= 4
2310775.50788899563483.3857068612310807.50894514564114.263670963
2310999.51528204564781.7142706652311314.95426409565792.033329118
#Sta/Elev= 30
       0 2755.22   105.9 2764.22     138 2764.48     150 2764.75     162 2763.02
     174 2745.05     186 2736.86   257.7 2735.77   262.8    2732   310.2  2731.9
   314.2 2735.68   322.2 2739.94   370.3  2740.9   414.7 2743.73   482.6 2755.76
  1038.2 2758.55  1109.2 2755.36    1155 2743.47  1250.7 2741.01  1300.7 2739.56
  1359.2 2739.96  1417.8 2743.47  1526.8 2739.21  1577.1 2741.23  1736.3 2742.97
    1862 2743.45  2255.9 2753.78  2318.8 2756.68  2356.5 2763.38  2384.6  2766.4
#Mann= 13 ,-1,0
       0     .05       0     138    .016       0     150     .08       0
   257.7    .035       0   314.2     .08       0   370.3     .07       0
   414.7     .05       0  1250.7     .08       0  1300.7     .04       0
  1359.2     .08       0  1577.1      .1       0  1736.3     .05       0
  2356.5     .06       0
#XS Ineff= 2 ,-1
  408.78 1114.46 2760.34 1695.35 2276.25 2755.17
Permanent Ineff=
       F       F
Bank Sta=257.7,314.2
XS Rating Curve= 0 ,0
Exp/Cntr(USF)=0,0
Exp/Cntr=0.3,0.1

Type RM Length L Ch R = 1 ,9483    ,323.1,313.5,301.2
BEGIN DESCRIPTION:
channel burned 3.12':
lidar invert = 2734.93
interpolated invert = 2731.81
END DESCRIPTION:
XS GIS Cut Line= 5
2310911.61362195563122.8495124882310528.64259869563588.532034211
2310585.78734181564031.9752408632310857.79631909565430.878552567
2311232.66583399565851.463861968
#Sta/Elev= 30
       0 2759.19    49.6 2757.33   118.8 2750.16   358.1 2749.41   603.6 2739.99
   630.6 2742.37   639.9 2742.41   664.1  2741.3  683.02 2735.04   688.8 2731.81
   768.9 2731.83  774.47 2735.01   789.1 2740.34   874.6  2739.9   978.7 2739.41
  1047.2 2742.11  1169.1 2738.76  1619.4 2739.02  1885.5  2740.3  1976.3 2737.41
  1994.7  2737.3  2021.1 2737.36  2110.7 2741.84  2204.5 2738.73    2286 2742.15
  2347.1 2741.39  2810.4 2747.95  2838.3 2749.92  2869.4 2757.91  3038.5 2767.48
#Mann= 12 ,-1,0
       0      .1       0   118.8     .06       0   630.6    .016       0
   639.9     .08       0  683.02    .035       0  774.47     .08       0
   874.6     .05       0  1619.4     .07       0  1976.3      .1       0
  1994.7     .04       0  2021.1      .1       0  2347.1     .06       0
#XS Ineff= 3 ,-1
     420   639.9    2747 1045.09 1712.722746.824 2285.97 2837.35 2748.93
Permanent Ineff=
       F       F       F
Bank Sta=683.02,774.47
XS Rating Curve= 0 ,0
Exp/Cntr(USF)=0,0
Exp/Cntr=0.5,0.3

Type RM Length L Ch R = 1 ,9170    ,250.4,246.5,252.8
BEGIN DESCRIPTION:
channel burned 2.07':
lidar invert =2733.77
effective invert = 2721.70
END DESCRIPTION:
Node Name=E
XS GIS Cut Line= 4
2310167.48782214563442.2414918112310535.49996786565083.438514366
2310572.07260346565147.4406266662310720.64893559565814.891226368
#Sta/Elev= 30
       0 2779.85    11.2 2779.75      44 2768.67   158.8 2761.16   179.3 2760.53
   191.6 2757.84   212.1 2738.44   224.4 2738.35  231.14 2734.98   236.7  2731.7
   339.2 2731.82   343.3 2734.96   363.8 2736.35     376 2739.17   433.4 2738.12
     499 2741.19   888.5 2736.71  1388.6 2736.25  1670.6 2739.24  1698.4 2736.68
  1727.7 2736.72  1734.6 2738.89  1787.4  2737.9  1887.9 2737.68  1933.7 2741.46
    1950 2738.64  1995.2 2739.53  2339.3 2741.65  2387.3 2748.54  2439.5 2751.89
#Mann= 13 ,-1,0
       0    .016       0    11.2     .06       0   158.8    .016       0
   179.3     .08       0  231.14    .035       0   343.3      .1       0
   363.8     .05       0  1388.6     .07       0  1698.4     .04       0
  1727.7     .07       0  1787.4     .08       0  1887.9      .1       0
  1995.2     .05       0
#XS Ineff= 2 ,-1
  696.66 1353.94 2747.08 1933.66 2379.52  2747.8
Permanent Ineff=
       F       F
Bank Sta=231.14,343.3
XS Rating Curve= 0 ,0
Exp/Cntr(USF)=0,0
Exp/Cntr=0.3,0.1