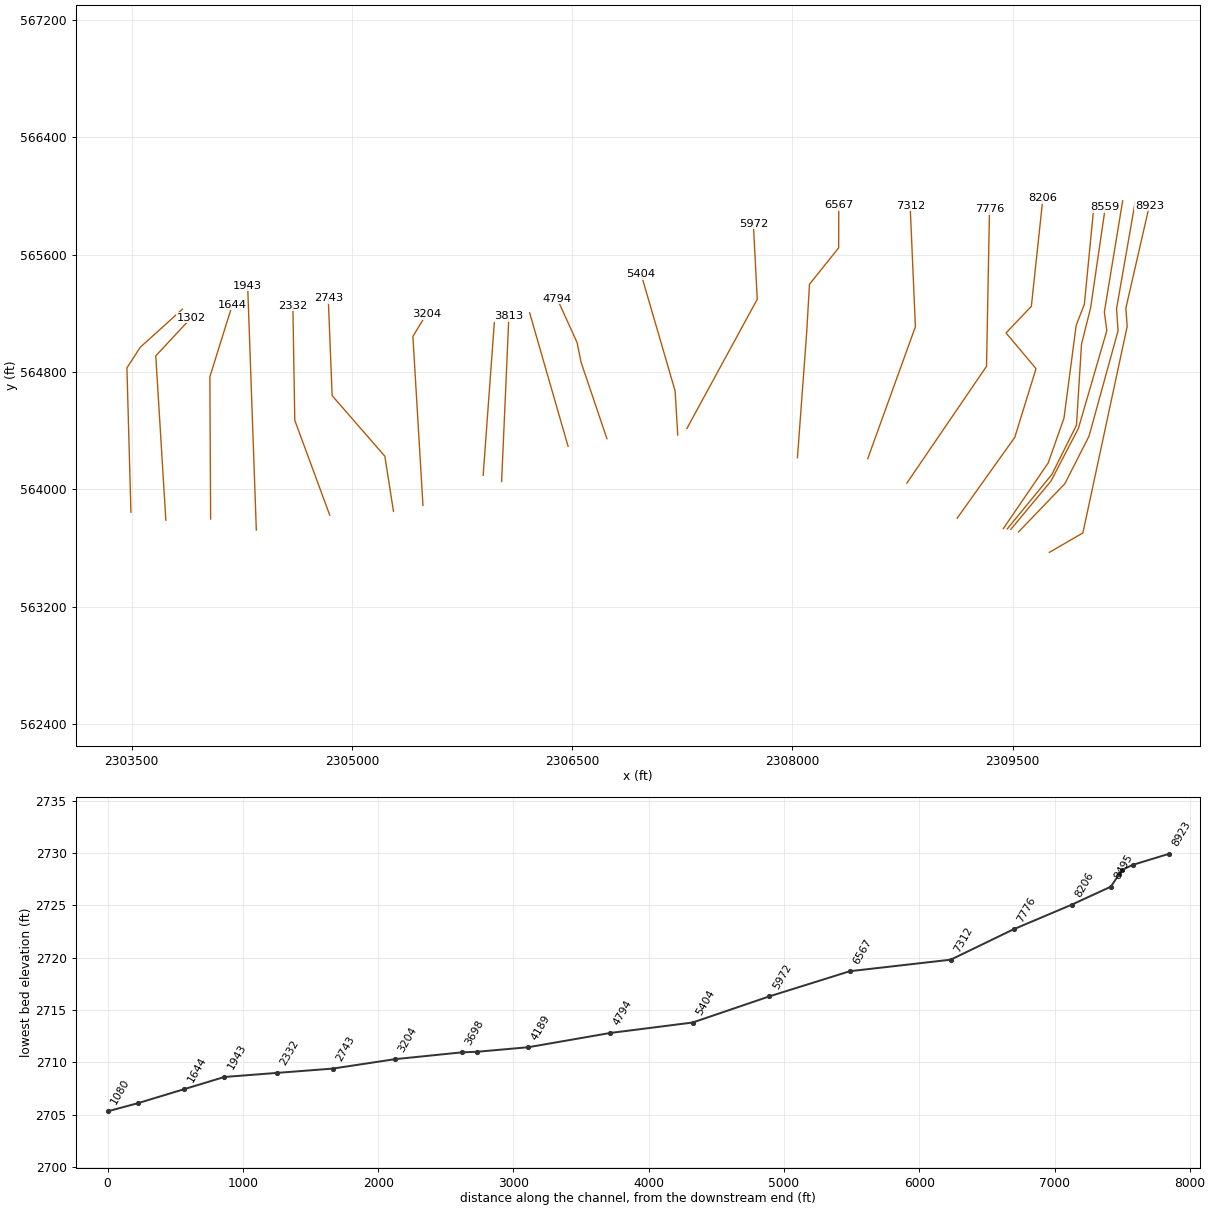
HEC-RAS study EFGRNBRRRV.prj: EFGRNBRRRV

--- EFGRNBRRRV.g01 (geometry) --- (continued)

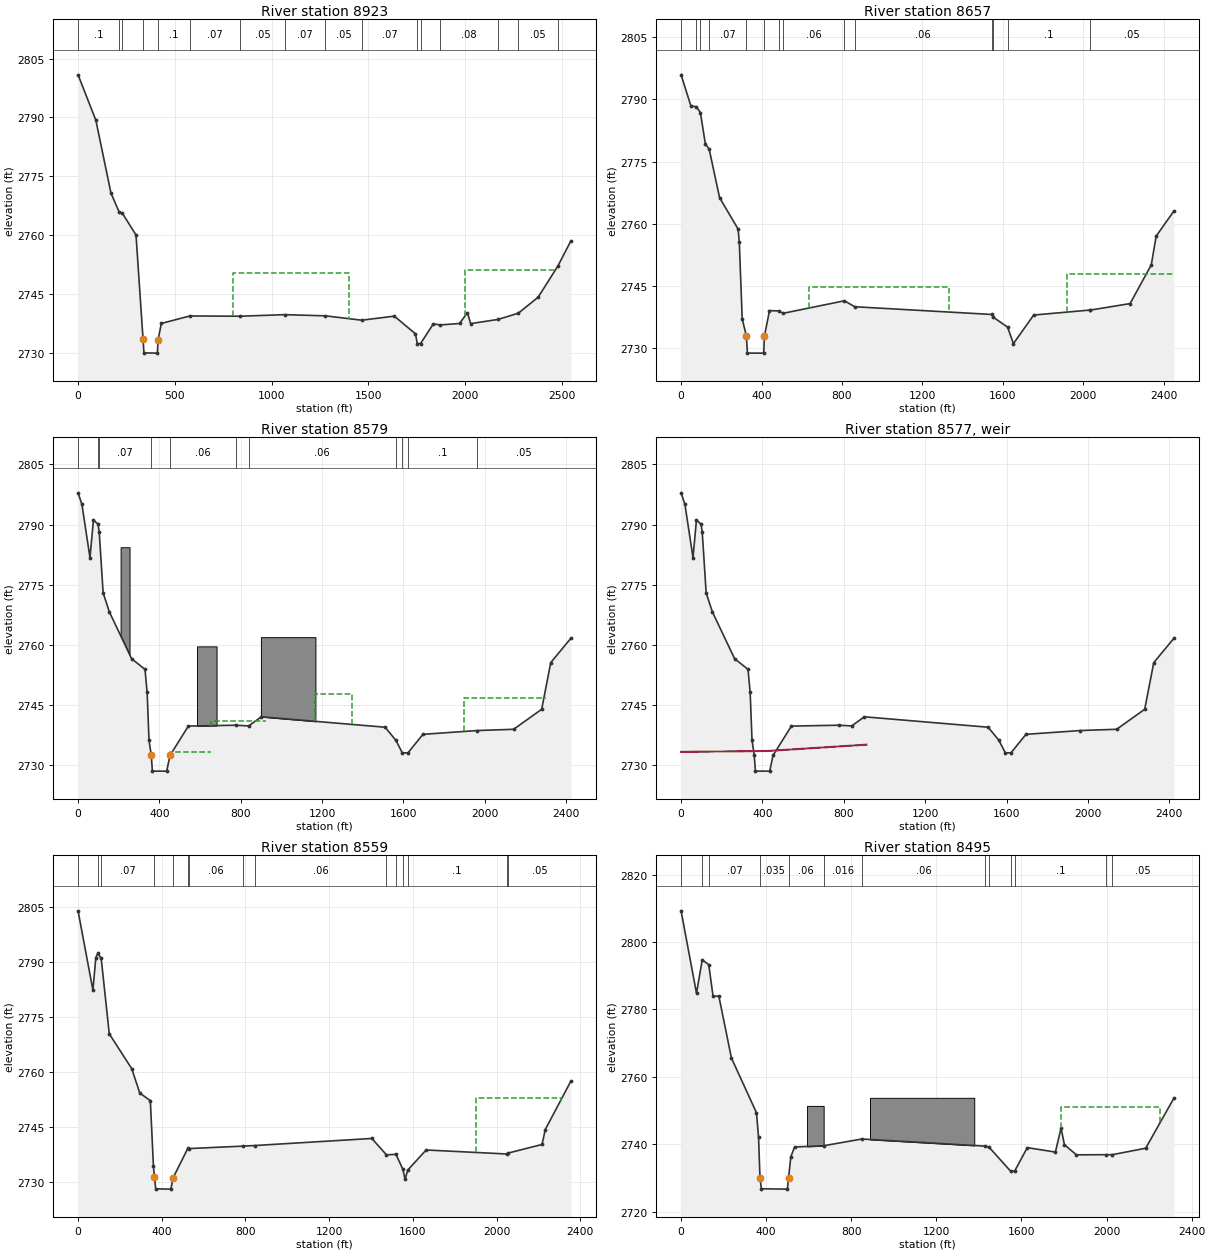
Type RM Length L Ch R = 1 ,8923    ,295.7,266.1,190.5
BEGIN DESCRIPTION:
channel burned 2.66':
lidar invert = 2732.56
interpolated invert = 2729.90
END DESCRIPTION:
XS GIS Cut Line= 5
2309749.18830246563570.2457164112309977.76727496563702.821520461
2310279.49151866565110.8679910662310270.34835976565234.300636216
2310430.35364051565933.752292068
#Sta/Elev= 30
       0 2800.87    92.1 2789.27   169.9 2770.73   211.5 2765.97   229.1 2765.55
   299.4 2760.03   335.6 2733.53   340.3 2729.96   409.8  2729.9   413.1 2733.18
     430 2737.46   577.6 2739.38   836.9 2739.31  1068.5 2739.71  1277.1 2739.41
  1465.3  2738.3  1633.5 2739.33  1742.7 2734.83  1752.3 2732.35  1769.3 2732.35
  1835.1 2737.35    1872 2737.09  1970.5 2737.46  2011.5 2740.22  2027.9 2737.43
  2169.2 2738.49  2274.1 2740.08  2376.7 2744.17  2478.5 2752.12  2545.5 2758.51
#Mann= 16 ,-1,0
       0      .1       0   211.5    .016       0   229.1      .1       0
   335.6    .035       0   413.1      .1       0   577.6     .07       0
   836.9     .05       0  1068.5     .07       0  1277.1     .05       0
  1465.3     .07       0  1752.3     .04       0  1769.3     .07       0
    1872     .08       0  2169.2      .1       0  2274.1     .05       0
  2478.5     .06       0
#XS Ineff= 2 ,-1
  802.37 1397.152750.432  1999.2 2468.16 2751.17
Permanent Ineff=
       F       F
Bank Sta=335.6,413.1
XS Rating Curve= 0 ,0
Exp/Cntr(USF)=0,0
Exp/Cntr=0.3,0.1

Type RM Length L Ch R = 1 ,8657    ,72.8,77.9,90.5
BEGIN DESCRIPTION:
XS 4 - inline, channel burned 2.74'
interpolated invert = 2728.85
lidar invert = 2731.59
END DESCRIPTION:
XS GIS Cut Line= 6
2309539.60224493563709.9203538062309854.55393605564037.779901121
2310019.77449533564363.0578771982310217.26469509565080.734681558
2310206.93841013565230.4658134032310333.43540083565955.887331479
#Sta/Elev= 30
       0 2795.93    48.9 2788.43    75.9 2788.25    96.1 2786.84     121  2779.2
   139.4 2778.07   191.4 2766.33   283.7 2758.74   289.5 2755.59     304 2737.09
  324.48 2733.04   329.9 2728.86   410.8 2728.85  414.77 2733.01   439.6 2739.09
   484.7 2739.02   507.8 2738.45   811.5 2741.46   863.8 2740.03  1543.8 2738.17
  1551.8 2737.52  1623.4 2735.12  1652.5 2731.14  1753.2 2738.03  2035.4 2739.24
  2035.4 2739.23  2232.5 2740.79  2337.9 2750.11  2362.3 2757.06  2450.3  2763.1
#Mann= 14 ,-1,0
       0      .1       0    75.9    .016       0    96.1      .1       0
   139.4     .07       0  324.48    .035       0  414.77     .06       0
   484.7    .016       0   507.8     .06       0   811.5    .016       0
   863.8     .06       0  1543.8      .1       0  1551.8     .04       0
  1623.4      .1       0  2035.4     .05       0
#XS Ineff= 2 ,-1
  634.38 1331.062744.694 1919.67  2450.3    2748
Permanent Ineff=
       F       F
Bank Sta=324.48,414.77
XS Rating Curve= 0 ,0
Exp/Cntr(USF)=0,0
Exp/Cntr=0.5,0.3

Type RM Length L Ch R = 1 ,8579    ,19.3,19.5,16.6
BEGIN DESCRIPTION:
inline structure xs 3
channel burned per surveyed cross section points - channel elevation = 2728.375
per FIS report - invert = 2729.75 at the weir
interpolated elevations at this point is 2727.38
END DESCRIPTION:
XS GIS Cut Line= 6
2309487.08544999 563727.530062442309760.10079205564055.603111685
2309947.40438912564415.9447079212310140.73207167565081.384194945
2310123.92096884565208.8683914072310248.60331482565966.768943996
#Sta/Elev= 30
       0 2797.92      19 2795.03    58.6 2781.72    75.6 2791.11    98.3 2790.09
     104 2788.17   123.3 2772.92   153.7 2768.19   263.2 2756.47   329.1 2753.81
   339.7 2748.04   348.8 2736.14   359.8 2732.33   365.52728.375   435.72728.375
   452.22732.306   542.3 2739.63   776.2 2739.85   838.8 2739.67   901.2 2741.95
  1509.5 2739.35  1562.6 2736.08  1594.3 2732.93  1622.3 2732.96  1695.7 2737.57
  1963.2 2738.52  2141.6 2738.83  2279.4 2743.83    2324 2755.49  2422.9 2761.57
#Mann= 11 ,-1,0
       0      .1       0    98.3    .016       0     104     .07       0
   359.8    .035       0   452.2     .06       0   776.2    .016       0
   838.8     .06       0  1562.6      .1       0  1594.3     .04       0
  1622.3      .1       0  1963.2     .05       0
#XS Ineff= 5 ,-1
       0     357 2733.17     454     655 2733.17  655.35  924.96 2741.01
 1167.08 1348.182747.725  1898.4 2302.07 2746.73
Permanent Ineff=
       F       F       F       F       F
#Block Obstruct= 3 ,-1
   209.2  253.15 2784.33  584.95  681.03 2759.55     899 1167.12 2761.85
Bank Sta=359.8,452.2
XS Rating Curve= 0 ,0
Exp/Cntr(USF)=0,0
Exp/Cntr=0.5,0.3

Type RM Length L Ch R = 5 ,8577    ,,,
BEGIN DESCRIPTION:
Bridge 54075EFG030
inline weir top of weir elevations taken from survey
channel invert dropped per survey data point
full survey was not taken at this cross section
END DESCRIPTION:
IW Pilot Flow=0
#Inline Weir SE= 3
       02733.178     4272733.415     9112734.983
IW Dist,WD,Coef,Skew,MaxSub,Min_El,Is_Ogee,SpillHt,DesHd
2,5,2.6,0,0.98,, 0 ,,,0,0,
Inline Weir Flap Gates= 0
IW Outlet Rating Curve= 0 ,False,,

Type RM Length L Ch R = 1 ,8559    ,62.4,64,61.3
BEGIN DESCRIPTION:
inline xs 2, channel burned 3.2'
intepolated invert = 2728.00
lidar invert = 2731.02
END DESCRIPTION:
XS GIS Cut Line= 6
2309462.86078672563730.5585727612309766.74833207564101.671805342
2309934.12657375564437.1142651072309968.42539377564990.011243777
 2310030.1632698565235.5907950972310130.31582425565921.567195433
#Sta/Elev= 30
       0 2803.85    70.9 2782.26      85 2791.07      94 2792.23   110.6  2790.9
   149.2 2770.33   256.7 2760.81   294.9  2754.2   345.5  2752.1   360.3 2734.28
     365 2731.35   371.2 2728.07   443.4    2728   454.8 2731.15   524.6 2739.11
   532.3 2739.06   788.5 2739.72   844.6 2739.88  1404.1 2741.81  1474.2 2737.34
  1519.4 2737.49  1552.4  2733.4  1562.9 2730.72  1576.1 2733.21  1663.8 2738.67
  2047.8 2737.58  2056.9 2737.85  2217.6 2740.17  2233.2 2744.25  2355.4 2757.43
#Mann= 15 ,-1,0
       0      .1       0      94    .016       0   110.6     .07       0
     365    .035       0   454.8     .06       0   524.6    .016       0
   532.3     .06       0   788.5    .016       0   844.6     .06       0
  1474.2    .016       0  1519.4     .08       0  1552.4     .04       0
  1576.1      .1       0  2047.8    .016       0  2056.9     .05       0
#XS Ineff= 3 ,-1
       0     359  2732.5     473     907  2732.5  1903.7 2306.372752.792
Permanent Ineff=
       F       F       F
Bank Sta=365,454.8
XS Rating Curve= 0 ,0
Exp/Cntr(USF)=0,0
Exp/Cntr=0.5,0.3

Type RM Length L Ch R = 1 ,8495    ,291.3,289.3,287.9
BEGIN DESCRIPTION:
channel burned 3.71':
lidar invert = 2730.48
effective invert = 2726.77
END DESCRIPTION:
XS GIS Cut Line= 6
2309436.03511013563732.5367868872309741.34073566564179.587747216
2309849.03358807564485.1409221412309932.16206924 565117.98609558
2309987.86107371565261.1376112572310051.49186189565917.061859492
#Sta/Elev= 30
       0 2809.24    72.5 2784.81    99.5 2794.73   130.1 2793.29   150.2 2783.98
   177.6 2783.94   236.6 2765.64   354.4  2749.4   364.1 2742.17  370.93 2729.98
   377.6 2726.88   499.7 2726.77  505.07 2730.04   515.8 2736.38   533.6 2739.26
   670.2 2739.62     849 2741.62  1430.2 2739.51  1446.9 2739.24  1549.3 2732.06
  1567.9 2732.11  1627.2 2739.07  1759.3 2737.75  1785.9 2744.84  1801.9 2739.91
  1858.2 2736.93  1998.9 2736.98    2027 2736.98  2183.7 2738.89  2316.2 2753.72
#Mann= 13 ,-1,0
       0      .1       0    99.5    .016       0   130.1     .07       0
  370.93    .035       0  505.07     .06       0   670.2    .016       0
     849     .06       0  1430.2    .016       0  1446.9      .1       0
  1549.3     .04       0  1567.9      .1       0  1998.9    .016       0
    2027     .05       0
#XS Ineff= 1 ,-1
 1785.71 2250.43 2751.22
Permanent Ineff=
       F
#Block Obstruct= 3 ,-1
     227     265 2751.44     592   670.1 2751.44     888    1378 2753.83
Bank Sta=370.93,505.07
XS Rating Curve= 0 ,0
Exp/Cntr(USF)=0,0
Exp/Cntr=0.3,0.1

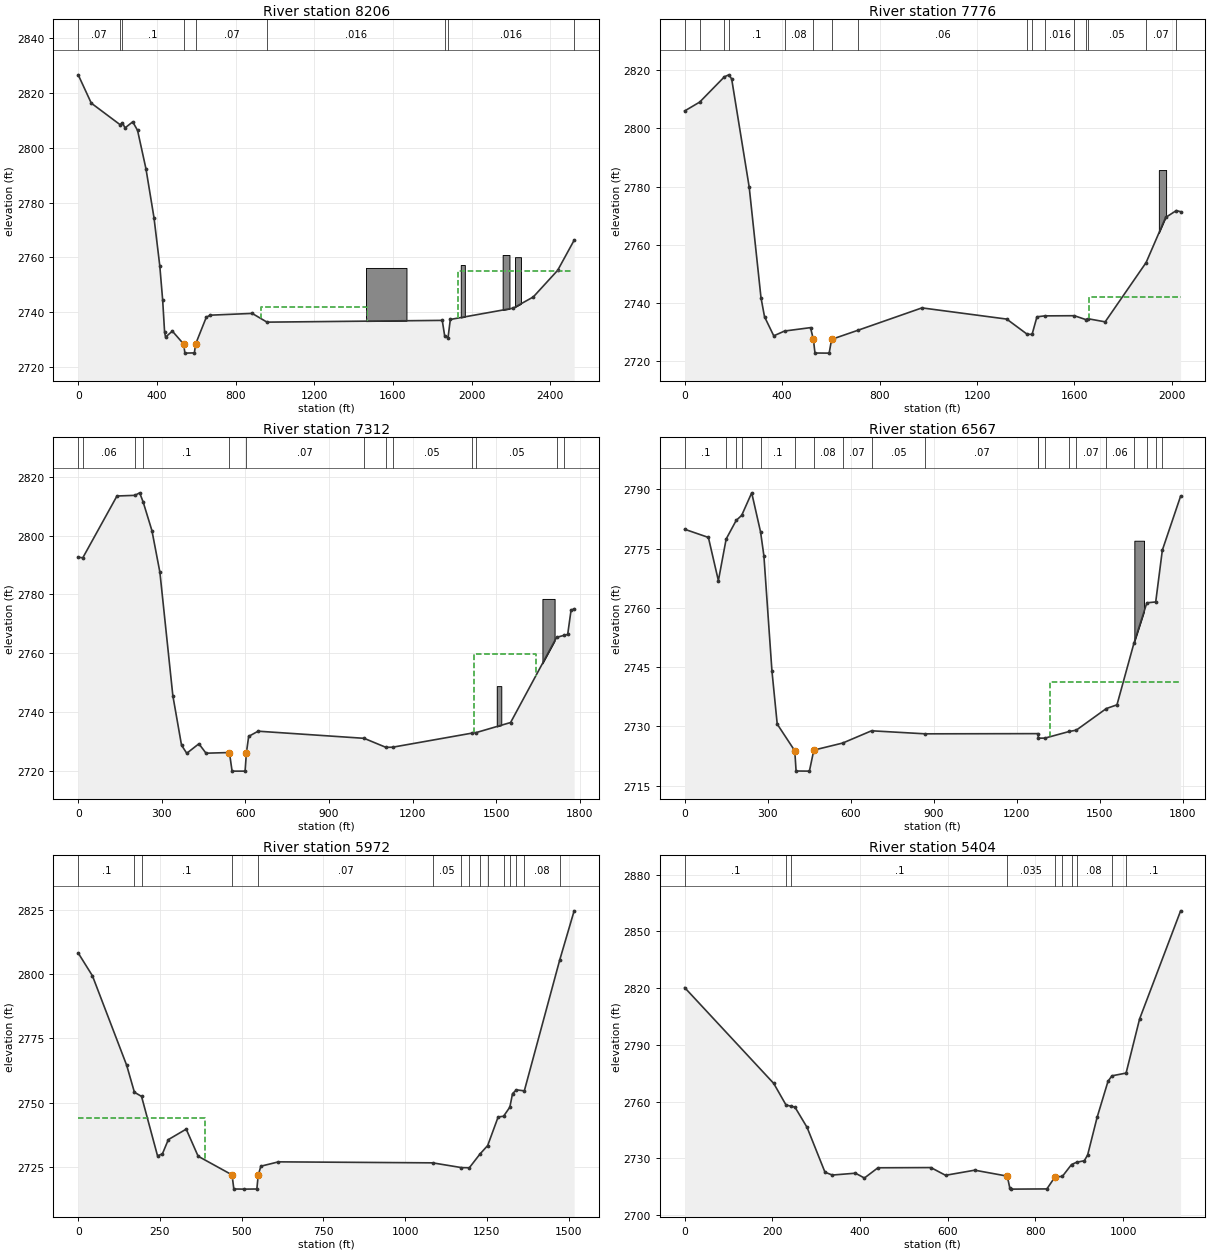
Type RM Length L Ch R = 1 ,8206    ,429.2,429.9,431.3
BEGIN DESCRIPTION:
channel burned 3.77':
lidar invert = 2728.84
interpolated invert = 2725.07
xs cut across structure located along JOHNSRN
END DESCRIPTION:
XS GIS Cut Line= 6
2309121.67897949563803.3512139432309513.91743941564354.398416161
2309658.73508498 564822.722397712309454.44545084565065.792970175
2309626.82524448565247.2858666732309705.54908237565984.816254538
#Sta/Elev= 30
       0 2826.62    66.4 2816.29   213.4  2808.4     225 2809.12   237.9 2807.24
   277.2 2809.46   301.7 2806.35   344.4 2792.35   385.2 2774.53   414.7 2756.94
   429.4  2744.4   439.1 2732.83   444.1 2730.89   478.5 2733.09  536.39 2728.33
   542.3 2725.05   590.6 2725.14  597.23 2728.42   651.3 2738.16   671.4  2738.9
   884.5 2739.55   959.8 2736.36  1850.9    2737  1863.2 2731.35  1880.4 2730.75
  1891.9 2737.34  2211.3 2741.46  2313.7 2745.55  2437.8 2755.28  2521.5 2766.27
#Mann= 9 ,-1,0
       0     .07       0   213.4    .016       0     225      .1       0
  536.39    .035       0  597.23     .07       0   959.8    .016       0
  1863.2     .04       0  1880.4    .016       0  2521.5     .06       0
#XS Ineff= 2 ,-1
     930 1470.352741.743 1929.03 2507.35 2754.98
Permanent Ineff=
       F       F
#Block Obstruct= 4 ,-1
    1463    1669 2756.14    1945  1965.7  2757.2    2158  2192.6 2760.87
  2220.8  2251.1 2760.07
Bank Sta=536.39,597.23
XS Rating Curve= 0 ,0
Exp/Cntr(USF)=0,0
Exp/Cntr=0.3,0.1

Type RM Length L Ch R = 1 ,7776    ,419.2,464.1,476.9
BEGIN DESCRIPTION:
channel burned 3.95':
lidar invert = 2726.65
effective invert = 2722.70
END DESCRIPTION:
XS GIS Cut Line= 3
2308779.07264956564042.2223546552309321.53234276564838.685226585
2309341.95331804565910.817465934
#Sta/Elev= 30
       0    2806    61.7 2809.05   163.3 2817.76   181.4 2818.42   192.9 2817.01
   264.9 2779.79   313.3 2741.76   327.8 2735.21   365.7 2728.65   410.1  2730.3
   516.6 2731.47  528.44  2727.4   534.9 2722.74   593.1  2722.7  603.23 2727.44
   710.2 2730.53   974.1 2738.26    1322 2734.41  1406.2 2729.19  1426.2 2729.15
  1446.2 2735.19  1478.2 2735.51  1599.7 2735.57  1646.3 2734.25  1654.3 2734.55
  1726.3 2733.46  1894.3 2753.85  1974.3 2769.35  2018.3 2771.73    2036 2771.34
#Mann= 16 ,-1,0
       0      .1       0    61.7     .07       0   163.3    .016       0
   181.4      .1       0   410.1     .08       0  528.44    .035       0
  603.23     .08       0   710.2     .06       0  1406.2     .04       0
  1426.2     .05       0  1478.2    .016       0  1599.7     .07       0
  1646.3    .016       0  1654.3     .05       0  1894.3     .07       0
  2018.3    .016       0
#XS Ineff= 2 , 0
                         1659.44         2741.94
Permanent Ineff=
       F       F
#Block Obstruct= 1 ,-1
 1946.64 1976.44 2785.66
Bank Sta=528.44,603.23
XS Rating Curve= 0 ,0
Exp/Cntr(USF)=0,0
Exp/Cntr=0.3,0.1

Type RM Length L Ch R = 1 ,7312    ,602.6,745.5,651.2
BEGIN DESCRIPTION:
channel burned 5.54':
lidar invert = 2725.34
effective invert = 2719.80
END DESCRIPTION:
XS GIS Cut Line= 3
2308512.94502869564209.712552316 2308837.2264232565108.180269195
2308801.52571921565932.271519444
#Sta/Elev= 30
       0 2792.72    16.4  2792.5   139.1 2813.57   203.6 2813.79   220.6 2814.65
   233.3 2811.47   264.6 2801.77   293.2 2787.58   339.6 2745.56   370.8 2728.65
   389.6 2725.88   433.2 2729.12   458.7 2725.91  542.73 2726.14   552.3  2719.8
     599  2719.8  603.692726.059   611.8 2731.64   645.8 2733.41  1026.2 2730.98
  1104.3 2727.91  1128.4 2727.95  1412.6 2732.74  1428.1 2732.93    1552 2736.37
  1716.9 2765.38  1744.9 2766.11  1756.9 2766.39    1769 2774.66  1780.1  2775.1
#Mann= 13 ,-1,0
       0      .1       0    16.4     .06       0   203.6    .016       0
   233.3      .1       0  542.73    .035       0  603.69     .07       0
  1026.2     .05       0  1104.3     .04       0  1128.4     .05       0
  1412.6    .016       0  1428.1     .05       0  1716.9    .016       0
  1744.9     .05       0
#XS Ineff= 1 ,-1
 1421.69    16422759.879
Permanent Ineff=
       F
#Block Obstruct= 2 ,-1
  1502.5 1518.57 2748.77 1666.22 1709.89 2778.49
Bank Sta=542.73,603.69
XS Rating Curve= 0 ,0
Exp/Cntr(USF)=0,0
Exp/Cntr=0.3,0.1

Type RM Length L Ch R = 1 ,6567    ,620,594.4,478.6
BEGIN DESCRIPTION:
channel burned 4.08':
lidar invert = 2722.78
effective invert = 2718.70
END DESCRIPTION:
Node Name=D
XS GIS Cut Line= 5
 2308033.9605836564215.6626696462308097.23101623565074.067966527
2308115.96058882565397.8366524432308314.61843035565645.663555367
2308315.47981965565935.246578109
#Sta/Elev= 30
       0 2779.92    85.7 2777.85   121.8 2766.91   149.9 2777.45     186 2782.14
   206.1 2783.45   242.2 2789.14   274.3 2779.22   286.3 2773.18   315.3 2744.09
   334.4 2730.61  397.832723.847   402.6 2718.73   450.7  2718.7   466.7 2724.02
   571.1 2725.81   675.3 2728.91   869.4 2728.14  1276.5 2728.19  1278.6 2727.04
  1302.1 2727.06    1390 2728.74  1415.2 2729.07  1523.7 2734.54  1562.2 2735.48
  1623.4 2751.06  1670.2  2761.3  1702.2 2761.52  1726.2 2774.64  1792.2 2788.31
#Mann= 20 ,-1,0
       0      .1       0   149.9     .06       0     186    .016       0
   206.1      .1       0   274.3      .1       0  397.83    .035       0
   466.7     .08       0   571.1     .07       0   675.3     .05       0
   869.4     .07       0  1276.5     .05       0  1278.6     .04       0
  1302.1     .05       0    1390    .016       0  1415.2     .07       0
  1523.7     .06       0  1623.4     .06       0  1670.2    .016       0
  1702.2     .08       0  1726.2      .1       0
#XS Ineff= 2 , 0
                         1321.86         2741.34
Permanent Ineff=
       F       F
#Block Obstruct= 1 ,-1
 1624.99 1660.04 2777.02
Bank Sta=397.83,466.7
XS Rating Curve= 0 ,0
Exp/Cntr(USF)=0,0
Exp/Cntr=0.3,0.1

Type RM Length L Ch R = 1 ,5972    ,307.1,568,623
BEGIN DESCRIPTION:
channel burned 5.32':
lidar invert = 2721.62
effective invert = 2716.30
END DESCRIPTION:
XS GIS Cut Line= 3
2307281.27074132564414.9916002122307760.25518641  565295.6089651
2307733.76332265565809.396982694
#Sta/Elev= 30
       0 2808.31    43.5 2799.42   148.3 2764.53   171.9 2754.05   193.7 2752.43
   242.6 2729.28   257.4 2730.01   275.7  2735.6   330.3 2739.68   366.8 2729.12
  470.48 2721.85     476 2716.36   508.1  2716.3   546.4 2716.35  550.55 2721.68
   558.6 2725.23   612.6 2726.93    1084 2726.54  1172.2 2724.69  1196.3 2724.63
  1228.8 2729.97  1252.4 2733.29  1284.4 2744.41  1301.1 2744.71  1320.2 2748.25
  1328.5 2753.54  1340.5 2754.98  1364.5 2754.59  1472.5 2805.47  1516.9 2824.74
#Mann= 15 ,-1,0
       0      .1       0   171.9    .016       0   193.7      .1       0
  470.48    .035       0  550.55     .07       0    1084     .05       0
  1172.2     .04       0  1196.3     .07       0  1228.8    .016       0
  1252.4     .08       0  1301.1    .016       0  1320.2     .08       0
  1340.5    .016       0  1364.5     .08       0  1472.5      .1       0
#XS Ineff= 2 , 0
           388.3 2743.88
Permanent Ineff=
       F       F
Bank Sta=470.48,550.55
XS Rating Curve= 0 ,0
Exp/Cntr(USF)=0,0
Exp/Cntr=0.3,0.1

Type RM Length L Ch R = 1 ,5404    ,549.7,610.1,554.7
BEGIN DESCRIPTION:
channel burned 5.92':
lidar invert = 2719.72
effective invert = 2713.80
END DESCRIPTION:
XS GIS Cut Line= 3
2307218.79450935564370.3657202352307200.94415736564670.846645416
2306968.88958147565468.162367679
#Sta/Elev= 30
       0 2820.29   203.2 2769.64   231.2 2758.26   243.4 2757.59   251.6 2757.12
   279.3 2746.39   320.1 2722.73   336.8 2721.24   389.6 2722.22     410 2719.67
   440.9 2725.08   561.7 2725.19   595.1 2721.11   661.7 2723.81   735.9 2720.67
   741.9 2714.22     745  2713.8   826.3 2713.91     845 2720.29   861.5  2720.5
   882.5 2726.79     894 2727.99   911.7  2728.8   919.3 2731.86   940.8 2751.65
   965.8 2770.82   974.7 2773.67    1007 2775.12  1037.8 2803.71  1131.4 2860.86
#Mann= 10 ,-1,0
       0      .1       0   231.2    .016       0   243.4      .1       0
   735.9    .035       0     845     .04       0   861.5      .1       0
   882.5    .016       0     894     .08       0   974.7    .016       0
    1007      .1       0
Bank Sta=735.9,845
XS Rating Curve= 0 ,0
Exp/Cntr(USF)=0,0
Exp/Cntr=0.3,0.1

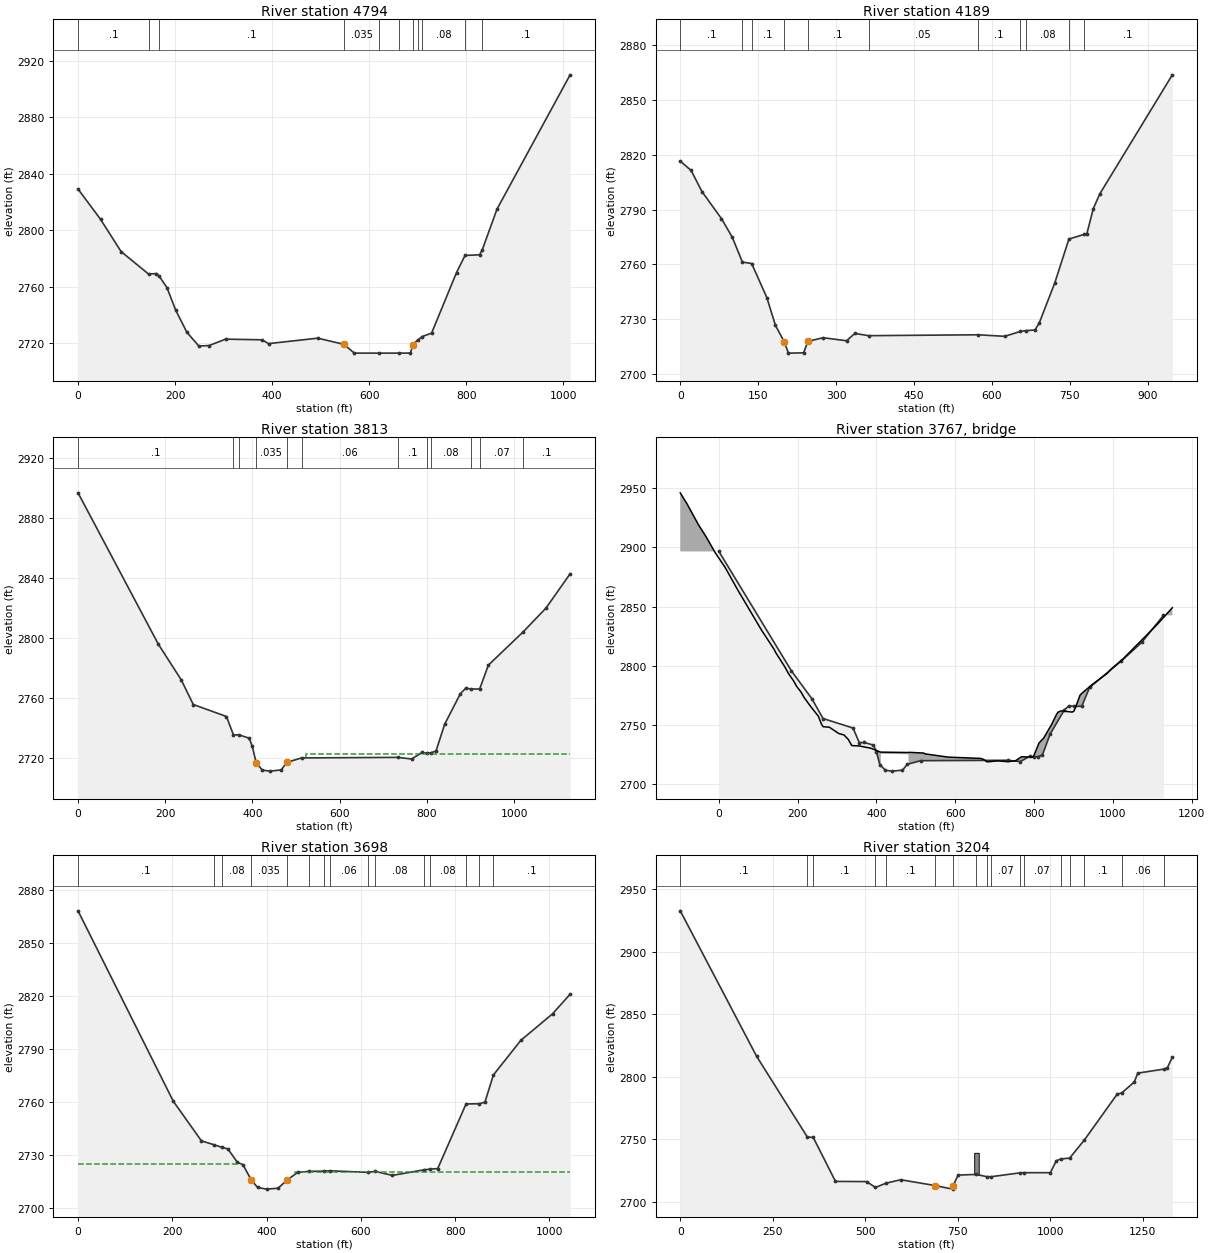
Type RM Length L Ch R = 1 ,4794    ,262.1,605.3,251.7
BEGIN DESCRIPTION:
channel burned 5.14':
lidar invert = 2717.94
effective invert = 2712.80
END DESCRIPTION:
Node Name=C
XS GIS Cut Line= 4
 2306736.5174449564345.1284331882306560.51163608 564866.28849049
2306533.08215938565001.150084265 2306398.2205656565298.302748516
#Sta/Elev= 30
       0 2829.17    46.5 2807.64    88.7 2784.84   145.5 2768.84   161.3 2769.23
   167.6 2767.23   183.4 2759.17   201.1 2743.38   224.4 2727.53   249.1 2717.79
   270.3  2718.2     304 2722.71     379 2722.25   392.7 2719.54     494 2723.41
   547.8 2719.01   569.4  2712.8   621.2  2712.8   661.3  2712.8   685.1 2712.85
   689.9 2718.85   699.6    2722   709.6 2724.58   728.6 2727.01     780 2769.96
   797.5 2782.08   827.4 2782.51   832.7 2785.79   863.4 2814.95    1014 2910.14
#Mann= 11 ,-1,0
       0      .1       0   145.5    .016       0   167.6      .1       0
   547.8    .035       0   621.2     .08       0   661.3    .035       0
   689.9     .06       0   699.6    .016       0   709.6     .08       0
   797.5    .016       0   832.7      .1       0
Bank Sta=547.8,689.9
XS Rating Curve= 0 ,0
Exp/Cntr(USF)=0,0
Exp/Cntr=0.3,0.1

Type RM Length L Ch R = 1 ,4189    ,385.1,375.6,248.7
BEGIN DESCRIPTION:
structure xs 4 - channel burned 4.27':
lidar invert = 2715.71
interpolated invert = 2711.44
END DESCRIPTION:
XS GIS Cut Line= 2
2306472.05478439 564293.014194942306210.24962186 565203.38214648
#Sta/Elev= 30
       0 2816.62      21  2811.5    41.8 2799.93    79.3 2785.15   100.1 2774.93
   119.6 2761.34   137.5 2760.52   166.7 2741.85   183.3 2726.61     200 2717.76
   208.3 2711.44   237.4 2711.59   245.7 2717.88   274.9 2719.88   320.1 2718.22
   336.2 2722.23   362.6    2721     573 2721.49   624.5 2720.65   654.7  2723.3
   666.1 2723.78   682.8 2724.11   691.1 2727.99   720.9 2749.81   748.2 2773.94
   777.4 2776.46   782.7 2776.81   795.2 2790.62   807.6 2798.66   947.3  2863.9
#Mann= 11 ,-1,0
       0      .1       0   119.6    .016       0   137.5      .1       0
     200    .035       0   245.7      .1       0   362.6     .05       0
     573      .1       0   654.7    .016       0   666.1     .08       0
   748.2    .016       0   777.4      .1       0
Bank Sta=200,245.7
XS Rating Curve= 0 ,0
Exp/Cntr(USF)=0,0
Exp/Cntr=0.5,0.3

Type RM Length L Ch R = 1 ,3813    ,117.7,115.6,116.2
BEGIN DESCRIPTION:
structure xs 3
channel burned per surveyed cross section points
effective invert = 2710.60
END DESCRIPTION:
XS GIS Cut Line= 2
2306019.43795922564053.150491121 2306069.0222703565180.367163142
#Sta/Elev= 30
       0 2896.51   184.2 2795.61   236.3 2772.03   264.3 2755.42   340.4 2747.41
   356.4 2735.08   368.9  2735.2   392.4 2732.97   399.6 2727.52   408.4 2716.59
  422.72 2711.66  440.35 2711.01  465.96 2711.81  478.25 2716.79   512.5 2719.81
   733.3 2720.17   764.8 2719.09   788.8 2723.43   800.8 2722.86     810 2723.31
   820.8  2724.4   840.8 2742.35   876.9 2762.75   888.9 2766.25   900.9 2765.79
   920.9 2765.74   940.9 2781.67  1020.9  2803.9  1073.1 2819.74  1128.3 2842.53
#Mann= 12 ,-1,0
       0      .1       0   356.4    .016       0   368.9     .08       0
   408.4    .035       0  478.25     .08       0   512.5     .06       0
   733.3      .1       0   800.8    .016       0     810     .08       0
   900.9    .016       0   920.9     .07       0  1020.9      .1       0
#XS Ineff= 2 , 0
             371 2727.19     522         2722.13
Permanent Ineff=
       F       F
Bank Sta=408.4,478.25
XS Rating Curve= 0 ,0
Exp/Cntr(USF)=0,0
Exp/Cntr=0.5,0.3

Type RM Length L Ch R = 3 ,3767    ,,,
BEGIN DESCRIPTION:
Bridge 54075EFG010
JV notes: road deck updated per surveyed XS data points
channel burned per surveyed cross sections
structure opening based on survey data, photos, and aerial imagery
surveyed inverts are approximately 3-5' below inverts from lidar:
 surveyed invert US is 2711.01
 surveyed invert DS is 2710.95
END DESCRIPTION:
Bridge Culvert--1,0,-1,-1, 0
Deck Dist Width WeirC Skew NumUp NumDn MinLoCord MaxHiCord MaxSubmerge Is_Ogee
40,15,2.6,0, 60, 60, , , 0.98, 0, 0,0,,
     -98  -80.26 -52.328 -32.281  -8.987  15.833  47.281  108.05 140.126 144.136
 168.192 176.211 189.827  197.33 208.287 216.306 232.344 252.391  260.41  264.42
 280.458 304.514 317.368 328.571 337.125 356.638     386   409.5  411.02  481.26
  483.17  520.26 521.924 581.649 664.092 672.302 680.302 708.302 732.302 752.302
 768.302 796.356 800.367 812.398 824.428  844.48 856.511 860.521 868.541 896.613
 900.624 904.634 916.665 920.675 948.747 984.542  996.871026.2581113.1691150.816
2946.0012936.3772919.3682908.8362895.3122883.0962864.3432830.1692813.8752811.165
 2798.592793.6022787.1022782.6032777.8462773.2132765.8342757.4242750.6822748.554
2748.0682742.7152741.5812737.7372732.6022732.265  2730.3 2727.19 2727.05 2726.73
 2726.88 2726.272725.6662722.836 2721.762720.8472718.8212719.6452719.0312719.688
 2723.172722.8032724.8132734.729 2739.012750.4342758.6622760.772  2761.9 2760.86
2761.5272764.3762775.1712776.586 2784.462793.2892797.5492805.9552835.1292848.998
                                                                                
                                                                                
                                                                 2725.56 2725.29
                                                                                
                                                                                
                                                                                
    -140 -122.26 -94.328 -74.281 -50.987 -26.167   5.281   66.05  98.126 102.136
 126.192 134.211 147.827  155.33 166.287 174.306 190.344 210.391  218.41  222.42
 238.458 262.514 275.368 286.571 295.125 314.638     344   367.5  369.02  439.26
  441.17  478.26 479.924 539.649 622.092 630.302 638.302 666.302 690.302 710.302
 726.302 754.356 758.367 770.398 782.428  802.48 814.511 818.521 826.541 854.613
 858.624 862.634 874.665 878.675 906.747 942.542  954.87 984.2581071.1691108.816
2946.0012936.3772919.3682908.8362895.3122883.0962864.3432830.1692813.8752811.165
 2798.592793.6022787.1022782.6032777.8462773.2132765.8342757.4242750.6822748.554
2748.0682742.7152741.5812737.7372732.6022732.265  2730.3 2727.19 2727.05 2726.73
 2726.88 2726.272725.6662722.836 2721.762720.8472718.8212719.6452719.0312719.688
 2723.172722.8032724.8132734.729 2739.012750.4342758.6622760.772  2761.9 2760.86
2761.5272764.3762775.1712776.586 2784.462793.2892797.5492805.9552835.1292848.998
                                                                                
                                                                                
                                                                 2725.56 2725.29
                                                                                
                                                                                
                                                                                
BR Coef=-1 ,-1 , 0 ,, 0 ,,,0.8,0,0.2,0,
WSPro=,,,, 1 ,,,, 0 ,,,, 0 ,,,,-1 ,-1 ,-1 , 0 , 0 , 0 , 0 , 0
BR U #Sta/Elev= 30
       0 2896.51   184.2 2795.61   236.3 2772.03   264.3 2755.42   340.4 2747.41
   356.4 2735.08   368.9  2735.2   392.4 2732.97   399.6 2727.52   408.4 2716.59
  422.72 2711.66  440.35 2711.01  465.96 2711.81  478.25 2716.79   512.5 2719.81
   733.3 2720.17   764.8 2719.09   788.8 2723.43   800.8 2722.86     810 2723.31
   820.8  2724.4   840.8 2742.35   876.9 2762.75   888.9 2766.25   900.9 2765.79
   920.9 2765.74   940.9 2781.67  1020.9  2803.9  1073.1 2819.74  1128.3 2842.53
BR U #Mann= 12
       0      .1   356.4    .016   368.9     .08   408.4     .03  478.25     .08
   512.5     .06   733.3      .1   800.8    .016     810     .08   900.9    .016
   920.9     .07  1020.9      .1
BR D #Sta/Elev= 30
       0 2868.41   201.9 2760.78   261.8 2738.25   288.5 2736.06   305.8 2734.54
   317.9 2733.72     338 2726.16     350 2724.74  367.82 2715.99  381.07 2711.89
  399.88 2710.95  424.21 2711.46   444.2  2716.2   466.3 2720.43   490.4 2721.01
   522.7 2721.13   535.1 2721.32   614.7 2720.46   631.1 2720.97   666.8 2718.72
     735 2721.91   746.3 2722.25   763.1 2722.57   823.2 2759.13   851.6 2759.27
   863.3 2760.16   881.2 2775.52   939.5 2795.15  1006.7 2810.13    1044 2821.23
BR D #Mann= 15
       0      .1   288.5    .016   305.8     .08  367.82     .03   444.2      .1
   490.4     .05   522.7    .016   535.1     .06   614.7    .016   631.1     .08
     735    .016   746.3     .08   823.2    .016   851.6     .07   881.2      .1
BC Design=,, 0 ,, 0 ,,,,,,
BC Use User HTab Curves=0
BC User HTab FreeFlow(D)= 0

Type RM Length L Ch R = 1 ,3698    ,474.2,494,536.6
BEGIN DESCRIPTION:
structure xs 2
channel burned per surveyed cross section points
END DESCRIPTION:
XS GIS Cut Line= 2
2305893.82437113564096.1235607292305969.85364813565137.394093535
#Sta/Elev= 30
       0 2868.41   201.9 2760.78   261.8 2738.25   288.5 2736.06   305.8 2734.54
   317.9 2733.72     338 2726.16     350 2724.74  367.82 2715.99  381.07 2711.89
  399.88 2710.95  424.21 2711.46   444.2  2716.2   466.3 2720.43   490.4 2721.01
   522.7 2721.13   535.1 2721.32   614.7 2720.46   631.1 2720.97   666.8 2718.72
     735 2721.91   746.3 2722.25   763.1 2722.57   823.2 2759.13   851.6 2759.27
   863.3 2760.16   881.2 2775.52   939.5 2795.15  1006.7 2810.13    1044 2821.23
#Mann= 15 ,-1,0
       0      .1       0   288.5    .016       0   305.8     .08       0
  367.82    .035       0   444.2      .1       0   490.4     .05       0
   522.7    .016       0   535.1     .06       0   614.7    .016       0
   631.1     .08       0     735    .016       0   746.3     .08       0
   823.2    .016       0   851.6     .07       0   881.2      .1       0
#XS Ineff= 2 , 0
           348.3  2725.4   459.7         2720.55
Permanent Ineff=
       F       F
Bank Sta=367.82,444.2
XS Rating Curve= 0 ,0
Exp/Cntr(USF)=0,0
Exp/Cntr=0.5,0.3

Type RM Length L Ch R = 1 ,3204    ,291.6,460.2,534.5
BEGIN DESCRIPTION:
structure xs 1 - channel burned 2.82':
lidar invert = 2713.12
effective invert = 2710.30
END DESCRIPTION:
XS GIS Cut Line= 3
 2305483.9046756563890.2562779122305415.33098385565042.294299315
2305506.76257285565193.156421166
#Sta/Elev= 30
       0 2932.78   206.7 2816.38   343.5 2752.01   359.6 2751.61   419.7 2716.48
   503.8 2716.31   527.9 2711.64   555.9 2715.02     596  2717.8  689.03 2713.17
   736.2  2710.3  738.01  2713.2   751.3 2721.52   800.2 2722.06   828.4 2720.29
   840.4 2720.22   919.4 2723.35   929.1 2723.45  1000.7 2723.45  1016.7 2732.94
  1028.7 2734.42  1052.8 2735.09  1092.9 2749.67  1180.8 2786.01  1194.3 2787.36
  1227.6 2795.94    1237 2803.02  1308.2 2806.28    1317  2807.3  1330.5 2815.79
#Mann= 17 ,-1,0
       0      .1       0   343.5    .016       0   359.6      .1       0
   527.9     .04       0   555.9      .1       0  689.03    .035       0
  738.01      .1       0   800.2     .07       0   828.4    .016       0
   840.4     .07       0   919.4    .016       0   929.1     .07       0
  1028.7    .016       0  1052.8     .08       0  1092.9      .1       0
  1194.3     .06       0  1308.2      .1       0
#Block Obstruct= 1 ,-1
  794.78  806.99 2739.33
Bank Sta=689.03,738.01
XS Rating Curve= 0 ,0
Exp/Cntr(USF)=0,0
Exp/Cntr=0.3,0.1

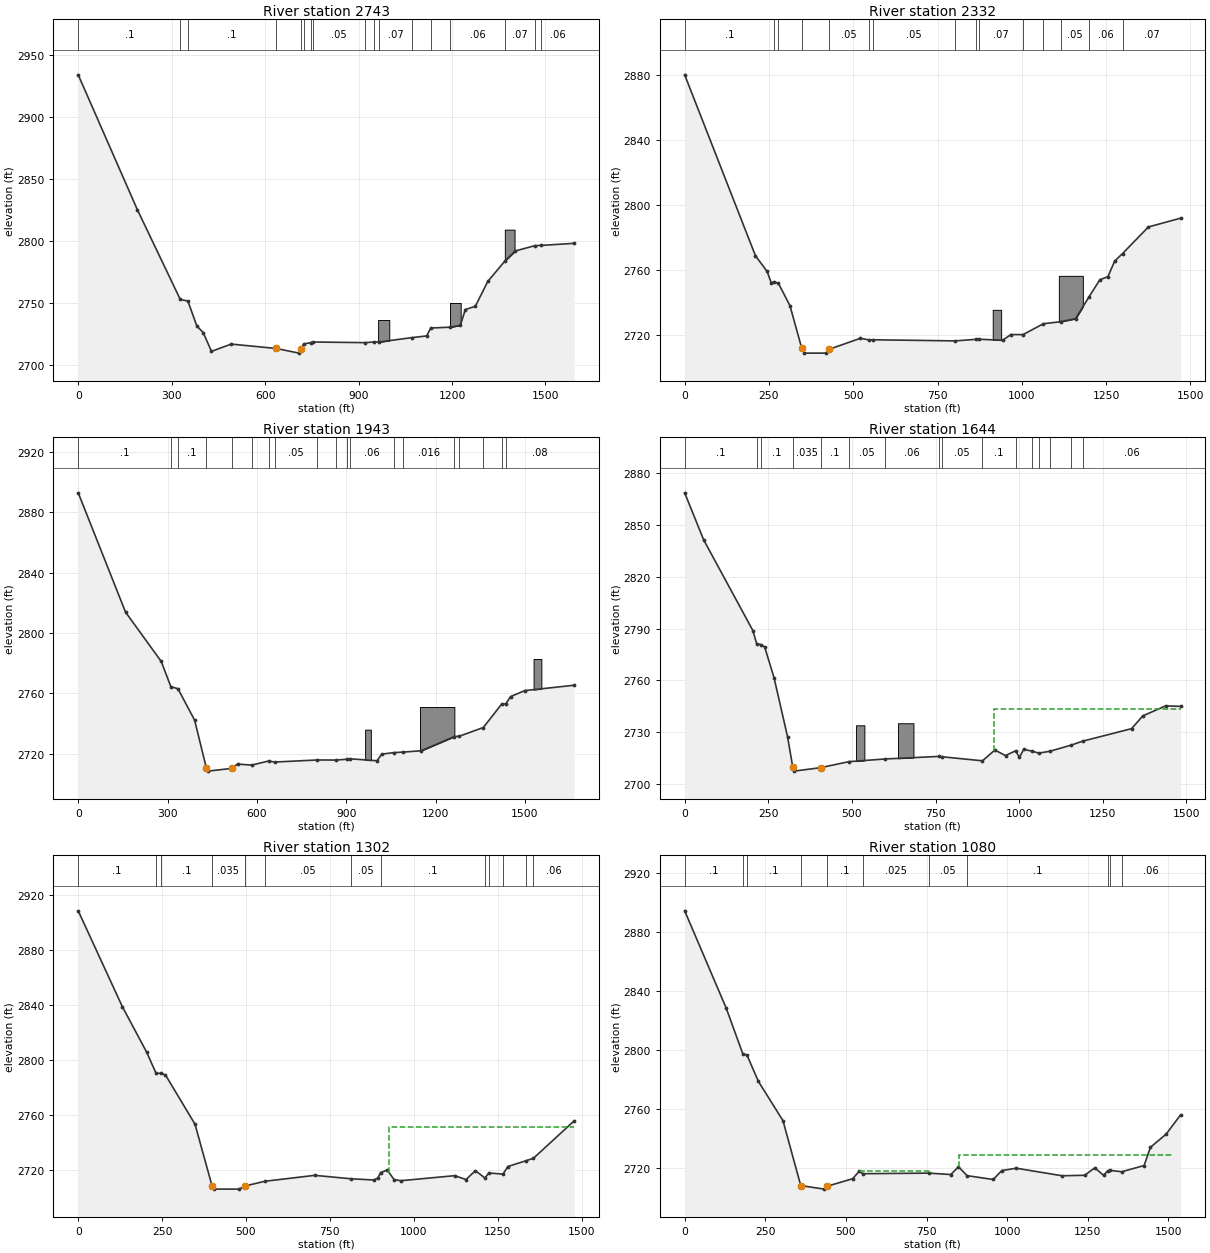
Type RM Length L Ch R = 1 ,2743    ,465.1,411.1,300.6
BEGIN DESCRIPTION:
channel burned 2.38':
lidar invert = 2711.78
effective invert = 2709.40
END DESCRIPTION:
Node Name=B
XS GIS Cut Line= 4
2305283.18235732563849.4444471132305224.23438804564225.804558694
2304865.32342433564638.8012927322304839.01278154565302.143291521
#Sta/Elev= 30
       0 2933.88     190 2825.02   327.7 2752.66     352 2751.41   380.9 2731.23
   401.3 2725.95   427.8 2710.81   491.1 2716.69   635.7 2713.16   708.7  2709.4
  715.83 2713.13   723.6 2716.74   745.8 2717.83     753 2718.38   922.1 2717.85
   950.5 2718.44   966.2 2718.38  1070.1 2721.87  1118.6 2723.28  1131.7 2729.65
  1194.7 2730.34  1226.7 2731.82  1242.7 2744.58  1274.8 2747.15  1314.8 2767.23
  1370.5  2783.9  1402.9 2791.77  1466.7 2796.15    1486 2796.29    1592 2797.97
#Mann= 17 ,-1,0
       0      .1       0   327.7    .016       0     352      .1       0
   635.7    .035       0  715.83      .1       0   723.6     .05       0
   745.8    .016       0     753     .05       0   922.1     .06       0
   950.5    .016       0   966.2     .07       0  1070.1     .08       0
  1131.7    .016       0  1194.7     .06       0  1370.5     .07       0
  1466.7    .016       0    1486     .06       0
#Block Obstruct= 3 ,-1
  962.64  998.51 2736.13 1193.52 1227.78 2749.86  1369.4 1400.73 2809.02
Bank Sta=635.7,715.83
XS Rating Curve= 0 ,0
Exp/Cntr(USF)=0,0
Exp/Cntr=0.3,0.1

Type RM Length L Ch R = 1 ,2332    ,402.8,389.5,290.2
BEGIN DESCRIPTION:
channel burned 1.39':
lidar invert = 2710.38
interpolated invert = 2708.99
END DESCRIPTION:
XS GIS Cut Line= 3
2304849.10462145563824.125288839 2304610.9985615564470.413165858
2304597.91581095565252.761648566
#Sta/Elev= 30
       0 2879.93     210 2768.79   244.5 2759.16   256.9 2752.04   265.4 2752.87
   278.2 2751.82   312.3 2738.14   347.3 2711.97   354.9 2708.99     419 2708.99
   427.4 2711.26   521.2  2718.1   546.8 2717.13   559.2 2717.19   802.6 2716.51
   863.6 2717.44   871.8 2717.52   943.6  2716.9   967.6  2720.4  1003.6 2720.36
  1064.1 2727.03  1115.3 2728.29  1159.6 2730.14  1199.6 2743.61  1231.6 2754.04
  1255.6 2755.97  1275.6 2765.55    1299 2770.17  1375.6 2786.48  1471.2  2791.9
#Mann= 15 ,-1,0
       0      .1       0   265.4    .016       0   278.2      .1       0
   347.3    .035       0   427.4     .05       0   546.8    .016       0
   559.2     .05       0   802.6     .07       0   863.6    .016       0
   871.8     .07       0  1003.6     .08       0  1064.1    .016       0
  1115.3     .05       0  1199.6     .06       0    1299     .07       0
#Block Obstruct= 2 ,-1
   913.8  938.79 2735.59 1109.93 1181.17 2756.47
Bank Sta=347.3,427.4
XS Rating Curve= 0 ,0
Exp/Cntr(USF)=0,0
Exp/Cntr=0.3,0.1

Type RM Length L Ch R = 1 ,1943    ,299.6,298.9,285.4
BEGIN DESCRIPTION:
channel burned 0.44':
lidar invert = 2709.04
effective invert = 2708.60
END DESCRIPTION:
XS GIS Cut Line= 2
2304349.08376713563722.4795901942304290.13579785565386.626107666
#Sta/Elev= 30
       0 2892.77   158.8 2813.87   278.9 2781.15   310.9 2764.55   334.9 2763.12
   390.9 2742.31  430.272710.634     435  2708.6     515 2710.39     535 2713.26
   582.8 2712.59   639.1 2715.29   659.1  2714.6   803.2 2715.99     865 2715.92
   902.3 2716.46   911.3 2716.78  1003.3 2715.47  1019.3 2719.84    1060 2720.86
    1089 2721.18  1151.3 2722.06  1263.3  2731.5  1279.5 2731.69  1360.3 2737.46
  1422.2 2753.07  1435.6 2753.07  1451.6 2757.91  1499.6  2761.9  1665.2 2765.43
#Mann= 19 ,-1,0
       0      .1       0   310.9    .016       0   334.9      .1       0
  430.27    .035       0     515      .1       0   582.8     .05       0
   639.1    .016       0   659.1     .05       0   803.2    .016       0
     865     .06       0   902.3    .016       0   911.3     .06       0
    1060     .08       0    1089    .016       0  1263.3    .016       0
  1279.5     .05       0  1360.3     .08       0  1422.2    .016       0
  1435.6     .08       0
#Block Obstruct= 3 ,-1
  963.31  982.55 2736.06 1147.71 1263.01 2751.05 1528.95 1555.18 2782.82
Bank Sta=430.27,515
XS Rating Curve= 0 ,0
Exp/Cntr(USF)=0,0
Exp/Cntr=0.3,0.1

Type RM Length L Ch R = 1 ,1644    ,334.8,342.4,347.4
BEGIN DESCRIPTION:
channel burned 0.60':
lidar invert = 2708.03
interpolated invert = 2707.43
END DESCRIPTION:
XS GIS Cut Line= 3
2304037.97408754563797.9597877452304032.74098732564767.038259234
2304185.52839553565257.184959458
#Sta/Elev= 30
       0 2868.55    56.7 2841.36   203.9  2788.8   215.2 2781.18   227.8 2780.71
   239.2 2779.27   267.2 2761.47   307.4 2727.42   323.2 2709.66   327.2 2707.43
   406.72709.448   490.4  2712.9   599.2 2714.47   759.2 2715.94   768.9 2715.74
   890.2 2713.41   927.2 2719.62   959.2 2716.45   989.5 2719.23  1000.7 2715.33
  1013.2 2720.01  1038.4 2719.02  1058.4 2717.86  1091.7 2718.93  1155.4 2722.49
  1189.2 2724.75  1335.9 2732.02  1369.6 2739.44  1437.6 2745.19  1482.5 2744.94
#Mann= 16 ,-1,0
       0      .1       0   215.2    .016       0   227.8      .1       0
   323.2    .035       0   406.7      .1       0   490.4     .05       0
   599.2     .06       0   759.2    .016       0   768.9     .05       0
   890.2      .1       0   989.5     .07       0  1038.4    .016       0
  1058.4     .06       0  1091.7     .08       0  1155.4     .07       0
  1189.2     .06       0
#XS Ineff= 2 , 0
                          924.44         2743.16
Permanent Ineff=
       F       F
#Block Obstruct= 2 ,-1
  512.32  537.19 2733.97  637.49  683.92 2735.15
Bank Sta=323.2,406.7
XS Rating Curve= 0 ,0
Exp/Cntr(USF)=0,0
Exp/Cntr=0.3,0.1

Type RM Length L Ch R = 1 ,1302    ,224.5,221.9,210.9
BEGIN DESCRIPTION:
channel burned 0.53':
lidar invert = 2706.62
interpolated invert = 2706.09
END DESCRIPTION:
XS GIS Cut Line= 3
2303732.98974624563789.6815300122303664.41605449564909.718495265
2303906.70976534565170.298523916
#Sta/Elev= 30
       0 2908.65   131.7 2838.81   203.9 2805.83   231.9 2790.45     248 2790.33
     260 2789.19   348.1 2753.33   398.6  2708.7   404.3 2706.13   479.9 2706.09
   495.82708.307   556.5 2711.82   704.8 2716.12     813 2713.62   881.1 2712.74
   893.2 2714.23   901.2 2718.13   921.2 2719.94   941.3 2713.08   961.3 2712.22
  1122.1 2715.89  1155.5 2713.06  1183.8 2719.51  1212.2 2714.16  1223.5 2717.84
  1265.9 2717.02  1280.4 2722.54  1333.9 2726.72  1356.5 2728.51    1478 2755.78
#Mann= 13 ,-1,0
       0      .1       0   231.9    .016       0     248      .1       0
   398.6    .035       0   495.8     .08       0   556.5     .05       0
     813     .05       0   901.2      .1       0  1212.2     .06       0
  1223.5    .016       0  1265.9     .06       0  1333.9     .07       0
  1356.5     .06       0
#XS Ineff= 2 , 0
                          926.98         2751.04
Permanent Ineff=
       F       F
Bank Sta=398.6,495.8
XS Rating Curve= 0 ,0
Exp/Cntr(USF)=0,0
Exp/Cntr=0.3,0.1

Type RM Length L Ch R = 1 ,1080    ,300.4,298.1,287.9
BEGIN DESCRIPTION:
channel burned 0.98':
lidar invert = 2706.3
interpolated invert = 2705.32
END DESCRIPTION:
Node Name=A
XS GIS Cut Line= 4
2303495.26761484563844.5404834122303467.83813814564827.430065165
2303558.23847027564967.9440364612303845.57917255565227.715310212
#Sta/Elev= 30
       0 2894.52   128.7 2828.41   180.7 2797.03   192.7 2796.65   228.7 2778.51
   304.8 2751.86  359.85 2707.75   432.8 2705.32     442  2707.3   520.8 2712.39
   540.8 2717.41   552.9 2715.81   756.9 2716.19     825 2715.25     849  2720.5
   875.6 2714.48   956.6 2711.87   983.3 2717.95  1028.2 2719.54  1170.1  2714.4
  1240.4 2714.74  1271.5 2719.81  1298.6 2714.75  1311.2 2717.58  1320.1 2718.05
    1355 2717.14  1424.5 2721.36  1444.1 2733.74  1492.7 2742.68  1537.7 2755.81
#Mann= 11 ,-1,0
       0      .1       0   180.7    .016       0   192.7      .1       0
  359.85    .035       0     442      .1       0   552.9    .025       0
   756.9     .05       0   875.6      .1       0  1311.2     .06       0
  1320.1    .016       0    1355     .06       0
#XS Ineff= 2 ,-1
  542.91  764.652717.779  849.33 1515.27  2728.3
Permanent Ineff=
       T       F
Bank Sta=359.85,442
XS Rating Curve= 0 ,0
Exp/Cntr(USF)=0,0
Exp/Cntr=0.3,0.1