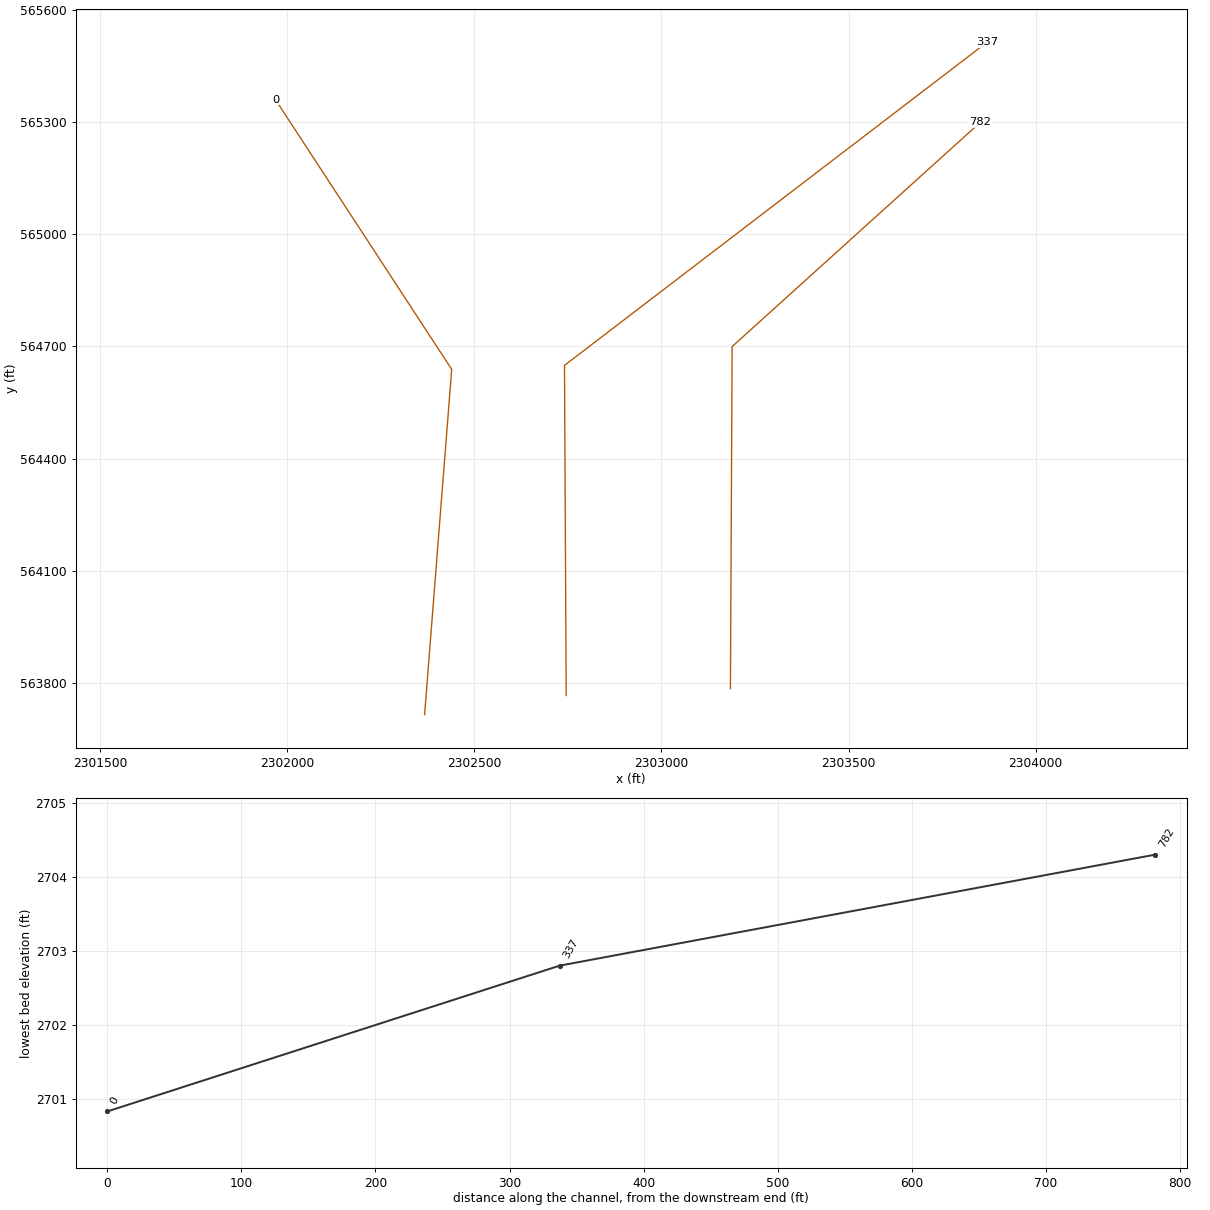
HEC-RAS study EFGRNBRRRV.prj: EFGRNBRRRV

--- EFGRNBRRRV.g01 (geometry) --- (continued)

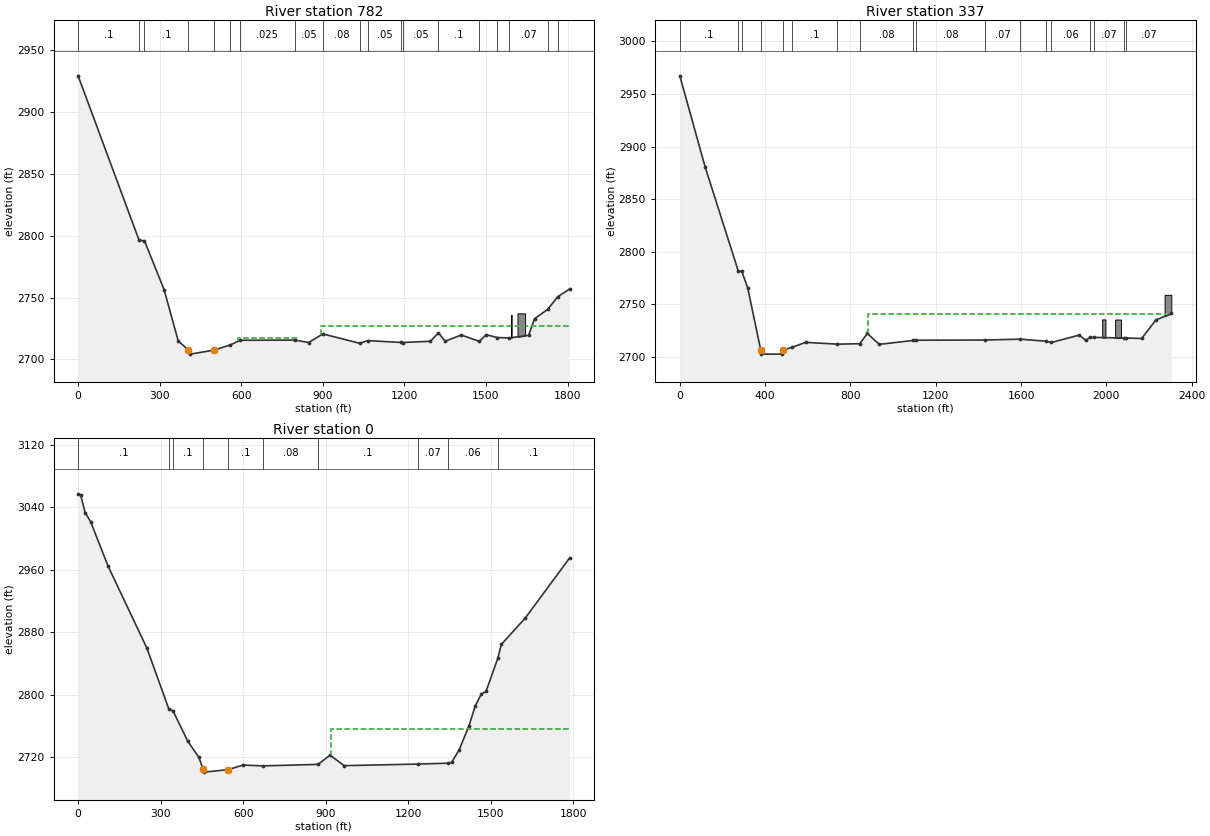
Type RM Length L Ch R = 1 ,782     ,444.1,444.2,446.7
BEGIN DESCRIPTION:
channel burned 1.54':
lidar invert = 2705.84
effective invert = 2704.30
END DESCRIPTION:
XS GIS Cut Line= 3
2303184.40021224563785.1099505622303188.97179169564699.425840564
2303851.85081194565298.302748516
#Sta/Elev= 30
       0  2929.3   224.1 2796.47   244.1 2795.84   316.1 2756.53   368.1 2715.03
  405.38 2707.65   412.1  2704.3   500.1 2707.53   560.1 2711.79   596.1  2715.5
   796.3 2715.64   848.1 2713.69   900.1 2720.64  1036.3 2713.04  1065.1 2715.24
  1188.2 2713.73  1195.4 2713.68    1296 2714.73  1325.4 2721.56  1349.9 2714.74
  1409.2 2719.77  1475.8 2714.61  1500.8 2720.02  1540.9 2717.73  1586.2 2717.38
    1657 2719.53  1678.7 2732.91  1727.2 2740.51  1764.6 2750.82  1807.7 2756.93
#Mann= 19 ,-1,0
       0      .1       0   224.1    .016       0   244.1      .1       0
  405.38    .035       0   500.1     .08       0   560.1     .05       0
   596.1    .025       0   796.3     .05       0   900.1     .08       0
  1036.3     .07       0  1065.1     .05       0  1188.2     .08       0
  1195.4     .05       0  1325.4      .1       0  1475.8     .06       0
  1540.9    .016       0  1586.2     .07       0  1727.2     .06       0
  1764.6     .07       0
#XS Ineff= 2 ,-1
  588.26  808.872717.678   892.3  1807.7 2727.33
Permanent Ineff=
       T       F
#Block Obstruct= 2 ,-1
 1591.98 1594.61 2736.07 1616.09    1644 2737.27
Bank Sta=405.38,500.1
XS Rating Curve= 0 ,0
Exp/Cntr(USF)=0,0
Exp/Cntr=0.3,0.1

Type RM Length L Ch R = 1 ,337     ,343,337.4,312.8
BEGIN DESCRIPTION:
channel burned 2.38':
lidar invert = 2705.18
effective invert = 2702.80
END DESCRIPTION:
XS GIS Cut Line= 3
2302745.52858504563766.8236327612302740.95700559564649.138466614
2303870.49804391565512.909186835
#Sta/Elev= 30
       0 2967.14   118.4 2880.76   274.4 2781.56   290.2 2781.57   318.4 2765.62
  379.21 2706.85   382.4 2702.86   478.4  2702.8  485.82 2706.74     525 2709.19
   590.4 2713.99   738.4 2712.27   843.4 2712.69   879.2 2722.42   935.1 2712.09
  1093.1 2715.76  1107.9    2716  1430.2  2716.2  1596.4 2717.01  1717.2 2715.05
  1742.4 2713.87  1873.3 2720.92  1903.3 2715.75  1922.8  2718.8  1943.8 2718.69
  2080.2 2718.08  2091.7 2718.11  2165.4 2717.66  2230.9 2735.03  2304.3  2741.5
#Mann= 18 ,-1,0
       0      .1       0   274.4    .016       0   290.2      .1       0
  379.21    .035       0  485.82     .08       0     525      .1       0
   738.4     .07       0   843.4     .08       0  1093.1      .1       0
  1107.9     .08       0  1430.2     .07       0  1596.4     .08       0
  1717.2     .07       0  1742.4     .06       0  1922.8    .016       0
  1943.8     .07       0  2080.2    .016       0  2091.7     .07       0
#XS Ineff= 2 , 0
                          881.69         2740.58
Permanent Ineff=
       F       F
#Block Obstruct= 3 ,-1
 1980.19 1995.29 2735.82 2040.82 2068.19 2735.67 2272.82 2304.28 2759.12
Bank Sta=379.21,485.82
XS Rating Curve= 0 ,0
Exp/Cntr(USF)=0,0
Exp/Cntr=0.3,0.1

Type RM Length L Ch R = 1 ,0       ,0,0,0
BEGIN DESCRIPTION:
channel burned 2.97':
lidar invert = 2703.8
interpolated invert = 2700.83
END DESCRIPTION:
XS GIS Cut Line= 3
 2302367.0921394563715.8402644162302439.53524422564638.589751616
2301968.49269991565359.419352612
#Sta/Elev= 30
       0 3057.48     9.7 3055.42    25.4 3033.55    45.5 3021.72   109.1 2964.69
   250.1 2859.66   330.4 2781.16   344.5 2779.73   398.6 2740.46   438.7 2719.84
   454.7 2704.54   458.7 2700.83  545.79 2704.05   599.2 2709.87   671.4 2708.84
     872 2710.76   916.1 2722.52   966.9 2709.15  1234.5 2711.15    1346 2712.29
  1357.6 2713.18  1385.1 2729.23  1421.2 2760.44  1443.6 2785.68  1465.5 2800.64
    1483 2804.41    1526 2847.09  1538.6 2864.52  1626.2 2898.62  1786.7 2975.33
#Mann= 10 ,-1,0
       0      .1       0   330.4    .016       0   344.5      .1       0
   454.7    .035       0  545.79      .1       0   671.4     .08       0
     872      .1       0  1234.5     .07       0    1346     .06       0
    1526      .1       0
#XS Ineff= 2 , 0
                          918.31         2756.33
Permanent Ineff=
       F       F
Bank Sta=454.7,545.79
XS Rating Curve= 0 ,0
Exp/Cntr(USF)=0,0
Exp/Cntr=0.3,0.1
LCMann Table=0

Chan Stop Cuts=-1
Use User Specified Reach Order=0
Composite Channel Slope=5